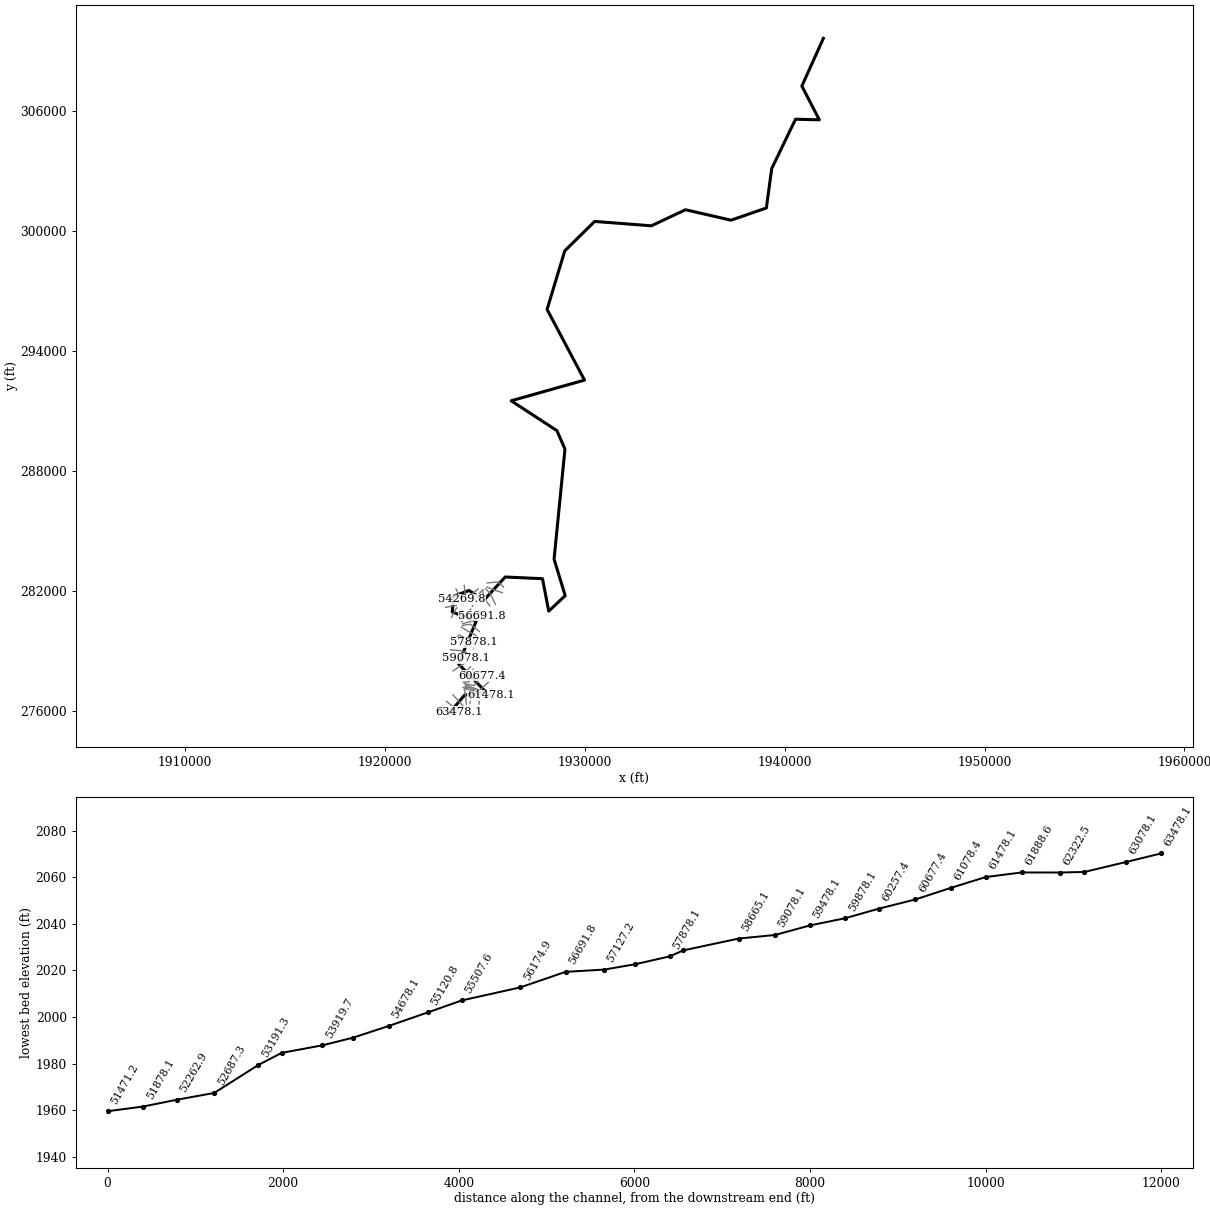
--- PnyCrk.prj (project) ---

Proj Title=PnyCrk
Current Plan=p01
Default Exp/Contr=0,0
English Units
Geom File=g01
Flow File=f01
Plan File=p01
BEGIN DESCRIPTION:
END DESCRIPTION:
DSS Export Rating Curves= 0
DSS Export Rating Curve Sorted= 0
DSS Export Volume Flow Curves= 0
DXF OffsetX= 0
DXF OffsetY= 0
DXF ScaleX= 0
DXF ScaleY= 0

--- PnyCrk.p01 (plan) ---

Plan Title=Floodplain
Program Version=4.00
Geom File=g01
Flow File=f01
K Sum by GR=0
Std Step Tol=0.01
Critical Tol=0.01
Num of Std Step Trials=20
Max Error Tol=0.3
Flow Tol Ratio=0.001
Split Flow NTrial=30
Split Flow Tol=0.02
Split Flow Ratio=0.02
Log Output Level=0
Friction Slope Method=1
Unsteady Friction Slope Method=2
Unsteady Bridges Friction Slope Method=1
Global Log Level=0
CheckData=False
Run HTab=0
Run UNet=0
Run PostProcess=0
UNET Theta=0
UNET Theta Warmup=0
UNET ZTol=0
UNET ZSATol=0
UNET MxIter=0
UNET MaxInSteps=0
UNET DtIC=0
UNET DtMin=0
UNET MaxCRTS=0
UNET WFStab=0
UNET SFStab=0
UNET WFX=0
UNET SFX=0
UNET DSS MLevel=0
UNET DZMax Abort=0
UNET Convert EG Bridges=0
UNET Use Existing IB Tables=0
UNET Froude Limit=0
UNET Froude Power=0
Write IC File=0
Echo Input=False
Echo Output=False
Write Detailed=0

--- PnyCrk.f01 (steady flow) ---

Flow Title=NFF Regression Equation
Program Version=4.00
Number of Profiles=1
Profile Names=P100yr
River Rch & RM=PnyCrk,Main      ,63478.1
11080.04
River Rch & RM=PnyCrk,Main      ,57127.2
11157.84
River Rch & RM=PnyCrk,Main      ,56691.8
11157.84
River Rch & RM=PnyCrk,Main      ,34298.9
11499.16
River Rch & RM=PnyCrk,Main      ,33861.5
12844.04
River Rch & RM=PnyCrk,Main      ,13525.7
13548.08
River Rch & RM=PnyCrk,Main      ,11878.1
14454.87
River Rch & RM=PnyCrk,Main      ,620.7
15122.14
Boundary for River Rch & Prof#=PnyCrk,Main      ,1
Up Type=0
Dn Type=3
Dn Slope=0.01068

--- PnyCrk.g01 (geometry) ---

Geom Title=USGS 3m DEM
Program Version=4.10

River Reach=PnyCrk          ,Main
Reach XY= 30
     1923218.046      275863.938      1923989.35      276776.538
     1925061.093      276931.694     1923690.508      278336.355
     1924573.093      280478.602     1923377.726      280934.294
     1923441.341      281722.959     1924217.536      282011.542
     1924949.677       281514.53     1926024.777      282685.896
     1927889.018      282598.867     1928201.675      280978.552
      1929025.02      281750.446      1928468.28      283578.377
      1929012.87       289074.86      1928613.83       290003.11
     1926323.384       291498.75     1929990.348      292532.963
     1928117.991      296069.604     1929002.812      298996.257
     1930497.685      300469.914     1933333.027      300251.385
     1935044.945       301053.93     1937321.381       300531.39
     1939086.585      301141.989     1939353.792       303111.06
     1940545.188      305582.576       1941735.7      305551.306
     1940861.736      307240.086     1941938.631      309627.305

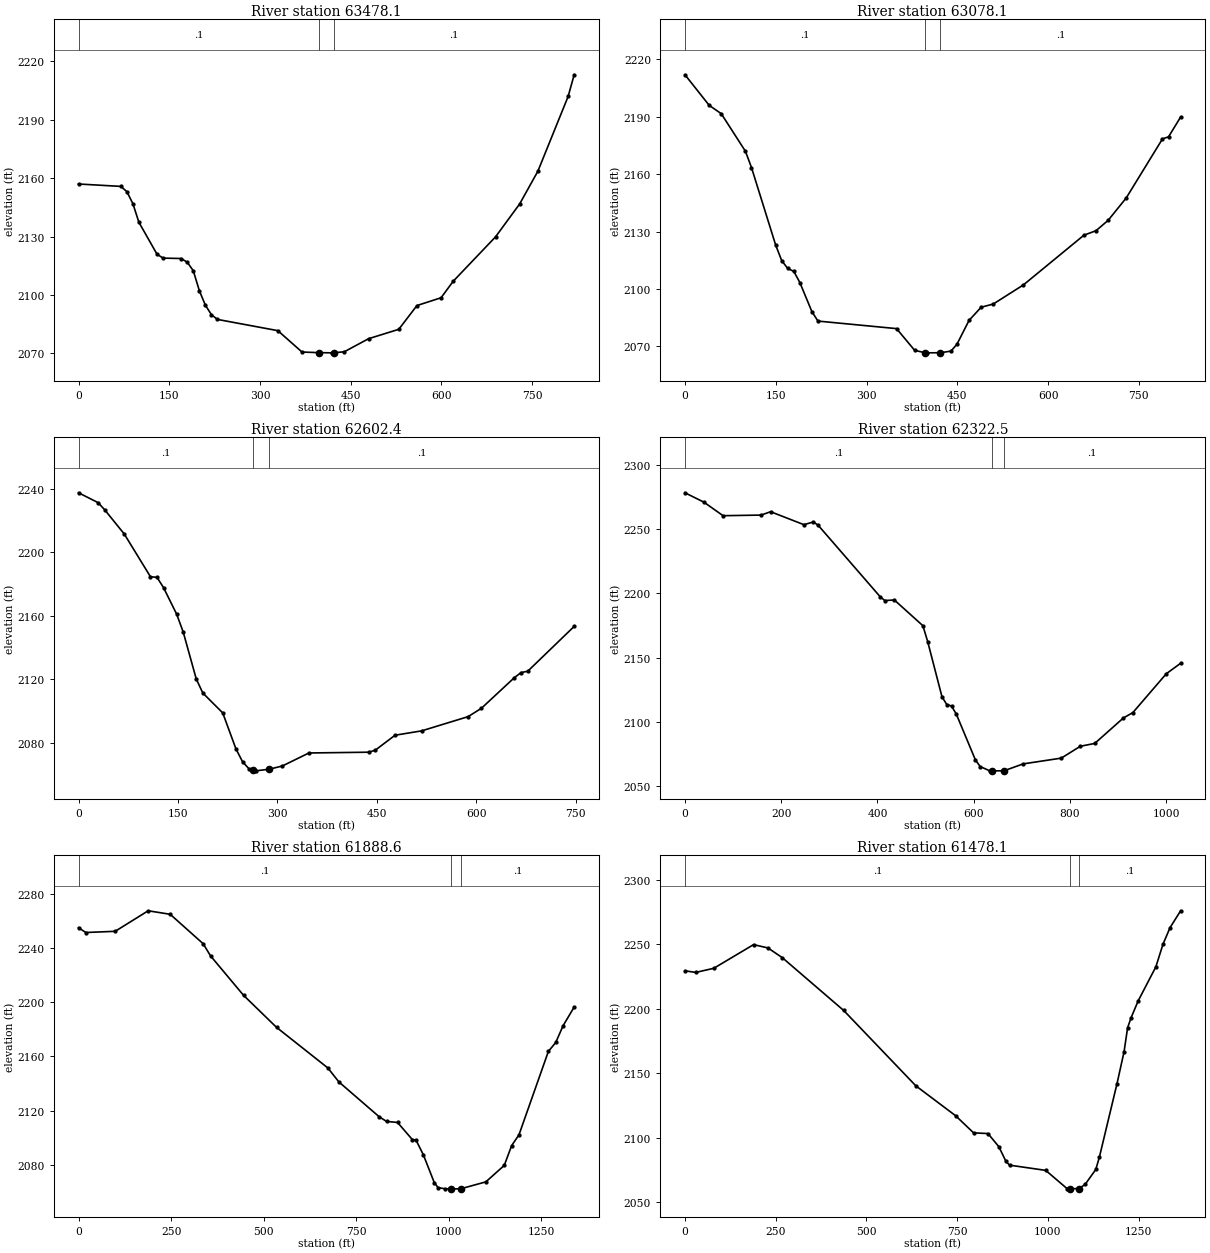
Type RM Length L Ch R = 1 ,63478.1 ,404,399.9,395.7
XS GIS Cut Line= 3
     1923090.615      276462.191     1923407.073      276202.481
     1923725.312      275944.127
#Sta/Elev= 30
       0 2156.97    69.9 2155.74    79.9 2153.07    89.9 2146.85    99.8 2137.32
   129.8  2120.9   139.8 2118.92   169.7 2118.71   179.7  2116.8   189.7 2112.45
   199.7 2102.24   209.7 2094.73   219.7 2089.89   229.6 2087.44   329.5 2081.67
   369.4  2070.7   396.9 2070.38   419.4 2070.28   421.9  2070.3   439.4 2070.84
   479.4 2077.53   529.4 2082.36   559.4 2094.56   599.3 2098.57   619.3 2107.02
   689.3 2129.82   729.3 2146.78   759.3 2163.53   809.3  2201.9   819.3 2213.05
#Mann= 3 , 0 , 0
       0      .1       0   396.9    .045       0   421.9      .1       0
Bank Sta=396.9,421.9
XS Rating Curve= 0 ,0
Exp/Cntr=0.3,0.1

Type RM Length L Ch R = 1 ,63078.1 ,493.4,475.3,457.3
XS GIS Cut Line= 3
     1923412.545      276790.528     1923687.536      276487.098
     1923962.528      276183.668
#Sta/Elev= 30
       0 2211.94      40 2195.97    59.9 2191.62    99.9 2171.96   109.9 2163.45
   149.8 2122.99   159.8 2114.82   169.8 2110.69   179.8  2109.2   189.8 2103.34
   209.7 2088.15   219.7  2083.2   349.6 2079.26   379.5 2067.91     397 2066.62
   399.5  2066.6     422 2066.66   439.5  2067.5   449.4  2071.1   469.4 2083.57
   489.4 2090.44   509.4 2092.11   559.3 2102.13   659.2 2128.09   679.2 2130.45
   699.2 2135.85   729.1 2147.56     789 2178.43     799  2179.5     819 2189.87
#Mann= 3 , 0 , 0
       0      .1       0     397    .045       0     422      .1       0
Bank Sta=397,422
XS Rating Curve= 0 ,0
Exp/Cntr=0.3,0.1

Type RM Length L Ch R = 1 ,62602.4 ,285.8,279.7,273.5
XS GIS Cut Line= 3
     1923974.864      277051.315     1924030.981      276872.441
     1924083.591      276314.774
#Sta/Elev= 30
       0 2237.63    29.6  2231.4    39.5  2226.9    69.1 2211.58   108.5 2184.71
   118.4 2184.31   128.3 2177.78     148 2161.12   157.9 2149.87   177.6 2120.23
   187.5 2111.37   217.5 2098.86   237.5  2076.1   247.5    2068   257.5 2063.44
   262.6 2062.86   267.5 2062.31   287.6 2063.33   307.5 2065.38   347.5 2073.57
   437.5 2074.06   447.5  2075.3   477.5 2084.77   517.6 2087.52   587.6 2096.48
   607.6 2101.72   657.6 2121.14   667.6 2124.27   677.6 2125.12   747.6 2153.38
#Mann= 3 , 0 , 0
       0      .1       0   262.6    .045       0   287.6      .1       0
Bank Sta=262.6,287.6
XS Rating Curve= 0 ,0
Exp/Cntr=0.3,0.1

Type RM Length L Ch R = 1 ,62322.5 ,432.3,434,435.7
XS GIS Cut Line= 3
     1923918.495       277168.67      1924336.12      276904.007
     1924266.992      276372.927
#Sta/Elev= 30
       0 2278.12    39.6 2270.77    79.1 2260.31   158.2 2260.79     178  2263.4
   247.2 2253.33     267 2255.47   276.9 2252.82   405.4 2197.44   415.3 2194.37
   435.1 2194.83   494.4 2174.83   504.3 2162.56   534.1 2119.58     544  2113.6
   553.9 2112.41   563.8  2106.2   603.5 2070.58   613.4 2065.43   633.3 2062.07
   637.9 2062.07   662.9  2062.1   702.7 2067.46     782 2071.95   821.7 2081.18
   851.5 2083.36     911 2103.14   930.8 2107.35  1000.2 2137.51    1030 2145.65
#Mann= 3 , 0 , 0
       0      .1       0   637.9    .045       0   662.9      .1       0
Bank Sta=637.9,662.9
XS Rating Curve= 0 ,0
Exp/Cntr=0.3,0.1

Type RM Length L Ch R = 1 ,61888.6 ,374.6,410.4,449.1
XS GIS Cut Line= 3
     1923986.645      277167.989     1924749.986      276837.368
     1924716.074      276331.805
#Sta/Elev= 30
       0 2255.26    19.8  2251.7      99 2252.58   188.2 2267.77   247.6 2265.17
   336.7 2243.39   356.5 2234.44   445.6 2205.27   534.8 2181.55   673.4 2151.51
   703.1  2141.2   812.1 2115.39   831.9 2111.97   861.7 2111.19   901.4 2098.58
   911.4 2098.18   931.2 2087.35     961 2066.59     971 2063.03   990.8  2062.1
  1006.7  2062.1  1031.7  2062.1  1100.1 2067.26  1149.8 2079.43  1169.7 2094.05
  1189.5 2102.02    1269 2163.78  1288.9 2170.38  1308.8 2182.82  1338.6 2196.55
#Mann= 3 , 0 , 0
       0      .1       0  1006.7    .045       0  1031.7      .1       0
Bank Sta=1006.7,1031.7
XS Rating Curve= 0 ,0
Exp/Cntr=0.3,0.1

Type RM Length L Ch R = 1 ,61478.1 ,368.6,399,426.5
XS GIS Cut Line= 3
     1924041.425      277215.886     1925047.999      276842.749
     1925331.211      276770.338
#Sta/Elev= 30
       0 2229.55    29.8  2228.3    79.5 2231.52   188.9 2249.89   228.6 2247.33
   268.4 2239.71   437.4 2198.72   636.2 2140.16   745.5 2116.99   795.2 2103.64
     835 2103.07   864.8  2092.9   884.6 2081.37   894.6 2078.52     994 2074.47
  1053.6 2060.12    1061 2060.15    1086 2060.33  1102.7 2063.58    1132 2075.18
  1141.7  2084.5  1190.4 2141.76  1209.9 2166.64  1219.7 2185.34  1229.4 2193.17
  1248.9 2206.26  1297.6 2232.68  1317.1 2250.15  1336.6 2263.08  1365.8  2276.2
#Mann= 3 , 0 , 0
       0      .1       0    1061    .045       0    1086      .1       0
Bank Sta=1061,1086
XS Rating Curve= 0 ,0
Exp/Cntr=0.3,0.1

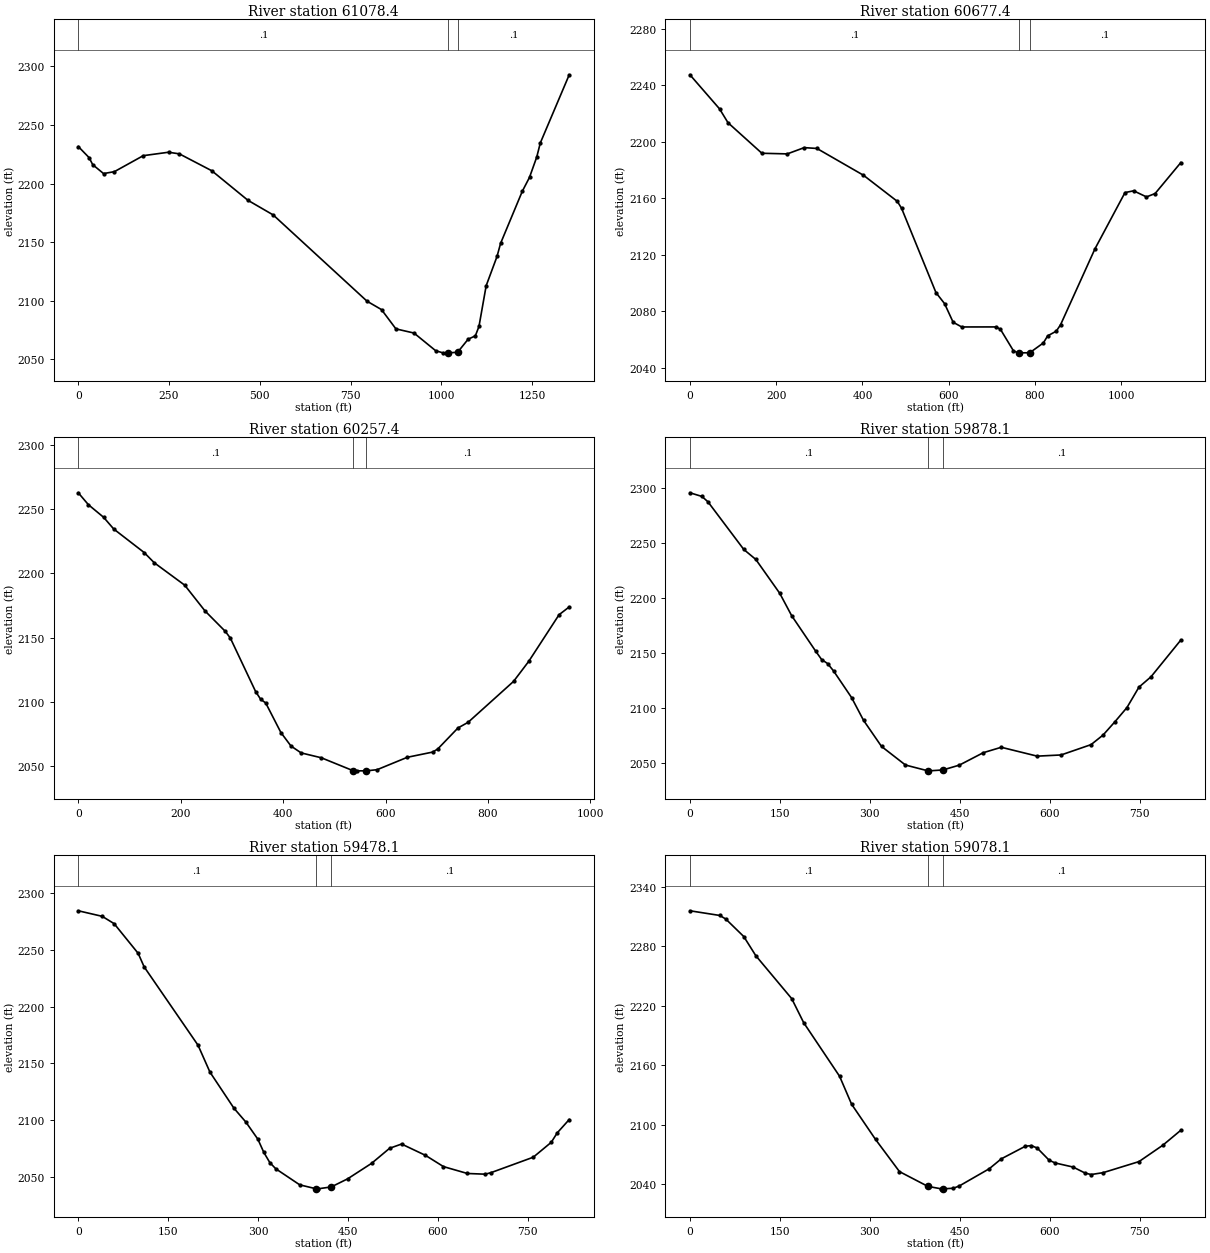
Type RM Length L Ch R = 1 ,61078.4 ,397.5,401,404.5
XS GIS Cut Line= 3
     1924030.612      277291.384     1924746.479      277019.749
     1925177.918      277417.314
#Sta/Elev= 30
       0  2231.6    29.8  2222.1    39.8 2216.08    69.6  2208.5    99.4 2210.12
     179 2223.78   248.6 2226.71   278.4 2225.33   367.9 2210.88   467.4 2185.66
     537 2173.16   795.5 2099.51   835.3 2092.35     875 2075.89   924.8 2072.34
   984.4 2057.28  1004.3 2055.44  1019.8 2055.46  1044.8 2055.89  1073.9 2067.06
  1093.8 2069.95  1103.8 2077.99  1123.6 2112.73  1153.5 2137.72  1163.4 2148.96
  1223.1 2193.35    1243 2205.28  1262.9 2222.58  1272.8 2234.67  1352.4 2292.84
#Mann= 3 , 0 , 0
       0      .1       0  1019.8    .045       0  1044.8      .1       0
Bank Sta=1019.8,1044.8
XS Rating Curve= 0 ,0
Exp/Cntr=0.3,0.1

Type RM Length L Ch R = 1 ,60677.4 ,409.3,420.1,430.8
XS GIS Cut Line= 3
     1923985.785      277355.967     1924465.892      277254.741
     1924882.153      277750.654
#Sta/Elev= 30
       0 2247.28    68.7 2223.15    88.3 2213.35   166.8 2191.74   225.7 2191.29
     265 2195.73   294.4 2195.14   402.3 2176.18   480.8 2157.69   490.7 2152.76
   570.4  2093.1   590.3 2085.34   610.2 2072.13   630.1 2068.81   709.8 2068.84
   719.8 2067.16   749.6 2052.14   759.6  2050.5   762.7  2050.5   787.7 2050.55
   819.4 2057.52   829.3 2062.53   849.2 2065.81   859.2 2070.36   938.9 2124.07
  1008.6 2163.92  1028.6 2165.16  1058.4 2160.85  1078.4 2163.24  1138.1 2185.18
#Mann= 3 , 0 , 0
       0      .1       0   762.7    .045       0   787.7      .1       0
Bank Sta=762.7,787.7
XS Rating Curve= 0 ,0
Exp/Cntr=0.3,0.1

Type RM Length L Ch R = 1 ,60257.4 ,392,379.2,366.5
XS GIS Cut Line= 3
     1923924.354      277421.232     1924220.378      277444.138
     1924428.339      278072.401
#Sta/Elev= 30
       0 2262.78    19.8 2253.49    49.5 2243.71    69.3 2234.57   128.7 2216.29
   148.4 2208.34   207.8 2190.93   247.4 2170.91     287 2155.02   296.9 2149.82
   346.3 2108.18   356.2 2102.13     366 2099.31   395.7 2076.27   415.4 2065.78
   435.2 2060.45   474.7 2056.65     537 2046.56   543.8  2046.5     562  2046.5
   583.4 2047.37   642.6 2057.05     692 2061.09   701.9 2063.48   741.4 2079.83
   761.2 2084.23     850 2116.07   879.7 2131.69   938.9 2167.95   958.7 2173.99
#Mann= 3 , 0 , 0
       0      .1       0     537    .045       0     562      .1       0
Bank Sta=537,562
XS Rating Curve= 0 ,0
Exp/Cntr=0.3,0.1

Type RM Length L Ch R = 1 ,59878.1 ,405.5,400,394
XS GIS Cut Line= 3
     1923713.118      277612.393     1924001.333      277903.292
     1924289.873       278193.87
#Sta/Elev= 30
       0 2295.99      20 2292.66      30 2287.81    89.9 2244.28   109.9 2235.22
   149.8 2204.36   169.8 2183.86   209.7 2151.63   219.7 2143.94   229.7 2140.25
   239.7 2133.48   269.7 2109.22   289.6 2088.52   319.6 2064.71   359.6 2047.73
     397 2042.45   399.5 2042.44     422 2043.24   449.4 2047.64   489.4 2058.99
   519.4 2063.92   579.3 2055.84   619.2 2056.92   669.2 2066.35   689.2 2075.07
   709.1 2087.27   729.1 2100.17   749.1 2118.78   769.1 2128.15     819 2161.74
#Mann= 3 , 0 , 0
       0      .1       0     397    .045       0     422      .1       0
Bank Sta=397,422
XS Rating Curve= 0 ,0
Exp/Cntr=0.3,0.1

Type RM Length L Ch R = 1 ,59478.1 ,415.1,400,385.5
XS GIS Cut Line= 3
     1923417.334      277991.741     1923757.553      278219.616
     1924102.286      278440.814
#Sta/Elev= 30
       0 2284.55      40 2279.64    59.9 2273.16    99.9 2247.03   109.9 2235.09
   199.8    2166   219.7 2142.26   259.7 2110.45   279.6 2098.24   299.6 2083.15
   309.6 2071.46   319.6 2062.48   329.6    2057   369.5 2042.87     397 2039.37
   399.5 2039.35     422 2041.02   449.4 2048.17   489.4 2061.85   519.4  2075.1
   539.4 2078.86   579.3 2068.87   609.3 2058.95   649.2 2052.89   679.2 2052.27
   689.2 2053.74   759.1 2067.24   789.1 2080.37   799.1 2088.71   819.1 2100.47
#Mann= 3 , 0 , 0
       0      .1       0     397    .045       0     422      .1       0
Bank Sta=397,422
XS Rating Curve= 0 ,0
Exp/Cntr=0.3,0.1

Type RM Length L Ch R = 1 ,59078.1 ,416.7,413,409.4
XS GIS Cut Line= 3
     1923252.481      278580.658     1923661.568      278599.037
     1924070.655      278617.417
#Sta/Elev= 30
       0  2315.6    49.9 2310.87    59.9 2307.23    89.9 2289.58   109.9 2270.32
   169.8 2227.03   189.8 2202.74   249.7  2148.7   269.7 2120.56   309.6 2085.08
   349.6 2052.59     397 2037.69   419.5 2035.23     422 2035.23   439.5 2035.83
   449.4 2038.14   499.4 2055.51   519.4 2065.46   559.3  2078.1   569.3 2078.85
   579.3  2076.4   599.3 2064.06   609.3 2061.31   639.2  2057.2   659.2 2051.14
   669.2 2049.65   689.2 2051.53   749.1 2062.69     789 2079.25     819 2094.34
#Mann= 3 , 0 , 0
       0      .1       0     397    .045       0     422      .1       0
Bank Sta=397,422
XS Rating Curve= 0 ,0
Exp/Cntr=0.3,0.1

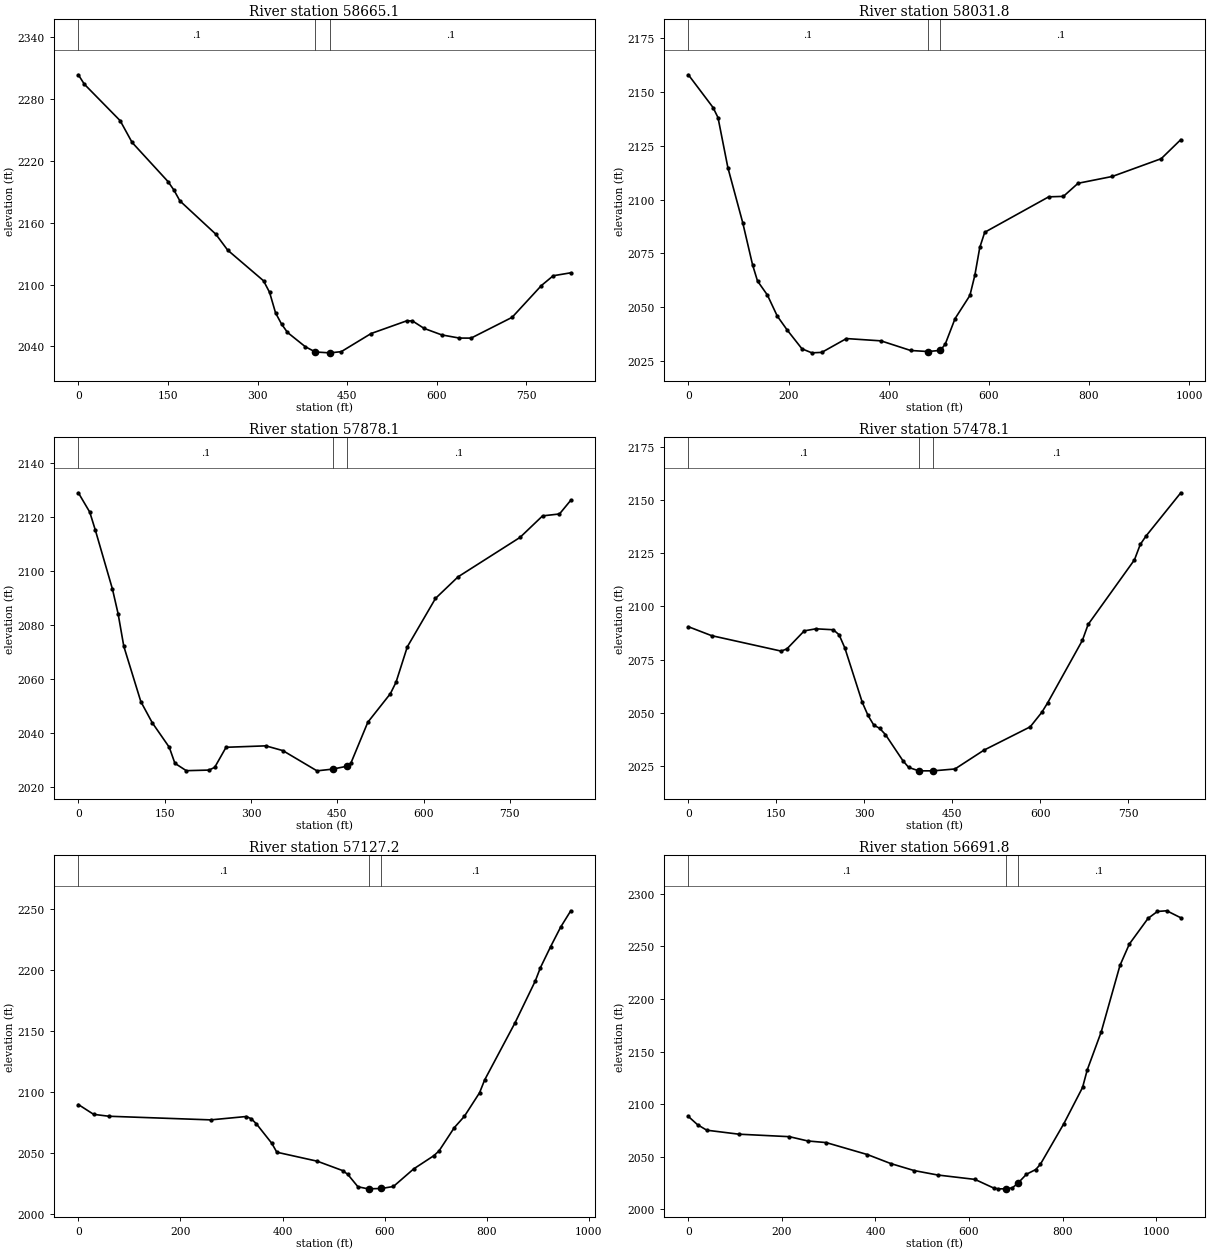
Type RM Length L Ch R = 1 ,58665.1 ,646.6,633.1,619.7
XS GIS Cut Line= 3
     1923281.627      279046.528     1923789.759      279001.871
     1924090.305      278910.114
#Sta/Elev= 30
       0 2303.54      10 2294.42      70 2258.99      90 2237.86     150 2199.96
     160 2191.65     170 2181.14     230 2148.91     250 2133.35     310 2103.61
   320.1 2092.41   330.1 2072.49   340.1 2061.65   350.1 2053.48   380.1 2039.55
   396.8 2034.53   420.1 2033.69   421.8 2033.71   440.1 2034.83   490.1 2052.44
   549.4 2064.69   559.2 2064.69   578.8  2057.4   608.3  2051.1   637.8 2048.02
   657.4 2047.98   726.1 2068.15   775.2 2099.04   794.9  2108.5   824.3 2111.37
#Mann= 3 , 0 , 0
       0      .1       0   396.8    .045       0   421.8      .1       0
Bank Sta=396.8,421.8
XS Rating Curve= 0 ,0
Exp/Cntr=0.3,0.1

Type RM Length L Ch R = 1 ,58031.8 ,150.8,153.6,157.8
XS GIS Cut Line= 3
      1923634.87      279712.196     1924194.327      279342.076
     1924428.793      279135.195
#Sta/Elev= 30
       0 2158.09    49.3 2142.84    59.2 2138.15    78.9 2114.85   108.5 2089.27
   128.2 2069.61   138.1 2062.04   157.8 2055.53   177.6  2045.7   197.3 2039.25
   226.9 2030.47   246.6  2028.6   266.4 2028.81   315.7 2035.25   384.7 2034.18
   443.9  2029.7   478.3 2029.21   503.3 2029.74     513 2032.63   532.7 2044.57
   562.3 2055.32   572.2 2064.77     582 2077.67   591.9 2084.74   719.7 2101.25
     749 2101.46   778.3 2107.56   846.7 2110.74   944.4 2119.02   983.5 2127.89
#Mann= 3 , 0 , 0
       0      .1       0   478.3    .045       0   503.3      .1       0
Bank Sta=478.3,503.3
XS Rating Curve= 0 ,0
Exp/Cntr=0.3,0.1

Type RM Length L Ch R = 1 ,57878.1 ,401.7,399.5,398.4
XS GIS Cut Line= 3
     1923709.696      279791.196     1924111.484      279579.465
     1924476.535      279412.027
#Sta/Elev= 30
       0 2128.95    19.8  2121.8    29.6 2115.07    59.2 2093.35    69.1 2084.17
      79 2072.11   108.6 2051.64   128.4 2043.84     158 2034.75   167.8 2028.81
   187.6 2026.08   227.1  2026.3     237 2027.32   256.7 2034.74   325.8 2035.27
   355.4 2033.51   414.7 2026.02   441.7 2026.65   466.7 2027.72   473.8 2028.94
   503.1 2044.02   542.3 2054.59   552.1 2058.82   571.7 2071.92   620.7 2089.85
   659.9 2097.83   767.6 2112.43   806.8  2120.4   836.2 2121.11   855.8 2126.18
#Mann= 3 , 0 , 0
       0      .1       0   441.7    .045       0   466.7      .1       0
Bank Sta=441.7,466.7
XS Rating Curve= 0 ,0
Exp/Cntr=0.3,0.1

Type RM Length L Ch R = 1 ,57478.1 ,354,350.8,345
XS GIS Cut Line= 3
     1923840.528      280175.831     1924183.116      279959.562
     1924569.401      279760.994
#Sta/Elev= 30
       0 2090.46    39.5 2086.26   158.1 2078.98     168 2080.02   197.6 2088.51
   217.4 2089.47     247 2089.03   256.9 2086.69   266.8 2080.43   296.4  2054.9
   306.3 2048.67   316.2  2044.1   326.1 2042.62     336 2039.66   365.6 2027.44
   375.5 2024.22   392.6 2022.62   395.3  2022.6   417.6  2022.6   454.5 2023.48
   503.8 2032.32   582.8 2043.32   602.6 2050.17   612.4 2054.57   671.7 2084.01
   681.5 2091.52   760.5 2121.95   770.4 2129.19   780.2 2133.15   839.5 2153.52
#Mann= 3 , 0 , 0
       0      .1       0   392.6    .045       0   417.6      .1       0
Bank Sta=392.6,417.6
XS Rating Curve= 0 ,0
Exp/Cntr=0.3,0.1

Type RM Length L Ch R = 1 ,57127.2 ,402.7,434.6,466.6
XS GIS Cut Line= 3
     1923892.786      280265.115     1924287.424      280323.039
     1924727.763      279967.499
#Sta/Elev= 30
       0 2089.53    29.9 2081.49    59.8 2079.92   259.3 2076.94   329.1 2079.71
     339 2077.81     349  2073.6   378.9 2057.78   388.9 2050.39   468.4 2042.99
     518 2035.28   527.9 2032.21   547.8 2022.03   567.7 2020.34   568.8 2020.35
   593.8 2020.63   617.3 2022.27     657  2036.7   696.7  2047.6   706.7 2051.48
   736.5 2070.52   756.3 2079.85   786.1 2099.21     796 2109.69   855.6 2156.62
   895.3 2190.97   905.2 2201.76   925.1 2218.95     945 2235.18   964.8 2248.56
#Mann= 3 , 0 , 0
       0      .1       0   568.8    .045       0   593.8      .1       0
Bank Sta=568.8,593.8
XS Rating Curve= 0 ,0
Exp/Cntr=0.3,0.1

Type RM Length L Ch R = 1 ,56691.8 ,502.5,516.5,530.5
XS GIS Cut Line= 3
     1923898.006      280352.145     1924287.424      280454.064
     1924866.585       280749.34
#Sta/Elev= 30
       0 2088.25    19.6 2080.41    39.3 2075.18     108 2071.38     216 2069.01
   255.3 2064.93   294.5  2063.4   382.9 2051.97   432.5 2043.46   482.5 2036.78
   532.6 2032.57   612.6 2028.37   652.6 2020.16   662.6 2019.39     679  2019.4
   692.6 2020.36     704 2024.54   722.6 2033.24   742.6 2037.77   752.6 2042.86
   802.6 2081.38   842.6 2115.82   852.6  2132.5   882.6 2168.82   922.6 2231.96
   942.6 2252.26   982.6 2276.69  1002.6 2283.28  1022.6 2283.92  1052.6 2277.26
#Mann= 3 , 0 , 0
       0      .1       0     679    .045       0     704      .1       0
Bank Sta=679,704
XS Rating Curve= 0 ,0
Exp/Cntr=0.3,0.1

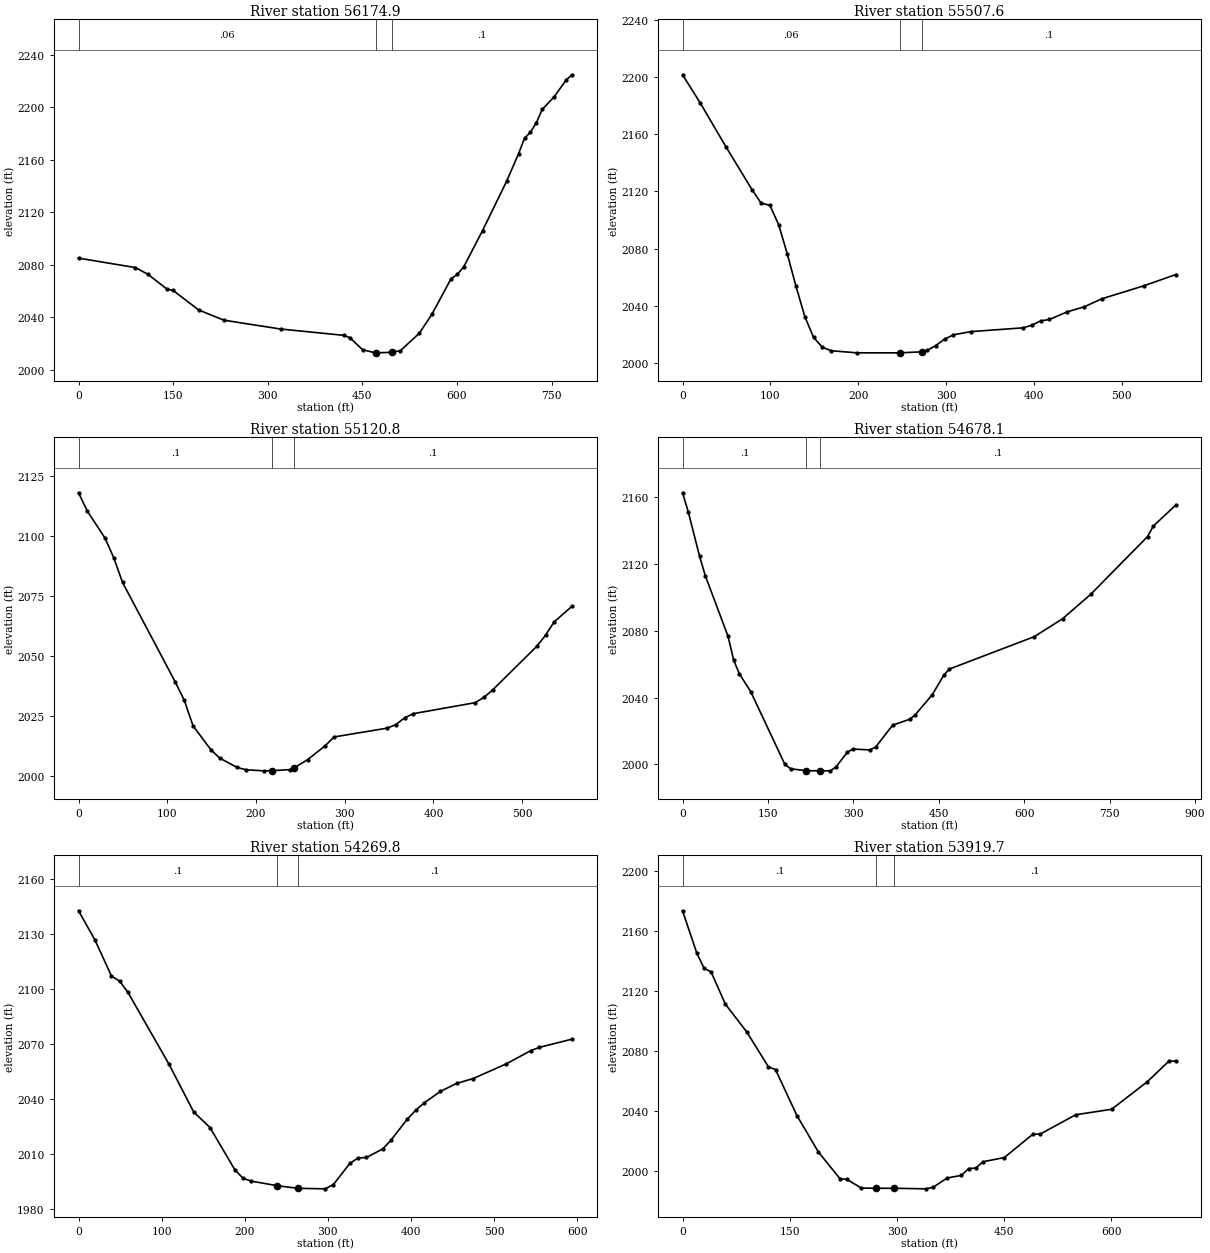
Type RM Length L Ch R = 1 ,56174.9 ,664,666.8,669.6
XS GIS Cut Line= 3
      1923851.81      280442.032     1924204.671      280988.508
      1924294.32      281085.053
#Sta/Elev= 30
       0 2084.89    90.1 2077.68   110.1 2072.54   140.1 2061.31   150.1 2060.22
   190.2 2045.43   230.2 2037.61   320.2 2030.86   420.3 2026.04   430.3  2024.2
   450.3 2015.08   470.4  2012.7   471.5 2012.71   496.5  2013.1   510.4 2014.41
   540.4 2027.72   560.4 2042.28   590.4 2069.03   600.5 2072.61   610.5 2078.13
   640.5 2105.85   678.7 2143.57   697.6 2164.47     707 2176.24   716.4 2180.78
   725.8 2188.13   735.2 2198.33     754  2207.8   772.8 2220.48   782.2 2224.61
#Mann= 3 , 0 , 0
       0     .06       0   471.5    .045       0   496.5      .1       0
Bank Sta=471.5,496.5
XS Rating Curve= 0 ,0
Exp/Cntr=0.3,0.1

Type RM Length L Ch R = 1 ,55507.6 ,411.8,386.5,361.2
XS GIS Cut Line= 3
     1923330.359      280662.445     1923570.235      281109.189
     1923615.059      281140.221
#Sta/Elev= 30
       0 2201.54    19.9 2182.09    49.7 2150.88    79.5  2120.8    89.5 2111.69
    99.4 2110.36   109.4  2096.7   119.3 2076.09   129.2  2053.5   139.2  2032.4
   149.1 2017.94   159.1 2011.04     169 2008.57   198.8  2007.1   247.2  2007.1
   272.2 2007.81   278.4 2008.81   288.3  2012.2   298.3 2016.69   308.2 2019.68
   328.1 2021.95   387.8 2024.59   397.7 2026.47   407.6 2029.45   417.6 2030.43
   437.5 2035.69   457.4 2039.36   477.2 2044.89   525.2 2054.02   561.6 2061.87
#Mann= 3 , 0 , 0
       0     .06       0   247.2    .045       0   272.2      .1       0
Bank Sta=247.2,272.2
XS Rating Curve= 0 ,0
Exp/Cntr=0.3,0.1

Type RM Length L Ch R = 1 ,55120.8 ,461.3,442.7,423.5
XS GIS Cut Line= 2
     1923031.824      281167.323     1923580.579      281257.454
#Sta/Elev= 30
       0 2118.19     9.9 2110.53    29.8 2099.28    39.7 2091.02    49.6 2080.71
   109.2 2038.99   119.2 2031.42   129.1 2020.74     149 2010.86   158.9 2007.31
   178.8 2003.38   188.7 2002.41   208.5 2001.95   218.3 2002.02   238.3 2002.47
   243.3 2003.26   258.2 2006.62     278 2012.45     288 2016.12   347.6 2019.78
   357.5 2021.24   367.4 2024.08   377.4 2025.85   446.9 2030.44   456.8 2032.62
   466.7 2035.77   516.4 2053.98   526.3 2058.65   536.2 2064.28   556.1 2070.72
#Mann= 3 , 0 , 0
       0      .1       0   218.3    .045       0   243.3      .1       0
Bank Sta=218.3,243.3
XS Rating Curve= 0 ,0
Exp/Cntr=0.3,0.1

Type RM Length L Ch R = 1 ,54678.1 ,424.6,408.3,392.5
XS GIS Cut Line= 3
      1923168.76      281720.072       1923370.1      281609.621
     1923921.933      281291.934
#Sta/Elev= 30
       0 2162.66      10 2151.34      30 2124.53    39.9 2113.09    79.9 2076.68
    89.9  2062.3    99.8 2054.26   119.8 2043.53   179.7 2000.01   189.7 1997.44
   217.1  1996.2   242.1  1996.2   259.5 1996.16   269.4  1998.5   289.3 2007.28
   299.3 2009.19   329.1 2008.69   339.1  2010.4   368.9 2023.52   398.8 2027.02
   408.7 2029.76   438.6 2041.79   458.5 2053.32   468.4  2057.1   617.7 2076.51
   667.4 2087.26   717.2 2102.01   816.6 2136.48   826.6 2142.71   866.4 2155.41
#Mann= 3 , 0 , 0
       0      .1       0   217.1    .045       0   242.1      .1       0
Bank Sta=217.1,242.1
XS Rating Curve= 0 ,0
Exp/Cntr=0.3,0.1

Type RM Length L Ch R = 1 ,54269.8 ,360.3,349.6,338.9
XS GIS Cut Line= 2
      1923559.64       282088.27     1923832.285       281560.88
#Sta/Elev= 30
       0 2142.79    19.8 2126.83    39.6 2107.22    49.5 2104.34    59.4 2098.33
   108.8 2059.14   138.5 2033.09   158.3 2024.47     188 2001.56   197.9 1996.88
   207.8 1995.32   238.8 1992.83   263.8 1991.39   296.8  1991.1   306.7 1993.46
   326.5 2004.99   336.4 2007.96   346.3 2008.21   366.1 2012.87     376  2017.7
   395.8 2029.21   405.7 2033.97   415.6 2037.89   435.4 2044.26   455.2 2048.64
     475 2051.29   514.5 2059.24   544.2 2066.49   554.1 2068.22   593.7 2072.76
#Mann= 3 , 0 , 0
       0      .1       0   238.8    .045       0   263.8      .1       0
Bank Sta=238.8,263.8
XS Rating Curve= 0 ,0
Exp/Cntr=0.3,0.1

Type RM Length L Ch R = 1 ,53919.7 ,490.5,464.2,437.8
XS GIS Cut Line= 2
     1923977.477      282269.121     1924039.166      281581.568
#Sta/Elev= 30
       0 2173.72      20 2145.35      30 2135.37      40 2132.76      60 2111.24
      90 2092.63     120 2069.52   130.1 2067.48   160.1 2036.75   190.1 2012.42
   220.1  1994.7   230.1 1994.06   250.1 1988.34   271.3  1988.2   296.3 1988.19
   340.2 1987.81   350.2 1988.78   370.2 1995.06   390.2 1996.81   400.2 2001.38
   410.2 2001.71   420.2  2005.9   450.2 2008.73   490.2 2024.37   500.2 2024.36
   550.2 2037.37   600.3    2041   650.3 2059.46   680.3 2073.12   690.3 2073.23
#Mann= 3 , 0 , 0
       0      .1       0   271.3    .045       0   296.3      .1       0
Bank Sta=271.3,296.3
XS Rating Curve= 0 ,0
Exp/Cntr=0.3,0.1

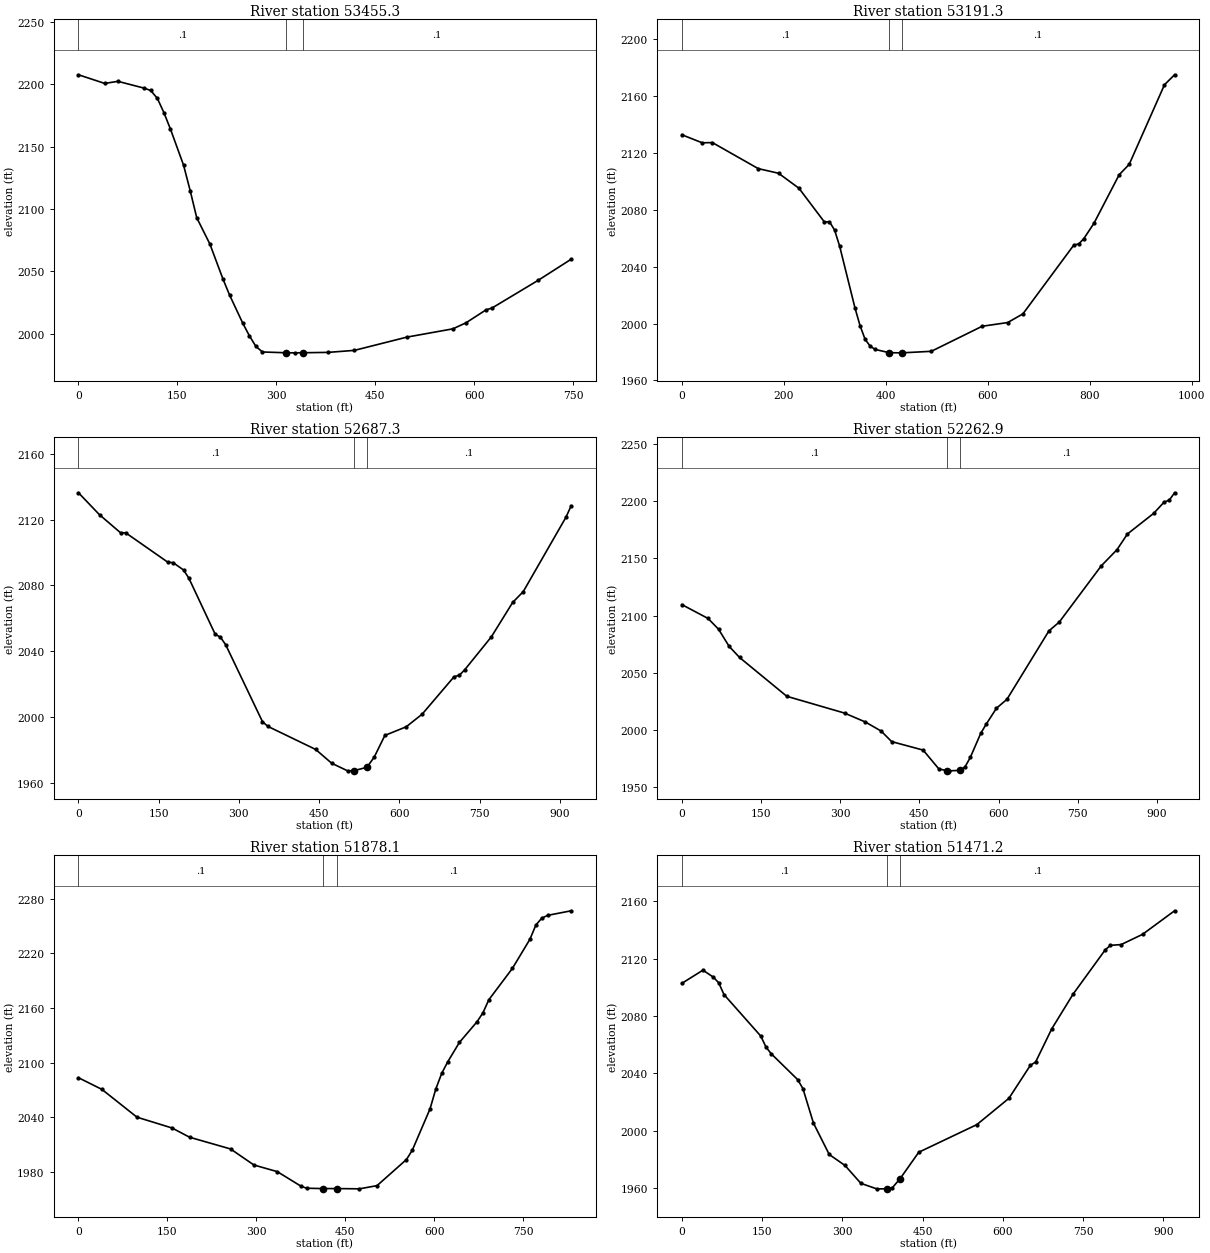
Type RM Length L Ch R = 1 ,53455.3 ,259,263.8,268.6
XS GIS Cut Line= 2
     1924663.077      282089.616     1924094.334      281605.705
#Sta/Elev= 30
       0 2207.65    39.8  2200.7    59.7 2202.39    99.6 2196.92   109.5 2195.04
   119.5 2188.72   129.4 2177.37   139.4 2164.04   159.3 2135.06   169.3 2114.64
   179.2 2092.99   199.1  2071.9     219 2043.74     229 2030.93   248.9 2008.43
   258.9 1998.37   268.8 1989.76   278.8 1985.25   315.2 1984.61   328.6 1984.56
   340.2 1984.63   378.4 1984.93   418.2 1986.54   497.8 1997.18   567.5 2003.82
   587.4 2008.67   617.3 2018.91   627.3 2020.68     697 2042.83   746.8  2059.7
#Mann= 3 , 0 , 0
       0      .1       0   315.2    .045       0   340.2      .1       0
Bank Sta=315.2,340.2
XS Rating Curve= 0 ,0
Exp/Cntr=0.3,0.1

Type RM Length L Ch R = 1 ,53191.3 ,466.5,503.5,540.7
XS GIS Cut Line= 3
     1924859.796      282005.675     1924373.624      281422.959
     1924390.865      281216.078
#Sta/Elev= 30
       0 2132.87    39.9 2127.21    59.9 2127.36   149.8 2109.05   189.7 2105.77
   229.7 2095.23   279.6 2071.49   289.6 2071.63   299.6 2065.82   309.6 2054.34
   339.5 2011.12   349.5 1998.58   359.5 1988.85   369.5 1984.06   379.4 1981.76
   406.9 1979.51   429.4  1979.4   431.9  1979.4   489.3 1980.47   589.1 1998.11
   639.1 2000.71     669 2006.82   768.8 2055.22   778.7 2056.09   788.6 2059.83
   808.3 2070.53   857.8 2104.72   877.5 2112.05   946.7 2168.07   966.5 2175.08
#Mann= 3 , 0 , 0
       0      .1       0   406.9    .045       0   431.9      .1       0
Bank Sta=406.9,431.9
XS Rating Curve= 0 ,0
Exp/Cntr=0.3,0.1

Type RM Length L Ch R = 1 ,52687.3 ,429.4,424.3,419.2
XS GIS Cut Line= 3
     1924917.952      282049.415      1924904.62      281705.697
     1925253.972      281246.107
#Sta/Elev= 30
       0 2136.25    39.3  2122.9    78.6 2111.97    88.4 2111.91   167.1 2094.06
   176.9 2093.82   196.6 2089.31   206.4 2084.36   255.5 2050.38   265.4 2048.51
   275.2 2043.96     344 1997.23   353.9 1994.39   443.5 1980.34   473.4 1971.97
   503.2 1967.35   514.3 1967.41   539.3 1969.48     553 1975.71   572.9 1988.87
   612.7 1994.09   642.6 2001.77   702.3 2024.53   712.2 2025.42   722.2 2028.75
     772 2048.76   811.8 2069.61   831.7 2076.26   911.3  2121.3   921.3  2128.4
#Mann= 3 , 0 , 0
       0      .1       0   514.3    .045       0   539.3      .1       0
Bank Sta=514.3,539.3
XS Rating Curve= 0 ,0
Exp/Cntr=0.3,0.1

Type RM Length L Ch R = 1 ,52262.9 ,364.2,384.5,407.2
XS GIS Cut Line= 3
     1925050.386      282097.517     1925266.663      281864.306
     1925539.057      281312.623
#Sta/Elev= 30
       0 2109.67    49.7 2097.55    69.6  2088.1    89.4 2073.28   109.3 2063.47
   198.8 2029.56   308.1  2014.9   347.8 2007.06   377.6 1999.14   397.4 1989.97
     457 1982.57   486.8 1966.13   501.8  1964.6   506.6 1964.44   526.8 1964.84
   536.4 1967.93   546.3  1976.1   566.2 1997.24   576.1 2004.93   595.9 2019.12
   615.8 2026.93   695.2 2086.65     715 2094.47   794.4 2143.51   824.2 2157.63
     844 2171.36   893.6 2189.34   913.5  2199.2   923.4 2200.99   933.3 2207.36
#Mann= 3 , 0 , 0
       0      .1       0   501.8    .045       0   526.8      .1       0
Bank Sta=501.8,526.8
XS Rating Curve= 0 ,0
Exp/Cntr=0.3,0.1

Type RM Length L Ch R = 1 ,51878.1 ,392.9,406.5,417.8
XS GIS Cut Line= 3
     1925104.712      282186.657     1925496.242      282023.516
     1925884.171      281900.677
#Sta/Elev= 30
       0 2083.45    39.5 2070.67    98.6 2040.17   157.8  2028.3   187.4 2018.16
   256.5 2005.29   295.9 1987.68   335.4 1980.38   374.8 1964.61   384.7 1962.19
   411.7 1961.81   436.7 1961.81   473.8 1961.52   503.6 1965.04   553.2  1993.7
   563.1 2003.98   592.9 2049.16   602.8 2071.28   612.7 2088.27   622.6 2100.67
   642.5 2122.19   672.3 2144.94   682.2 2154.69   692.1 2168.98   731.8 2203.36
   761.6 2235.59   771.5 2251.04   781.4 2258.56   791.4 2261.66   831.1 2266.68
#Mann= 3 , 0 , 0
       0      .1       0   411.7    .045       0   436.7      .1       0
Bank Sta=411.7,436.7
XS Rating Curve= 0 ,0
Exp/Cntr=0.3,0.1

Type RM Length L Ch R = 1 ,51471.2 ,497.8,455.3,412.8
XS GIS Cut Line= 3
     1925120.788      282385.985     1925649.394      282440.127
     1925941.352      282182.051
#Sta/Elev= 30
       0  2102.8    39.4    2112      59  2107.1    68.9 2103.19    78.7 2095.02
   147.6    2066   157.4 2058.27   167.3 2053.61   216.5 2035.66   226.3 2029.41
     246 2005.32   275.5 1983.45     305 1975.77   334.6 1963.33   364.1 1959.49
   383.2 1959.49   393.6 1960.32   408.2 1966.69   442.8 1985.01   551.4 2004.28
   611.3  2022.6   651.3 2045.57   661.3 2047.97   691.2 2070.94   731.2 2095.24
   791.2 2126.08   801.1 2129.31   821.1 2129.85   861.1 2136.97     921 2153.42
#Mann= 3 , 0 , 0
       0      .1       0   383.2    .045       0   408.2      .1       0
Bank Sta=383.2,408.2
XS Rating Curve= 0 ,0
Exp/Cntr=0.3,0.1