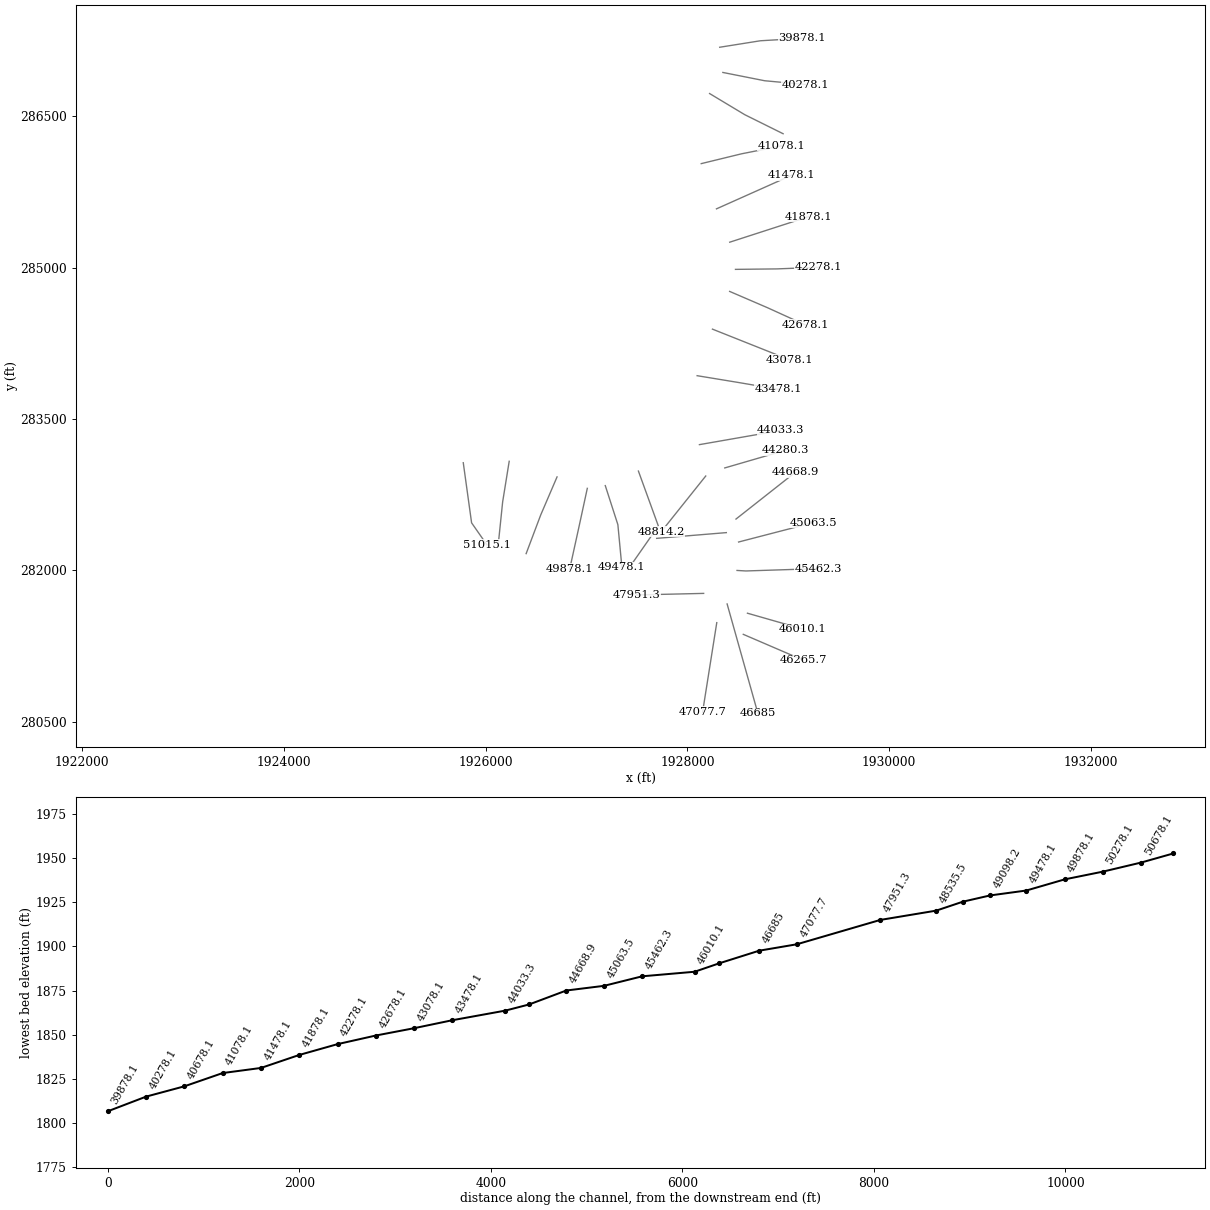
HEC-RAS study PnyCrk.prj: PnyCrk

--- PnyCrk.g01 (geometry) --- (continued)

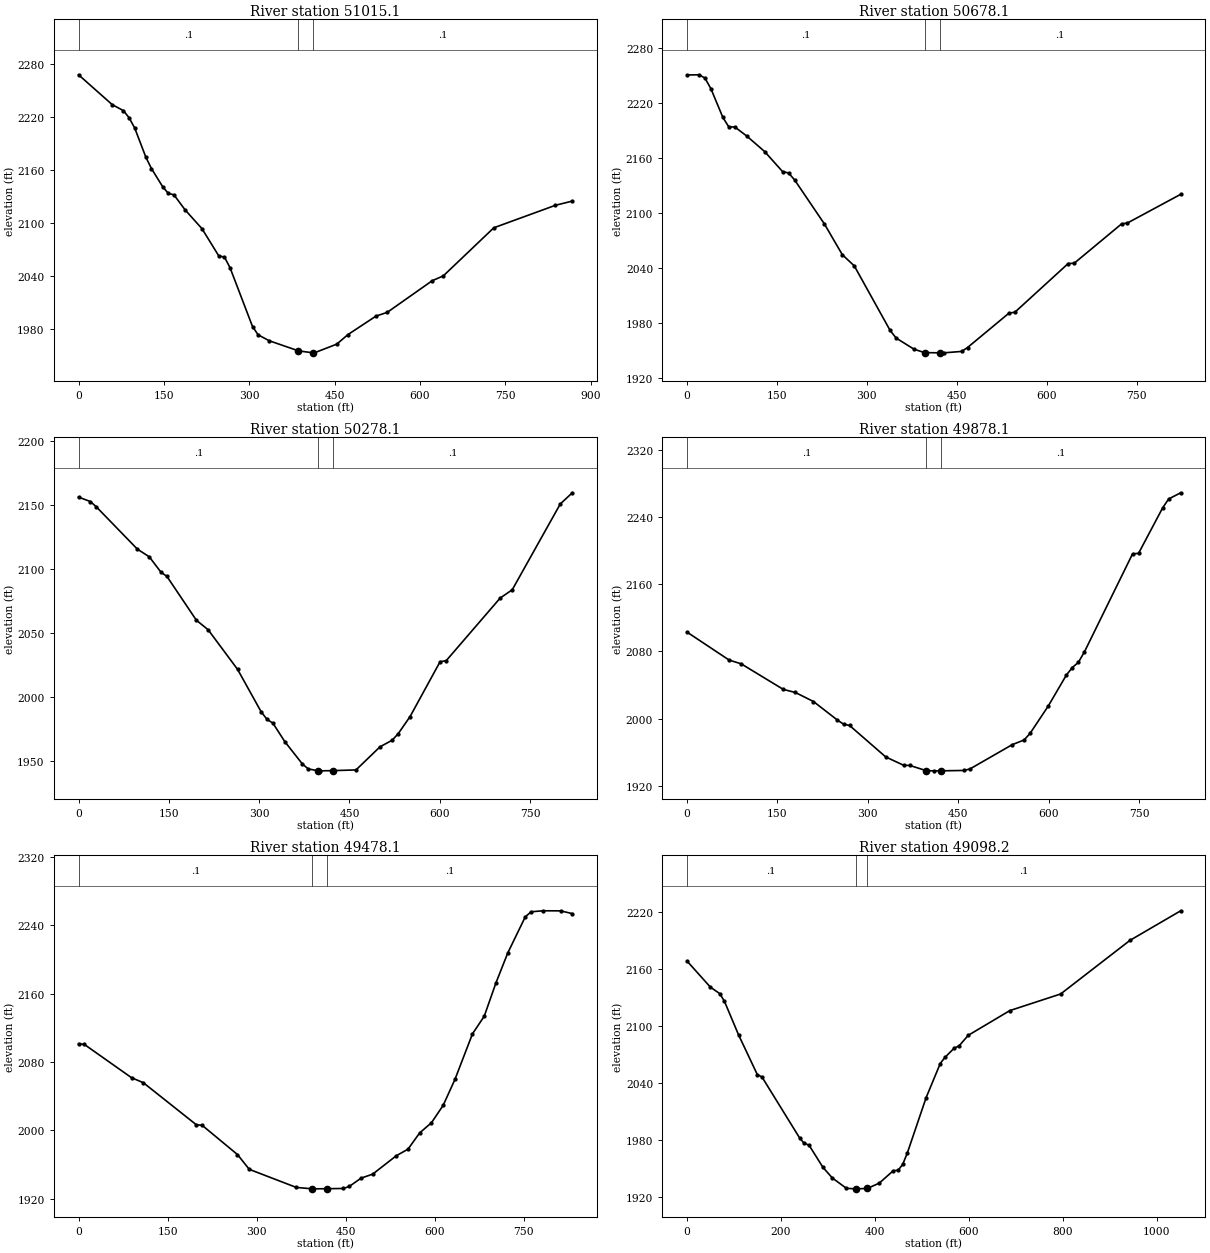
Type RM Length L Ch R = 1 ,51015.1 ,344.9,336.7,330.1
XS GIS Cut Line= 3
     1925777.185      283067.276     1925859.723      282471.159
     1926011.975      282252.935
#Sta/Elev= 30
       0 2267.51    59.2 2233.72    78.9  2226.9    88.8 2218.91    98.7 2207.27
   118.4 2174.08   128.2 2161.27     148 2140.65   157.8 2133.24   167.7 2131.58
   187.4 2114.49     217 2093.25   246.6 2062.32   256.5 2061.14   266.4 2048.89
   305.8 1982.48   315.7 1973.05   335.4 1966.33   386.6 1954.96   411.6 1952.76
   414.4 1952.71   453.8 1962.53   473.6  1973.4   522.9 1994.34   542.6 1998.53
   621.5 2034.32   641.2 2039.86   729.9 2094.28   838.3 2119.77   867.9 2124.52
#Mann= 3 , 0 , 0
       0      .1       0   386.6    .045       0   411.6      .1       0
Bank Sta=386.6,411.6
XS Rating Curve= 0 ,0
Exp/Cntr=0.3,0.1

Type RM Length L Ch R = 1 ,50678.1 ,406.4,399.6,392.5
XS GIS Cut Line= 3
      1926232.59      283081.365     1926167.563      282678.001
     1926124.923      282265.438
#Sta/Elev= 30
       0 2250.57    19.9  2250.8    29.9 2247.32    39.9 2235.66    59.8 2204.41
    69.8 2193.91    79.7 2193.89    99.6 2184.06   129.6 2167.03   159.4 2145.24
   169.4 2143.72   179.4 2136.22   229.2  2088.1   259.1 2054.52     279 2042.38
   338.8 1971.91   348.8 1963.65   378.7 1951.47   396.1 1947.78   421.1 1947.57
   428.3 1947.54     458 1949.08   467.8 1953.32     537 1990.87   546.8 1991.85
   635.7 2044.97   645.6  2045.2   724.6 2088.13   734.5 2089.17   823.3 2120.45
#Mann= 3 , 0 , 0
       0      .1       0   396.1    .045       0   421.1      .1       0
Bank Sta=396.1,421.1
XS Rating Curve= 0 ,0
Exp/Cntr=0.3,0.1

Type RM Length L Ch R = 1 ,50278.1 ,394.4,399.7,403.8
XS GIS Cut Line= 3
     1926707.021      282926.593     1926544.913      282548.937
     1926400.637       282165.99
#Sta/Elev= 30
       0 2155.98    19.6 2152.54    29.4 2148.45    97.8 2115.35   117.4 2109.44
     137 2097.35   146.8  2094.1   195.7 2059.93   215.3 2052.47   264.2 2021.54
   303.3 1988.48   313.1 1982.55   322.9 1979.58   342.5 1965.27   371.8 1947.76
   381.6 1943.89   398.5  1942.4   401.2 1942.39   423.5 1942.56   460.9 1943.11
   500.8 1961.15   520.8 1966.24   530.8 1971.25   550.7 1984.74   600.6 2027.58
   610.6 2028.28   700.4 2077.23   720.4 2083.67   800.2 2150.62   820.2 2159.36
#Mann= 3 , 0 , 0
       0      .1       0   398.5    .045       0   423.5      .1       0
Bank Sta=398.5,423.5
XS Rating Curve= 0 ,0
Exp/Cntr=0.3,0.1

Type RM Length L Ch R = 1 ,49878.1 ,385.1,399.5,407.9
XS GIS Cut Line= 3
     1927006.997      282813.128     1926920.336      282412.897
     1926832.378      282012.959
#Sta/Elev= 30
       0 2103.07    69.9 2069.76    89.9 2065.31   159.8 2034.86   179.8 2031.19
   209.8 2020.47   249.7  1998.3   259.7 1993.56   269.7 1991.96   329.6 1954.58
   359.6 1944.55   369.6 1944.44     397 1938.18   409.5    1938     422 1938.02
   459.4 1938.45   469.4 1940.24   539.4 1969.09   559.3 1974.74   569.3 1982.73
   599.3  2015.1   629.2 2051.76   639.2 2060.89   649.2 2067.01   659.2 2079.37
   739.1 2196.07   749.1 2196.72     789 2250.77     799 2261.38     819 2268.72
#Mann= 3 , 0 , 0
       0      .1       0     397    .045       0     422      .1       0
Bank Sta=397,422
XS Rating Curve= 0 ,0
Exp/Cntr=0.3,0.1

Type RM Length L Ch R = 1 ,49478.1 ,378.7,379.7,386.9
XS GIS Cut Line= 3
     1927185.211      282840.146     1927310.065      282453.062
     1927350.184      282029.719
#Sta/Elev= 30
       0 2101.53     9.9 2100.66    89.3 2061.76   109.1 2055.95   198.4 2006.73
   208.3 2006.05   267.8 1971.82   287.7 1954.52     367 1933.34   394.2  1931.7
   419.2 1931.86   446.3 1932.14   456.2 1934.53     476 1944.17   495.7 1948.94
   535.3 1970.38   555.1  1978.1   574.8 1997.17   594.6 2009.01   614.4 2029.42
   634.2 2059.71   663.8 2113.14   683.6 2133.73   703.4 2172.88   723.2  2207.7
   752.8 2250.11   762.7 2255.95   782.5 2257.13   812.2 2257.05     832 2253.81
#Mann= 3 , 0 , 0
       0      .1       0   394.2    .045       0   419.2      .1       0
Bank Sta=394.2,419.2
XS Rating Curve= 0 ,0
Exp/Cntr=0.3,0.1

Type RM Length L Ch R = 1 ,49098.2 ,311.8,283.5,255.3
XS GIS Cut Line= 3
     1927513.671       282984.37     1927711.312      282440.127
      1927441.17      282053.207
#Sta/Elev= 30
       0  2168.3    49.9 2140.83    69.9 2133.98    79.9 2125.79   109.8  2090.7
   149.8 2048.88   159.7 2046.39   239.6  1982.5   249.6 1976.65   259.6 1974.95
   289.5 1951.42   309.5 1940.27   339.4 1929.44   358.8  1928.9   383.8  1929.3
   409.3 1934.89   439.3 1948.04   449.2  1948.3   459.2 1954.58   469.2 1966.82
   509.1 2024.81   539.1 2060.59   549.1 2067.02     569 2076.84     579 2079.01
   598.7 2090.21   687.2 2116.18   795.3 2133.63   942.8 2189.94  1050.9 2221.05
#Mann= 3 , 0 , 0
       0      .1       0   358.8    .045       0   383.8      .1       0
Bank Sta=358.8,383.8
XS Rating Curve= 0 ,0
Exp/Cntr=0.3,0.1

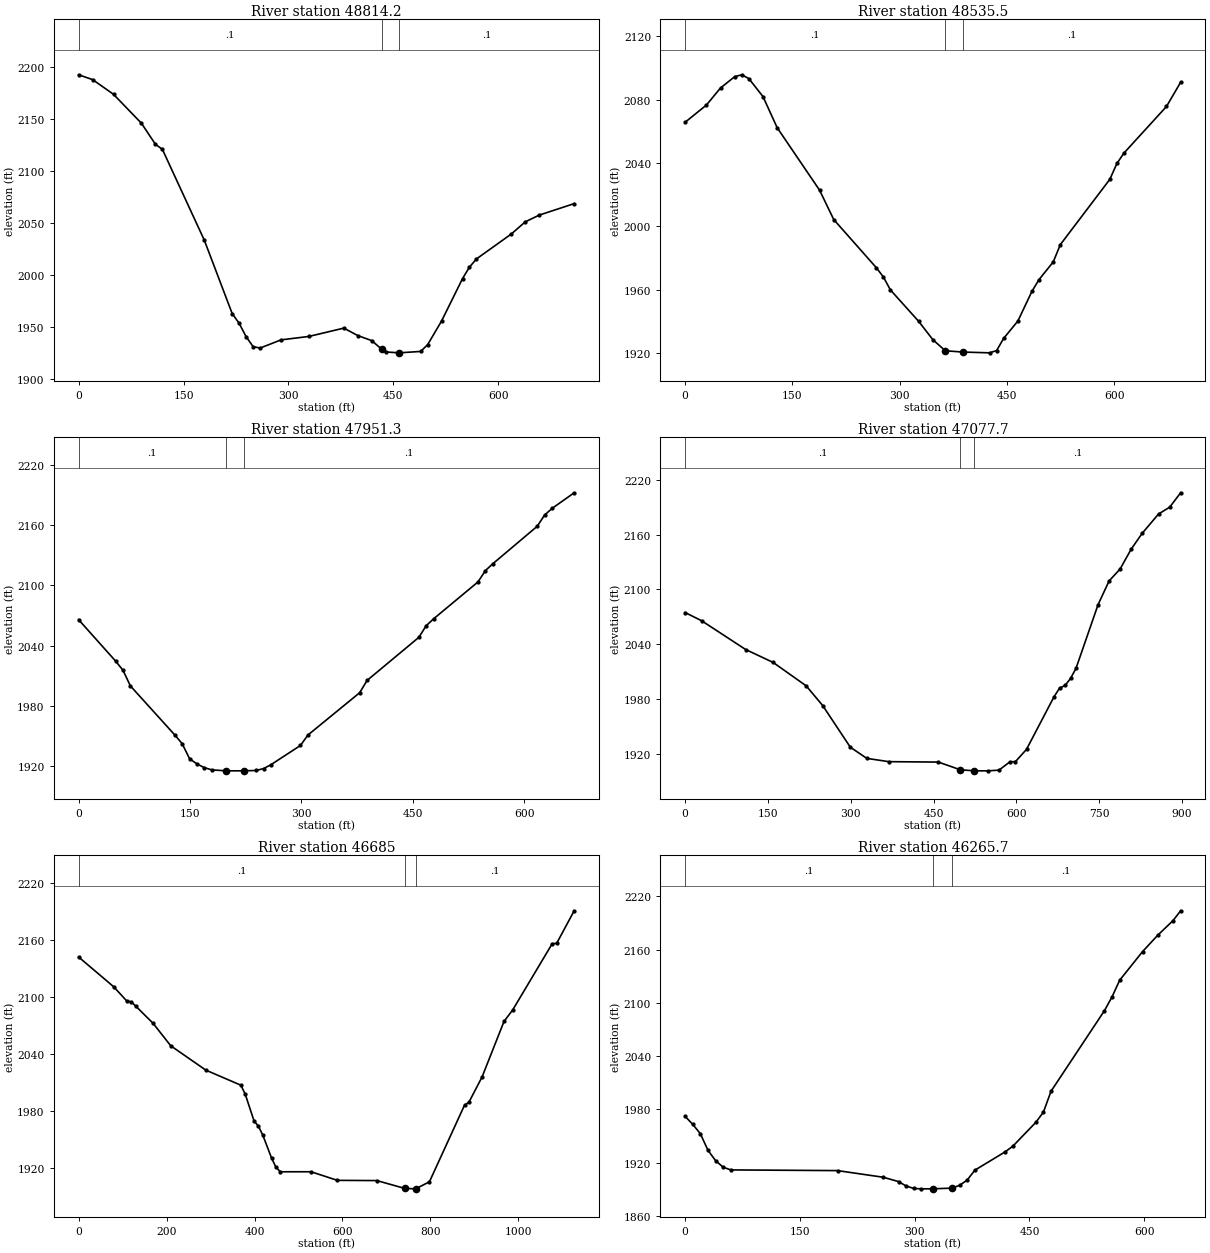
Type RM Length L Ch R = 1 ,48814.2 ,300.9,278.5,256.1
XS GIS Cut Line= 2
     1928181.106      282935.349     1927738.897      282381.941
#Sta/Elev= 30
       0 2192.17      20 2187.52    49.9 2173.41    89.8 2145.66   109.8 2125.45
   119.7 2120.66   179.6 2033.56   219.5 1963.06   229.5  1953.7   239.4 1940.88
   249.4 1931.34   259.4 1929.96   289.3  1937.8   329.2 1941.11   379.1 1949.09
   399.1 1941.93     419  1937.1   433.1 1928.93     439 1926.22   458.1 1925.37
   488.9 1926.71   498.9 1933.16   518.8 1955.87   548.8  1996.6   558.7  2007.6
   568.7 2015.47   618.6 2039.42   638.5 2051.08   658.5 2057.54   708.4 2068.54
#Mann= 3 , 0 , 0
       0      .1       0   433.1    .045       0   458.1      .1       0
#XS Ineff= 2 , 0
          378.63 1948.97
Permanent Ineff=
       F       F
Bank Sta=433.1,458.1
XS Rating Curve= 0 ,0
Exp/Cntr=0.3,0.1

Type RM Length L Ch R = 1 ,48535.5 ,585,583.4,581.7
XS GIS Cut Line= 2
     1928385.401      282374.183     1927694.934      282317.291
#Sta/Elev= 30
       0 2065.74    29.7 2076.56    49.5 2087.37    69.3  2094.5    79.2  2095.7
    89.1 2093.31   108.9 2081.94   128.7 2062.33     188 2022.91   207.8 2004.39
   267.2 1974.08   277.1 1968.23     287 1960.01   326.6 1940.14   346.4 1928.59
   363.8  1921.6   388.8 1920.79   425.6  1920.3   435.5 1921.72   445.4 1929.45
   465.2 1940.33     485 1959.18   494.9 1966.54   514.7 1977.66   524.6 1988.56
   593.8 2029.75   603.7 2039.76   613.6 2046.34     673  2075.7   692.8 2090.96
#Mann= 3 , 0 , 0
       0      .1       0   363.8    .045       0   388.8      .1       0
Bank Sta=363.8,388.8
XS Rating Curve= 0 ,0
Exp/Cntr=0.3,0.1

Type RM Length L Ch R = 1 ,47951.3 ,834.5,872.9,911.3
XS GIS Cut Line= 2
     1928160.418      281771.641     1927493.225      281756.125
#Sta/Elev= 30
       0 2065.73    49.8 2024.45    59.8 2015.25    69.7 1999.72   129.5 1950.82
   139.4 1942.16   149.4 1927.17   159.4 1921.86   169.3 1918.24   179.3 1916.01
   198.1 1915.06   199.2 1915.04   223.1 1915.08   239.1 1915.39     249 1917.28
     259 1921.14   298.8 1940.37   308.8 1950.72   378.5 1992.93   388.5 2005.18
   458.2 2048.13   468.2 2059.81   478.1 2066.61   537.9 2103.41   547.8 2114.64
   557.8  2121.5   617.6 2158.85   627.5 2169.98   637.5  2176.6   667.4 2192.27
#Mann= 3 , 0 , 0
       0      .1       0   198.1    .045       0   223.1      .1       0
Bank Sta=198.1,223.1
XS Rating Curve= 0 ,0
Exp/Cntr=0.3,0.1

Type RM Length L Ch R = 1 ,47077.7 ,380.6,392.5,404.4
XS GIS Cut Line= 2
     1928290.581      281481.576     1928150.074      280595.002
#Sta/Elev= 30
       0 2074.61    29.9 2065.62   109.7 2034.11   159.6  2019.9   219.4 1994.27
   249.3  1972.7   299.2 1927.18   329.1 1914.88     369 1911.28   458.8 1910.83
   498.5 1902.38   523.5 1901.26   548.6 1901.23   568.5 1901.99   588.4  1911.1
   598.4 1911.34   618.4 1924.76   668.2 1982.27   678.2 1991.74   688.2 1994.74
   698.2 2002.41   708.1 2013.52     748 2083.17     768 2109.21   787.9 2122.23
   807.9 2143.89   827.8 2161.25   857.7 2182.59   877.7 2189.94   897.6 2205.76
#Mann= 3 , 0 , 0
       0      .1       0   498.5    .045       0   523.5      .1       0
Bank Sta=498.5,523.5
XS Rating Curve= 0 ,0
Exp/Cntr=0.3,0.1

Type RM Length L Ch R = 1 ,46685   ,394.1,418.7,443.3
XS GIS Cut Line= 2
      1928393.19      281666.941      1928698.31      280582.072
#Sta/Elev= 30
       0 2141.58    79.8 2110.27   109.7  2095.2   119.7 2094.44   129.6 2090.04
   169.5 2071.74   209.4 2048.21   289.2 2022.57     369 2006.69     379 1997.12
   398.9 1969.08   408.9 1963.54   418.9  1954.1   438.8 1929.98   448.8  1920.3
   458.8 1915.56   528.6 1915.59   588.4 1906.54   678.2  1906.3   741.5 1898.07
   766.5 1897.61   797.8 1905.01   877.6 1985.65   887.6 1988.74   917.5 2015.33
   967.4 2073.76   987.3 2085.99  1077.1 2155.67  1087.1 2155.91    1127 2190.26
#Mann= 3 , 0 , 0
       0      .1       0   741.5    .045       0   766.5      .1       0
Bank Sta=741.5,766.5
XS Rating Curve= 0 ,0
Exp/Cntr=0.3,0.1

Type RM Length L Ch R = 1 ,46265.7 ,252,255.6,259.1
XS GIS Cut Line= 2
     1928553.492      281365.636     1929148.277       281109.62
#Sta/Elev= 30
       0  1972.1      10 1963.07    19.9 1952.58    29.9 1933.84    39.8 1922.25
    49.8 1914.73    59.8 1911.76   199.2 1910.98     259 1903.48   278.9  1898.6
   288.9 1893.62   298.9 1890.84   308.8 1890.44   323.4 1890.47   348.4 1891.21
   358.6 1894.36   368.6 1900.34   378.6 1911.45   418.4 1932.21   428.4  1938.6
   458.3 1965.36   468.2 1976.87   478.2 2000.45   547.9 2091.08   557.9  2106.7
   567.8 2125.39   597.7 2157.62   617.7  2176.2   637.6 2192.63   647.5 2203.64
#Mann= 3 , 0 , 0
       0      .1       0   323.4    .045       0   348.4      .1       0
Bank Sta=323.4,348.4
XS Rating Curve= 0 ,0
Exp/Cntr=0.3,0.1

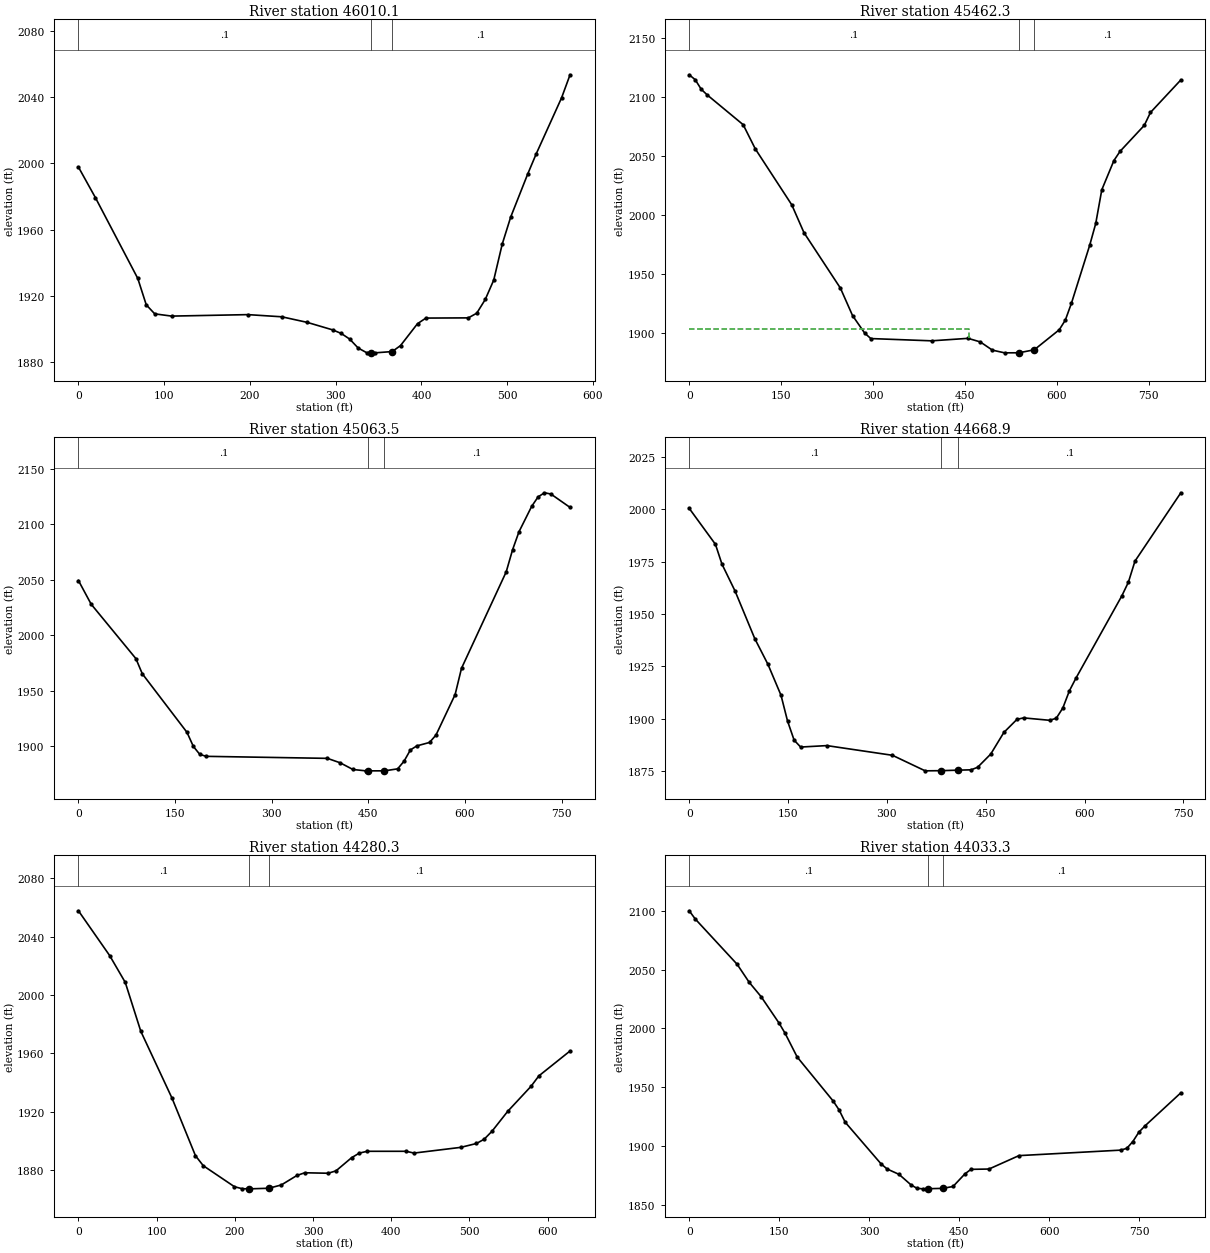
Type RM Length L Ch R = 1 ,46010.1 ,538.9,547.5,556.1
XS GIS Cut Line= 2
     1928594.869      281575.103     1929146.022      281417.421
#Sta/Elev= 30
       0 1997.74    19.8 1979.29    69.2 1930.57    79.1 1914.62      89 1909.19
   108.7 1907.84   197.7 1908.73   237.2 1907.42   266.9 1904.04   296.5 1899.52
   306.4  1897.4   316.3 1893.98   326.2 1888.59     336  1885.8   340.9 1885.74
   345.9 1885.68   365.9 1886.45   375.6 1890.06   395.4 1903.26   405.2 1906.65
   454.7 1906.77   464.5  1909.6   474.4 1917.86   484.3 1929.57   494.2 1951.26
   504.1 1967.61   523.8 1993.39   533.7 2005.55   563.4 2039.49   573.3 2053.41
#Mann= 3 , 0 , 0
       0      .1       0   340.9    .045       0   365.9      .1       0
Bank Sta=340.9,365.9
XS Rating Curve= 0 ,0
Exp/Cntr=0.3,0.1

Type RM Length L Ch R = 1 ,45462.3 ,392.4,398.5,404.6
XS GIS Cut Line= 3
     1928491.428       281999.21     1928579.353      281994.038
     1929293.259      282017.169
#Sta/Elev= 30
       0 2118.96     9.8 2114.78    19.6 2106.68    29.4 2101.86    88.1  2076.6
   107.9 2056.06   167.4 2008.63   187.3 1985.03   246.8 1937.97   266.6 1914.69
   286.5 1899.78   296.4 1895.21   395.6 1893.29   455.1 1895.39     475 1892.38
   494.8  1885.4   514.7  1883.1   538.2 1883.15   563.2 1885.69     604 1902.68
   613.9 1910.88   623.8  1925.1   653.6 1974.26   663.5 1992.81   673.4 2021.41
   693.2 2046.24   703.2 2054.01   742.8 2076.08   752.8 2086.97   802.4 2114.58
#Mann= 3 , 0 , 0
       0      .1       0   538.2    .045       0   563.2      .1       0
#XS Ineff= 2 , 0
          456.49 1902.91
Permanent Ineff=
       F       F
Bank Sta=538.2,563.2
XS Rating Curve= 0 ,0
Exp/Cntr=0.3,0.1

Type RM Length L Ch R = 1 ,45063.5 ,383,394.3,405.7
XS GIS Cut Line= 2
     1928506.944      282281.086     1929245.552      282472.752
#Sta/Elev= 30
       0 2049.33    19.8 2027.94    89.2  1978.9    99.1 1965.27   168.5 1912.41
   178.4  1899.7   188.3 1892.58   198.2 1890.78   386.5 1888.95   406.3 1884.94
   426.1 1878.91     446  1877.7     450  1877.7     475  1877.7   495.5  1879.5
   505.4 1886.38   515.3 1896.55   525.2 1900.18     545  1903.3     555 1909.98
   584.7  1946.5   594.6 1970.16     664 2057.16   673.9 2077.11   683.8 2093.26
   703.6 2116.29   713.5 2124.76   723.4 2128.46   733.3 2127.35   763.1 2115.25
#Mann= 3 , 0 , 0
       0      .1       0     450    .045       0     475      .1       0
Bank Sta=450,475
XS Rating Curve= 0 ,0
Exp/Cntr=0.3,0.1

Type RM Length L Ch R = 1 ,44668.9 ,398.8,388.3,377.7
XS GIS Cut Line= 2
     1928481.084      282508.656     1929067.135      282970.411
#Sta/Elev= 30
       0 2000.49    39.8 1983.31    49.7 1973.84    69.6 1960.96    99.5 1938.23
   119.4    1926   139.3 1911.18   149.2 1898.88   159.2 1889.72   169.1 1886.42
   208.9 1887.11   308.4 1882.48   358.1 1875.05   382.6 1875.13   407.6 1875.37
   427.8 1875.54   437.7 1876.75   457.6 1883.06   477.5 1893.39   497.4 1899.65
   507.4 1900.36   547.1  1899.2   557.1  1900.2     567 1905.07     577 1913.31
   586.9 1919.34   656.6 1958.69   666.5  1965.2   676.5 1975.28   746.1 2007.94
#Mann= 3 , 0 , 0
       0      .1       0   382.6    .045       0   407.6      .1       0
Bank Sta=382.6,407.6
XS Rating Curve= 0 ,0
Exp/Cntr=0.3,0.1

Type RM Length L Ch R = 1 ,44280.3 ,250,246.9,243.9
XS GIS Cut Line= 2
     1928369.885      283015.516     1928973.701      283191.194
#Sta/Elev= 30
       0 2057.63    39.9 2026.98    59.9 2008.56    79.8 1975.03   119.8 1929.15
   149.7 1889.83   159.7 1882.99   199.6 1868.59   209.6 1867.22   218.5 1867.16
   219.6 1867.15   243.5 1867.55   259.5 1869.81   279.5 1876.32   289.5 1878.16
   319.4 1877.83   329.4 1879.46   349.4 1888.49   359.3 1891.64   369.3 1892.87
   419.2 1892.87   429.2 1891.65   489.1 1895.57   509.1 1898.22     519 1901.16
     529 1906.62     549  1920.2   578.9 1937.39   588.9 1944.52   628.8 1961.59
#Mann= 3 , 0 , 0
       0      .1       0   218.5    .045       0   243.5      .1       0
Bank Sta=218.5,243.5
XS Rating Curve= 0 ,0
Exp/Cntr=0.3,0.1

Type RM Length L Ch R = 1 ,44033.3 ,564.1,554.8,545.4
XS GIS Cut Line= 3
     1928118.637      283246.485     1928522.026      283316.969
     1928925.414      283387.453
#Sta/Elev= 30
       0 2100.01      10 2093.06    79.9  2054.5    99.9 2039.22   119.8    2027
   149.8 2004.45   159.8 1995.82   179.8 1975.77   239.7 1938.37   249.7 1930.75
   259.7  1920.4   319.6  1884.9   329.6 1880.58   349.6 1875.96   369.6    1867
   379.5 1864.12   389.5 1863.68   397.4 1863.78   422.4 1864.08   439.5 1865.68
   459.4 1876.44   469.4 1880.25   499.4 1880.51   549.3 1891.91   719.1 1896.59
   729.1 1898.14   739.1 1903.91   749.1 1911.84   759.1  1917.1     819 1945.29
#Mann= 3 , 0 , 0
       0      .1       0   397.4    .045       0   422.4      .1       0
Bank Sta=397.4,422.4
XS Rating Curve= 0 ,0
Exp/Cntr=0.3,0.1

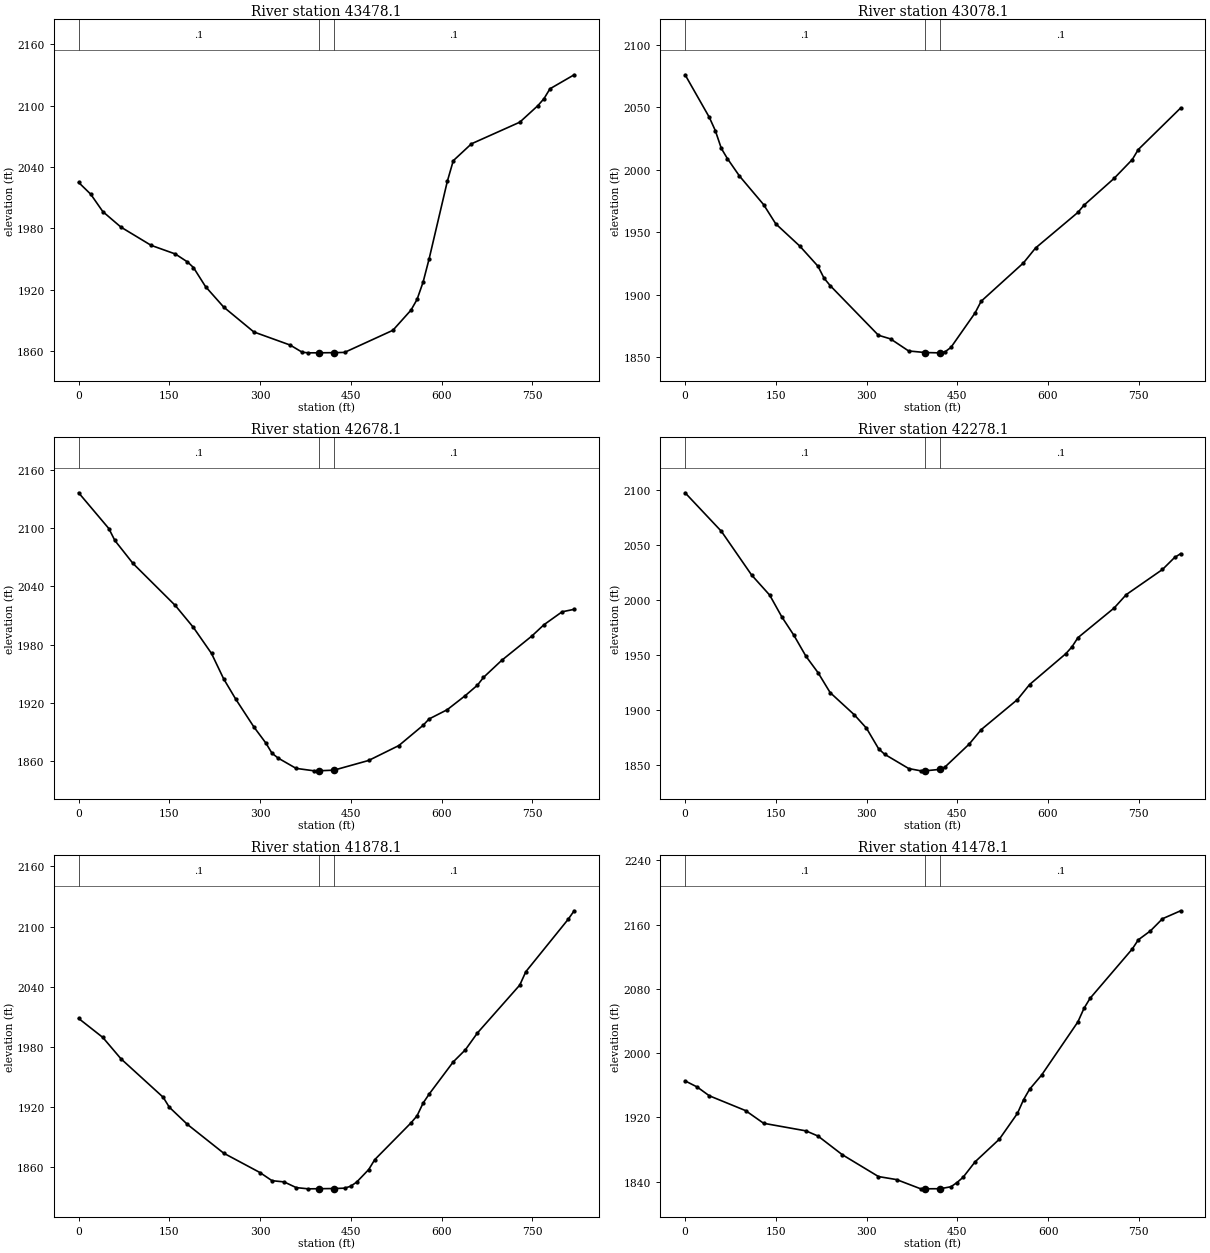
Type RM Length L Ch R = 1 ,43478.1 ,405.4,399.5,393.7
XS GIS Cut Line= 3
      1928095.79      283930.036     1928499.855      283863.585
     1928903.559      283794.853
#Sta/Elev= 30
       0 2024.96      20 2013.43      40  1996.4    69.9 1981.25   119.8 1963.41
   159.8 1954.95   179.8  1947.2   189.8  1941.7   209.7 1923.06   239.7 1903.03
   289.6 1878.64   349.6 1865.83   369.5 1858.81   379.5 1858.22     397 1858.25
     422 1858.39   439.5 1858.65   519.4 1880.29   549.3 1900.02   559.3 1910.43
   569.3 1927.42   579.3 1950.25   609.3 2025.93   619.2 2046.24   649.2 2062.75
   729.1 2083.91   759.1 2100.15   769.1 2106.93     779 2116.59     819  2130.3
#Mann= 3 , 0 , 0
       0      .1       0     397    .045       0     422      .1       0
Bank Sta=397,422
XS Rating Curve= 0 ,0
Exp/Cntr=0.3,0.1

Type RM Length L Ch R = 1 ,43078.1 ,400.6,399.8,398.5
XS GIS Cut Line= 3
      1928247.72      284391.634     1928628.125      284240.165
     1929008.831      284088.679
#Sta/Elev= 30
       0 2075.97      40 2041.99    49.9 2031.42    59.9 2017.11    69.9 2008.99
    89.9 1995.03   129.8 1972.18   149.8 1956.87   189.8 1938.94   219.7 1922.92
   229.7 1913.39   239.7 1907.52   319.6 1867.76   339.6 1864.85   369.5 1855.21
     397 1853.93   419.4  1853.7     422 1853.89   429.4 1854.42   439.4    1858
   479.4 1885.62   489.4 1894.92   559.4 1925.61   579.3 1937.48   649.3 1965.93
   659.3 1971.66   709.3  1993.2   739.2 2008.17   749.2 2016.22   819.2 2049.42
#Mann= 3 , 0 , 0
       0      .1       0     397    .045       0     422      .1       0
Bank Sta=397,422
XS Rating Curve= 0 ,0
Exp/Cntr=0.3,0.1

Type RM Length L Ch R = 1 ,42678.1 ,388,399.5,412.3
XS GIS Cut Line= 3
     1928418.152      284765.656     1928794.244      284603.709
     1929167.095      284433.966
#Sta/Elev= 30
       0 2136.78    49.9 2099.85    59.9 2087.49    89.9 2063.76   159.8 2020.35
   189.8 1997.64   219.7 1970.77   239.7 1944.63   259.7 1923.63   289.6    1895
   309.6 1878.19   319.6  1867.8   329.6 1862.82   359.5 1852.09   389.5 1849.55
     397  1849.6     422 1850.24   479.4 1860.26   529.4 1875.68   569.4 1896.54
   579.3 1903.11   609.3 1912.69   639.3  1927.3   659.3 1938.06   669.3 1946.07
   699.2 1963.58   749.2 1988.78   769.2 2000.44   799.2 2013.82   819.2 2016.41
#Mann= 3 , 0 , 0
       0      .1       0     397    .045       0     422      .1       0
Bank Sta=397,422
XS Rating Curve= 0 ,0
Exp/Cntr=0.3,0.1

Type RM Length L Ch R = 1 ,42278.1 ,391.5,399.8,407.3
XS GIS Cut Line= 3
     1928476.055      284984.136     1928885.711      284988.833
     1929294.874      285004.626
#Sta/Elev= 30
       0 2097.85      60 2062.76   109.9 2023.02   139.9 2004.63   159.9 1984.86
   179.9 1968.06   199.8 1948.99   219.8 1934.05   239.8 1915.91   279.8 1895.68
   299.8 1883.54   319.8 1864.89   329.7 1859.82   369.7 1846.76   389.7 1844.68
   397.2  1844.7   422.2 1846.08   429.7  1848.2   469.6 1869.01   489.6 1882.25
   549.5 1909.61   569.5 1923.24   629.4 1951.34   639.4 1957.45   649.4 1965.92
   709.3 1992.95   729.3 2005.13   789.2 2028.03   809.2 2038.94   819.2  2042.4
#Mann= 3 , 0 , 0
       0      .1       0   397.2    .045       0   422.2      .1       0
Bank Sta=397.2,422.2
XS Rating Curve= 0 ,0
Exp/Cntr=0.3,0.1

Type RM Length L Ch R = 1 ,41878.1 ,396.9,399.9,402.8
XS GIS Cut Line= 3
     1928418.987      285253.594     1928808.599      285379.661
     1929198.211      285505.727
#Sta/Elev= 30
       0 2008.37      40 1989.42    69.9 1968.19   139.8 1929.78   149.8 1919.96
   179.8 1902.75   239.7 1874.11   299.6 1854.81   319.6 1846.68   339.6 1845.46
   359.6 1839.78   379.5 1838.55     397 1838.68     422 1838.86   439.5 1839.21
   449.4  1841.1   459.4 1845.19   479.4 1857.78   489.4 1867.64   549.3 1904.27
   559.3 1911.29   569.3 1923.99   579.3 1932.98   619.2 1965.12   639.2 1977.14
   659.2 1993.97   729.1 2041.65   739.1 2054.96     809 2107.12     819 2115.67
#Mann= 3 , 0 , 0
       0      .1       0     397    .045       0     422      .1       0
Bank Sta=397,422
XS Rating Curve= 0 ,0
Exp/Cntr=0.3,0.1

Type RM Length L Ch R = 1 ,41478.1 ,404.9,399.8,393.7
XS GIS Cut Line= 3
     1928287.608      285584.162     1928661.467      285751.255
     1929035.325      285918.348
#Sta/Elev= 30
       0 1965.57      20 1957.95      40 1947.03    99.9  1928.6   129.8 1912.78
   199.8 1903.34   219.7  1896.9   259.7 1873.74   319.6 1846.48   349.6 1842.69
   389.5 1831.19     397 1831.24     422 1831.35   439.5 1833.82   449.4 1839.04
   459.4 1845.55   479.4 1864.91   519.4 1893.02   549.3 1925.16   559.3 1942.02
   569.3  1955.1   589.3 1972.89   649.2 2039.02   659.2 2055.76   669.2 2068.24
   739.1 2129.81   749.1 2141.21   769.1  2152.3     789 2167.42     819 2177.32
#Mann= 3 , 0 , 0
       0      .1       0     397    .045       0     422      .1       0
Bank Sta=397,422
XS Rating Curve= 0 ,0
Exp/Cntr=0.3,0.1

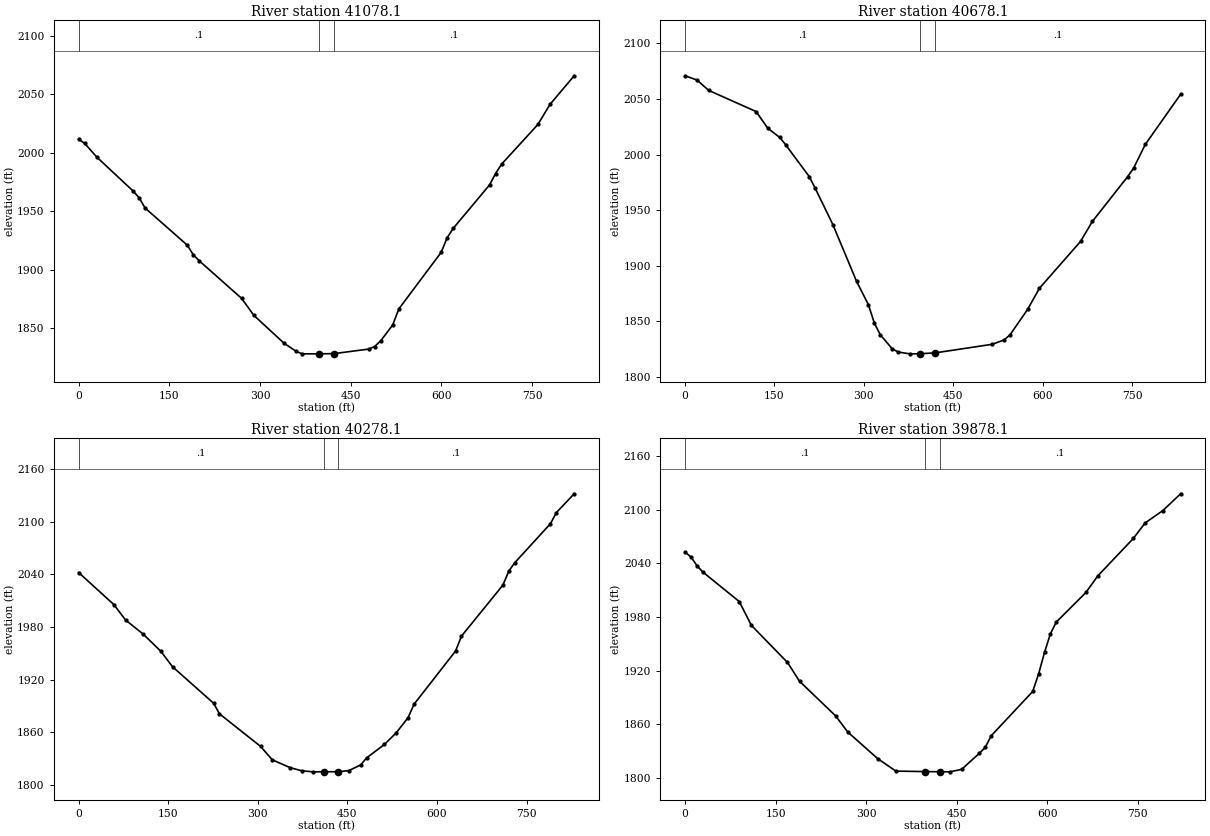
Type RM Length L Ch R = 1 ,41078.1 ,421,399.6,381.5
XS GIS Cut Line= 3
     1928136.546      286032.522     1928534.318      286129.484
       1928936.4      286209.448
#Sta/Elev= 30
       0 2011.65      10 2008.13      30 1996.42    89.9  1967.5    99.9 1961.78
   109.8 1952.96   179.7 1921.14   189.7 1912.89   199.7 1907.68   269.6 1875.64
   289.6 1861.26   339.5 1837.43   359.5 1830.49   369.5  1828.3   396.9 1828.33
   421.9 1828.46   479.4 1832.35   489.4 1834.52   499.4 1839.38   519.4 1853.01
   529.4 1866.64   599.4 1914.96   609.4 1927.54   619.4 1935.52   679.4 1972.59
   689.4 1982.37   699.4  1990.4   759.4 2024.27   779.4 2041.45   819.4  2065.9
#Mann= 3 , 0 , 0
       0      .1       0   396.9    .045       0   421.9      .1       0
Bank Sta=396.9,421.9
XS Rating Curve= 0 ,0
Exp/Cntr=0.3,0.1

Type RM Length L Ch R = 1 ,40678.1 ,390,399.5,409.6
XS GIS Cut Line= 3
     1928219.335      286727.427     1928568.011      286517.832
     1928948.351      286328.928
#Sta/Elev= 30
       0  2070.8    19.8    2067    39.7 2057.63   119.1 2038.65   138.9 2023.55
   158.8 2015.35   168.7 2008.81   208.4  1980.1   218.3 1969.71   248.1 1936.82
   287.8 1885.87   307.6 1865.01   317.5 1848.49   327.4 1838.04   347.3 1825.48
   357.2 1822.42   377.1 1820.79   394.3 1820.88   419.3 1821.64   515.5 1829.38
   535.2 1833.28   545.1 1837.77   574.7 1860.76   594.5  1879.7   663.6  1921.9
   683.4 1939.83   742.6 1980.11   752.5 1987.64   772.2  2009.1   831.5 2054.16
#Mann= 3 , 0 , 0
       0      .1       0   394.3    .045       0   419.3      .1       0
Bank Sta=394.3,419.3
XS Rating Curve= 0 ,0
Exp/Cntr=0.3,0.1

Type RM Length L Ch R = 1 ,40278.1 ,390.1,399.7,403.9
XS GIS Cut Line= 3
      1928350.87      286936.498     1928765.322      286854.333
     1929170.815       286817.06
#Sta/Elev= 30
       0 2041.91      59  2005.4    78.6 1987.83   108.1 1971.76   137.6 1952.26
   157.2 1934.63     226 1893.07   235.8 1881.04   304.6 1843.92   324.3 1828.64
   353.7 1819.85   373.4 1816.14     393 1814.96     410 1815.03     435  1815.1
   452.3 1816.33   472.2 1822.81   482.1 1830.78   511.9  1846.1   531.8 1859.43
   551.6 1876.68   561.6 1891.95   631.1 1952.53     641 1969.48   710.5  2027.7
   720.5 2043.86   730.4  2053.2     790 2097.54   799.9 2110.14   829.7 2131.58
#Mann= 3 , 0 , 0
       0      .1       0     410    .045       0     435      .1       0
Bank Sta=410,435
XS Rating Curve= 0 ,0
Exp/Cntr=0.3,0.1

Type RM Length L Ch R = 1 ,39878.1 ,416,399.5,386.2
XS GIS Cut Line= 3
     1928319.555      287186.389     1928723.553      287250.748
     1929134.662      287274.784
#Sta/Elev= 30
       0 2052.58      10 2047.03      20 2037.12    29.9 2030.08    89.8 1997.26
   109.8 1970.66   169.6 1929.15   189.6 1908.06   249.4  1869.3   269.4 1851.28
   319.3 1821.32   349.2 1807.51   396.6 1806.95   421.6 1806.77   438.5 1806.67
   458.1 1809.41   487.5 1827.49   497.3 1834.09   507.1 1847.07   575.8 1896.62
   585.6 1916.26   595.4 1940.35   605.2 1961.34     615 1974.42     664  2007.5
   683.6 2026.02   742.5 2067.94   762.1 2085.38   791.5 2099.18   820.9 2117.98
#Mann= 3 , 0 , 0
       0      .1       0   396.6    .045       0   421.6      .1       0
Bank Sta=396.6,421.6
XS Rating Curve= 0 ,0
Exp/Cntr=0.3,0.1