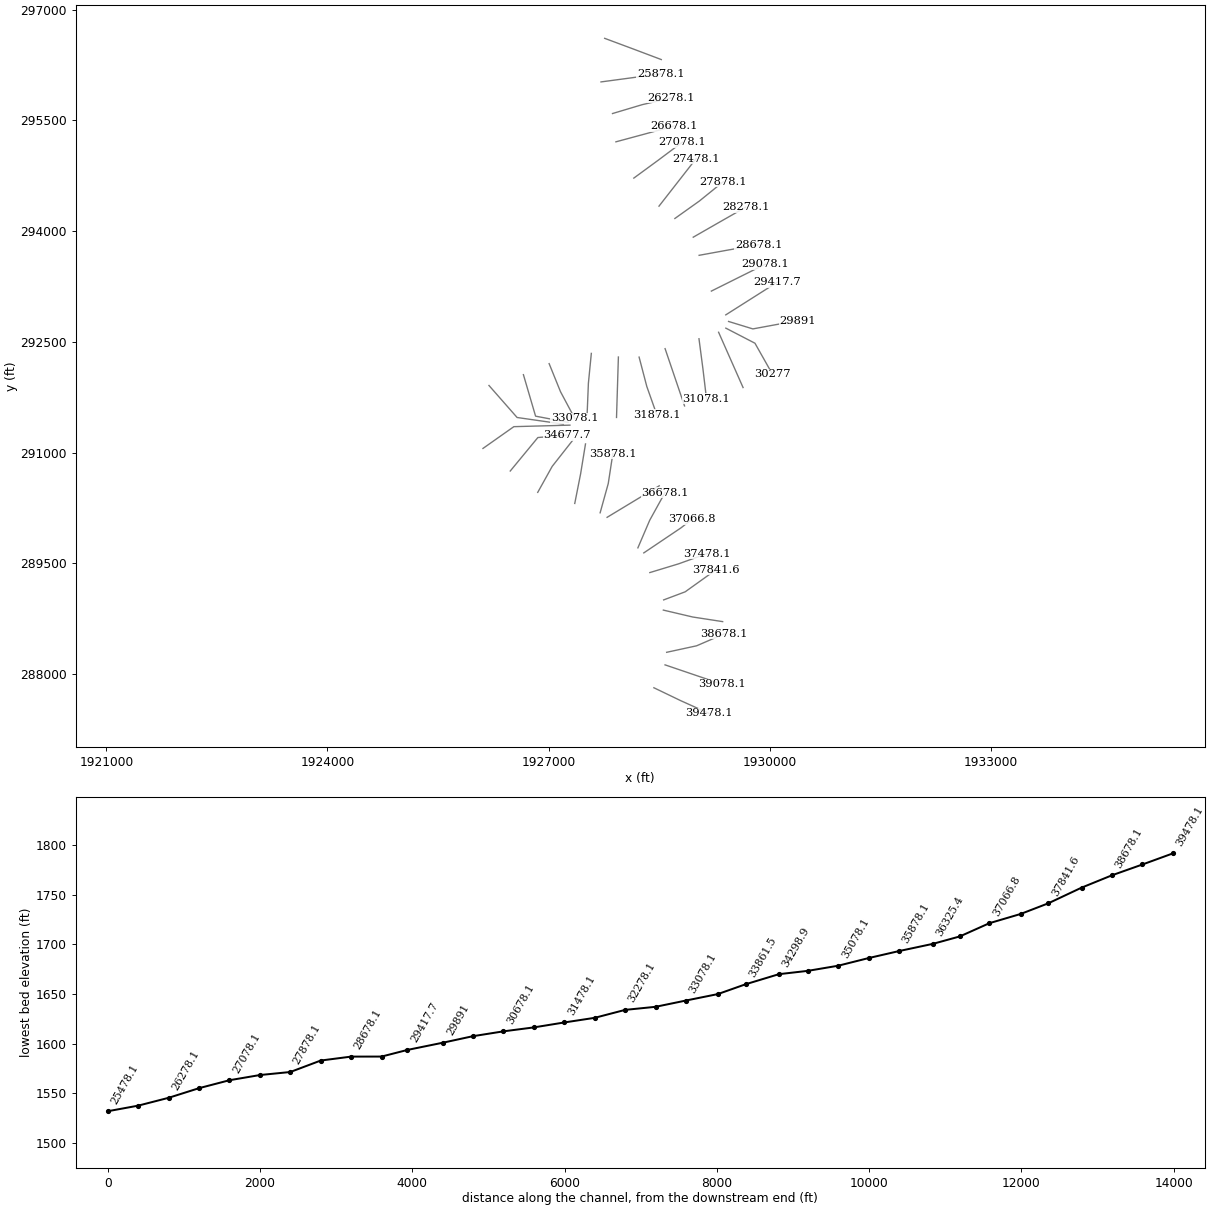
HEC-RAS study PnyCrk.prj: PnyCrk

--- PnyCrk.g01 (geometry) --- (continued)

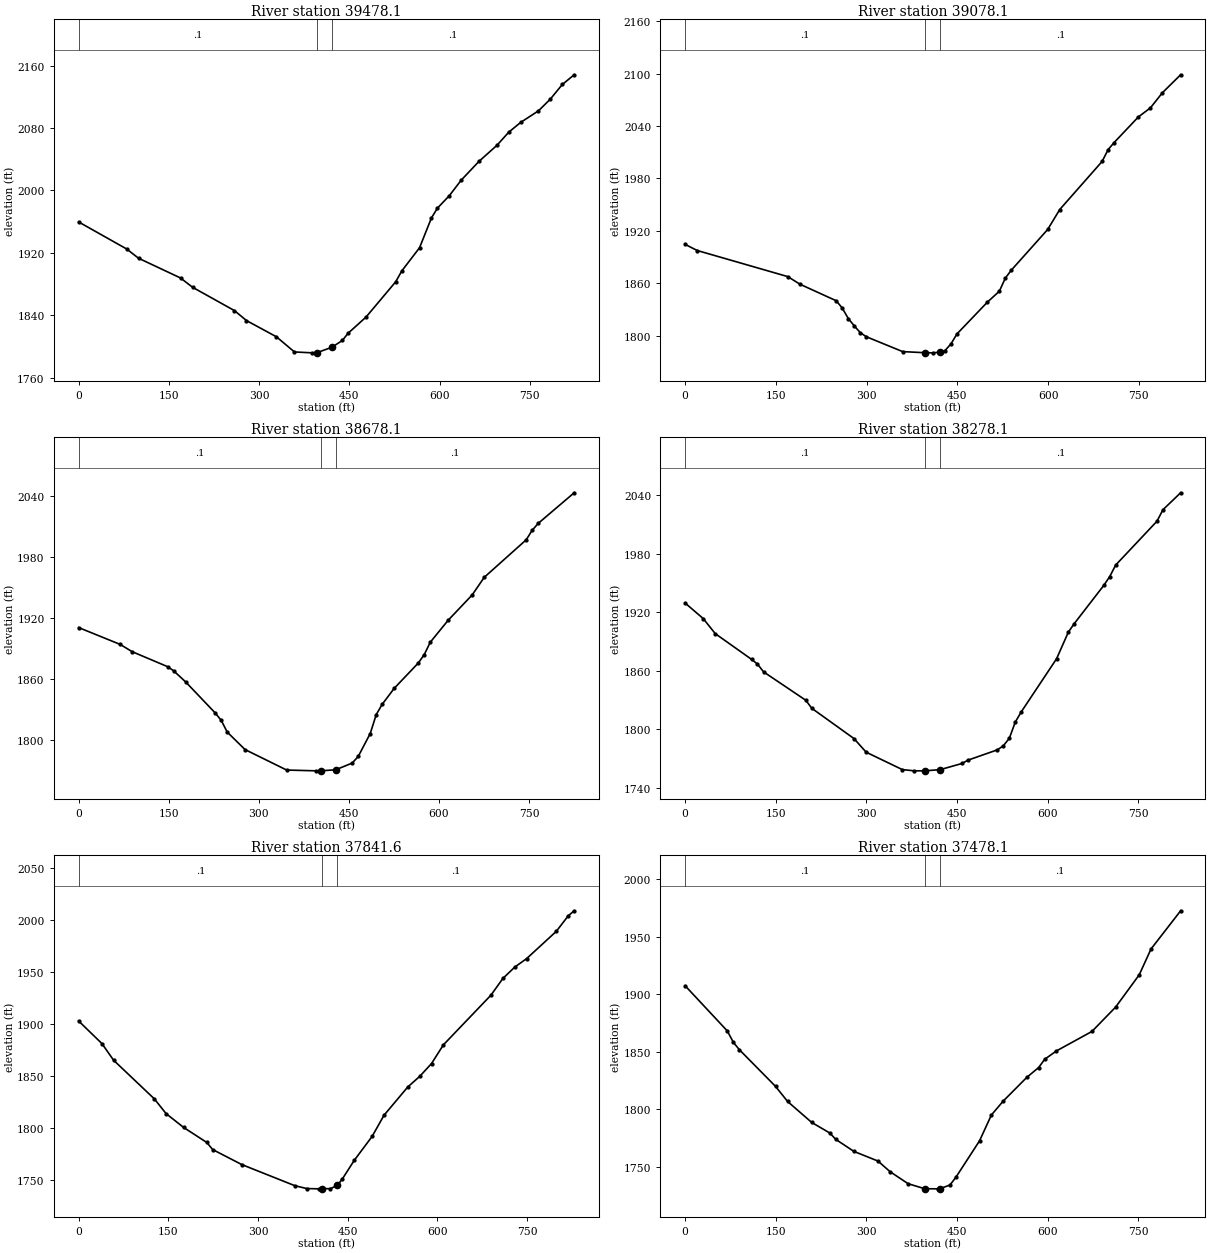
Type RM Length L Ch R = 1 ,39478.1 ,396.2,399.6,402.3
XS GIS Cut Line= 3
     1928428.739      287816.447     1928796.991      287639.624
     1929175.643       287469.44
#Sta/Elev= 30
       0 1959.63    79.7 1925.02    99.6 1913.09   169.4 1887.77   189.3  1875.9
     259 1845.95     279 1833.19   328.8 1812.38   358.7 1792.94   388.6 1791.82
     396 1792.01     421 1798.99   438.2 1807.65     448 1817.02   477.7 1837.71
   527.1 1883.05     537 1896.71   566.6 1926.54   586.4 1964.77   596.3 1977.29
   616.1 1993.29   635.8 2013.14   665.5 2037.36   695.2 2057.83   714.9  2074.7
   734.7 2087.24   764.3 2102.09   784.1 2117.21   803.9 2135.84   823.6 2148.29
#Mann= 3 , 0 , 0
       0      .1       0     396    .045       0     421      .1       0
Bank Sta=396,421
XS Rating Curve= 0 ,0
Exp/Cntr=0.3,0.1

Type RM Length L Ch R = 1 ,39078.1 ,384.5,399.5,419.8
XS GIS Cut Line= 3
     1928580.107      288126.502      1928967.88      287994.888
     1929355.653      287863.274
#Sta/Elev= 30
       0 1904.69      20 1897.65   169.8 1867.78   189.8  1859.1   249.7 1840.21
   259.7  1831.9   269.7 1819.84   279.7 1811.37   289.6 1803.68   299.6 1799.01
   359.6 1782.03     397 1780.75   409.5 1780.63     422 1781.46   429.5 1783.16
   439.5 1790.94   449.4 1802.31   499.4 1838.45   519.4 1851.11   529.4 1866.25
   539.3 1875.28   599.3 1921.73   619.2 1944.51   689.2 1999.47   699.2 2013.08
   709.1 2021.12   749.1 2050.34   769.1 2060.77     789 2078.15     819 2098.58
#Mann= 3 , 0 , 0
       0      .1       0     397    .045       0     422      .1       0
Bank Sta=397,422
XS Rating Curve= 0 ,0
Exp/Cntr=0.3,0.1

Type RM Length L Ch R = 1 ,38678.1 ,412.1,399.7,384.3
XS GIS Cut Line= 3
     1928601.974      288296.636     1929008.207      288384.636
     1929384.327      288546.797
#Sta/Elev= 30
       0 1910.71    69.3  1894.1    89.1    1887   148.4 1872.18   158.3 1868.11
   178.1 1857.32   227.6 1826.59   237.5 1819.35   247.4 1807.91   277.1 1790.69
   346.4 1770.53   395.9 1769.75   403.2 1769.76   428.2 1770.81   455.6 1777.43
   465.6 1783.91   485.6 1806.48   495.6 1825.11   505.6 1835.27   525.5  1850.9
   565.5 1875.75   575.5 1884.04   585.5 1896.21   615.4 1917.93   655.4 1942.83
   675.4 1960.11   745.3 1997.04   755.3 2006.41   765.3 2013.21   825.2 2043.32
#Mann= 3 , 0 , 0
       0      .1       0   403.2    .045       0   428.2      .1       0
Bank Sta=403.2,428.2
XS Rating Curve= 0 ,0
Exp/Cntr=0.3,0.1

Type RM Length L Ch R = 1 ,38278.1 ,412.6,436.1,457.6
XS GIS Cut Line= 3
     1928557.185      288868.246     1928955.812      288774.625
     1929361.667      288712.263
#Sta/Elev= 30
       0 1929.56      30 1913.59    49.9 1898.13   109.9 1871.75   119.8 1866.87
   129.8 1858.91   199.7 1829.74   209.7 1821.46   279.6 1790.34   299.6 1776.41
   359.5 1758.54   379.5 1757.26     397 1757.29     422 1758.46   458.4 1764.85
   468.1 1768.23     517 1778.86   526.8  1783.1   536.6  1790.7   546.4 1807.26
   556.1  1817.6   614.8 1872.36   634.3  1899.7   644.1 1908.45     693 1947.72
   702.8 1956.76   712.6 1968.54     781 2013.59   790.8 2025.31   820.1 2042.74
#Mann= 3 , 0 , 0
       0      .1       0     397    .045       0     422      .1       0
Bank Sta=397,422
XS Rating Curve= 0 ,0
Exp/Cntr=0.3,0.1

Type RM Length L Ch R = 1 ,37841.6 ,372,363.1,355.5
XS GIS Cut Line= 3
     1928561.454      289006.268     1928853.471      289115.934
     1929274.137      289416.407
#Sta/Elev= 30
       0 1903.06      39 1881.29    58.5 1865.27   126.7 1828.07   146.2 1813.96
   175.5 1800.63   214.4 1786.12   224.2  1779.3   272.9 1764.86   361.6 1744.53
   381.5 1741.78   401.4 1741.49   407.9  1741.6   421.3  1741.7   432.9 1744.89
   441.2 1751.06     461  1768.9   490.9 1791.93   510.8  1812.3   550.5  1839.5
   570.4 1849.64   590.3 1862.09   610.2 1880.12   689.7 1927.92   709.6 1943.96
   729.5 1954.91   749.4  1963.1   799.1  1989.4     819 2004.29   828.9 2009.14
#Mann= 3 , 0 , 0
       0      .1       0   407.9    .045       0   432.9      .1       0
Bank Sta=407.9,432.9
XS Rating Curve= 0 ,0
Exp/Cntr=0.3,0.1

Type RM Length L Ch R = 1 ,37478.1 ,400.3,411,420.4
XS GIS Cut Line= 3
     1928373.983      289376.561     1928765.355      289495.282
     1929152.171      289634.154
#Sta/Elev= 30
       0 1907.41    69.8 1868.09    79.8 1858.23    89.8 1851.74   149.6 1819.88
   169.6 1806.72   209.5 1788.49   239.4  1779.3   249.4 1773.73   279.3  1763.3
   319.2 1754.89   339.2 1745.65   369.1 1735.17   396.5 1730.83   418.8 1730.73
   421.5 1730.83   438.3 1734.05   448.1  1740.8   487.3 1772.54   506.8 1794.92
   526.4 1807.05   565.6 1827.77   585.1 1836.26   594.9 1843.34   614.5  1850.7
   673.2 1867.61   712.3 1888.73   751.5 1916.89     771 1939.36     820 1972.58
#Mann= 3 , 0 , 0
       0      .1       0   396.5    .045       0   421.5      .1       0
Bank Sta=396.5,421.5
XS Rating Curve= 0 ,0
Exp/Cntr=0.3,0.1

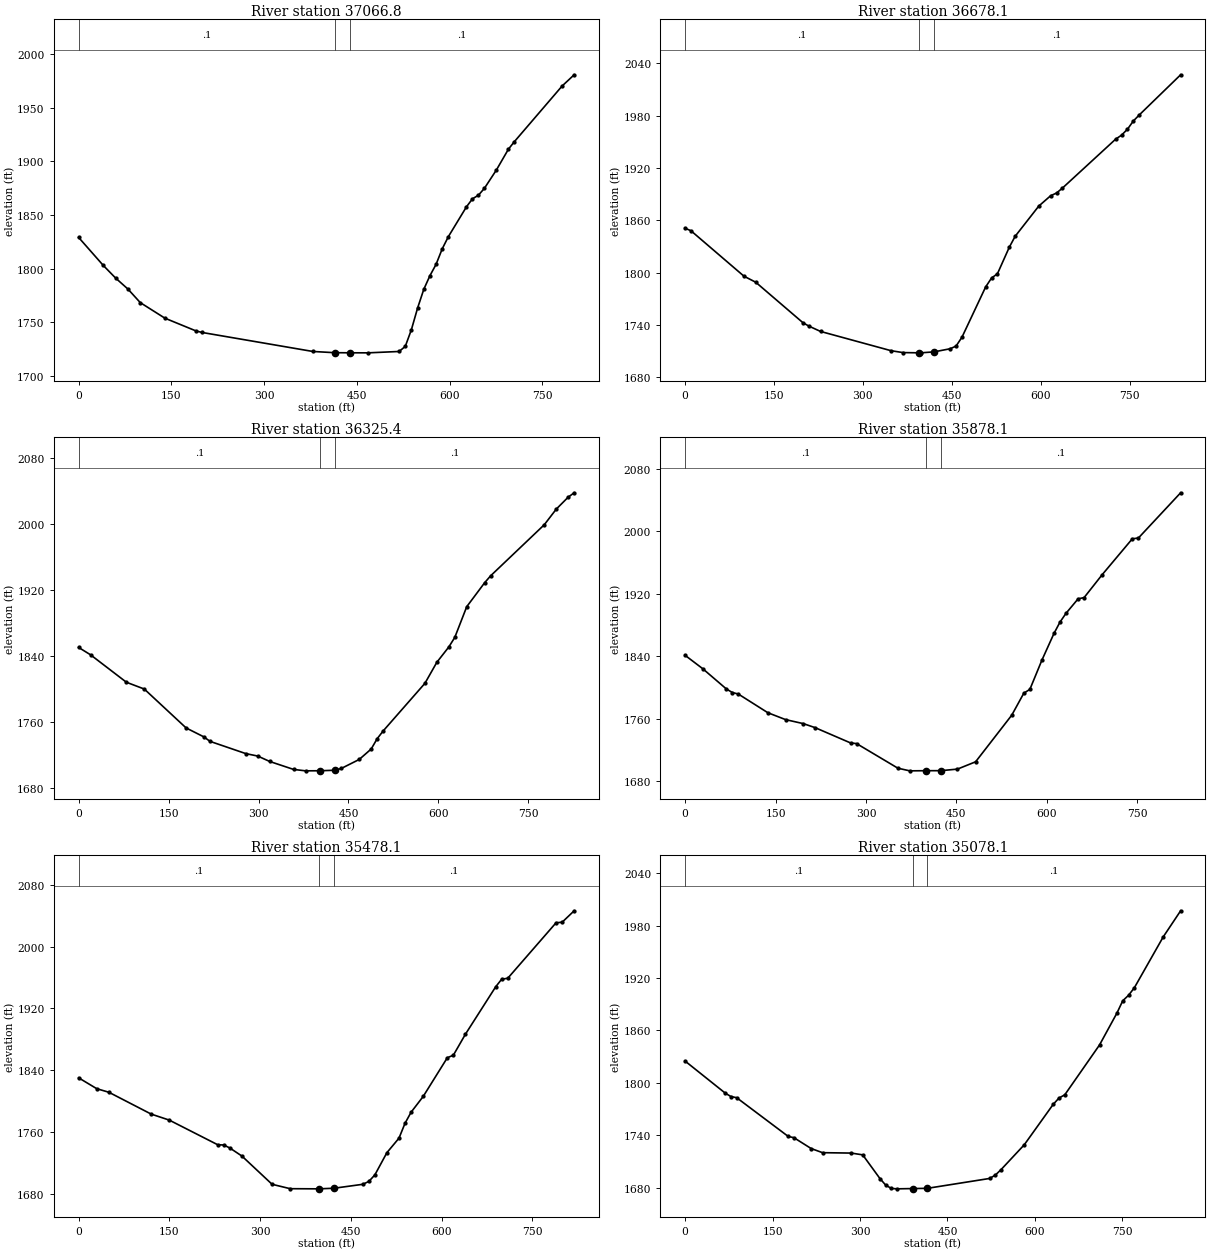
Type RM Length L Ch R = 1 ,37066.8 ,373.6,388.3,400.3
XS GIS Cut Line= 3
     1928291.843      289643.079     1928796.578       289982.25
     1928949.153      290101.207
#Sta/Elev= 30
       0 1828.94    39.9 1802.84    59.8 1791.11    79.8 1780.82    99.7 1768.22
   139.6  1753.7   189.4 1741.94   199.4 1740.43   378.8  1722.7   413.9 1721.56
   438.9 1721.46   468.5 1721.42   518.4 1722.69   528.4 1727.44   538.3 1743.01
   548.3 1763.13   558.3 1780.54   568.2 1793.23   578.2 1803.87   588.2 1818.37
   598.1 1829.69   627.4  1857.5   637.1 1864.93   646.8 1868.32   656.5 1874.81
   675.8  1891.8   695.2 1911.14   704.8 1918.14   782.2  1970.1   801.6  1980.5
#Mann= 3 , 0 , 0
       0      .1       0   413.9    .045       0   438.9      .1       0
Bank Sta=413.9,438.9
XS Rating Curve= 0 ,0
Exp/Cntr=0.3,0.1

Type RM Length L Ch R = 1 ,36678.1 ,369.3,352.1,337.8
XS GIS Cut Line= 3
       1928211.7      289711.422     1928372.367      290085.841
     1928580.252      290460.969
#Sta/Elev= 30
       0 1850.87     9.9 1847.94    99.4 1795.86   119.2 1788.98   198.8 1742.62
   208.7 1738.76   228.6 1732.58   347.8 1710.48   367.7 1708.35   394.9 1708.08
   397.5 1708.06   419.9 1709.15   447.3 1712.73   457.3 1715.82   467.3 1726.01
   507.2 1783.53   517.2  1793.8   527.1 1798.64   547.1 1829.04     557 1841.57
   596.9 1876.23   616.9 1888.07   626.9 1891.21   636.8 1896.83   726.6  1952.9
   736.6  1957.5   746.6 1964.33   756.5 1973.72   766.5 1980.67   836.3 2026.67
#Mann= 3 , 0 , 0
       0      .1       0   394.9    .045       0   419.9      .1       0
Bank Sta=394.9,419.9
XS Rating Curve= 0 ,0
Exp/Cntr=0.3,0.1

Type RM Length L Ch R = 1 ,36325.4 ,425.9,446.8,471
XS GIS Cut Line= 2
     1927793.769      290124.698     1928501.344      290551.698
#Sta/Elev= 30
       0 1850.48    19.9 1841.54    79.7  1808.2   109.5 1799.96   179.2 1752.73
   209.1 1741.76     219 1736.44   278.8 1721.53   298.7 1718.55   318.6    1712
   358.4 1702.33   378.4  1700.6   402.9 1700.71   427.9 1701.34   438.1 1703.52
     468 1714.46   487.9 1727.11   497.8 1739.56   507.8 1748.99   577.5 1806.91
   597.4 1832.48   617.3 1851.02   627.3 1862.66   647.2 1899.95   677.1  1929.1
     687 1937.45   776.6 1999.57   796.6 2018.57   816.5 2033.09   826.4 2038.36
#Mann= 3 , 0 , 0
       0      .1       0   402.9    .045       0   427.9      .1       0
Bank Sta=402.9,427.9
XS Rating Curve= 0 ,0
Exp/Cntr=0.3,0.1

Type RM Length L Ch R = 1 ,35878.1 ,397.5,399.6,399.3
XS GIS Cut Line= 3
     1927699.388       290186.07     1927809.607      290582.886
     1927871.955      290988.244
#Sta/Elev= 30
       0 1841.31    29.4 1824.07    68.6 1798.11    78.4 1793.63    88.2 1791.73
   137.3 1767.73   166.7 1758.92   196.1 1753.78   215.7 1748.62   274.6 1728.99
   284.4 1728.22     353 1696.66   372.6 1693.28   399.3 1693.45   424.3  1693.5
   451.8  1695.5   481.9 1704.87   541.9 1764.66   561.9 1792.84   571.9 1797.65
   591.9 1835.18   611.9 1869.34   621.9  1883.9   631.9 1895.18   651.9 1913.67
   661.9  1915.3   691.9 1944.67   741.9 1990.67   751.9 1991.57     822 2049.58
#Mann= 3 , 0 , 0
       0      .1       0   399.3    .045       0   424.3      .1       0
Bank Sta=399.3,424.3
XS Rating Curve= 0 ,0
Exp/Cntr=0.3,0.1

Type RM Length L Ch R = 1 ,35478.1 ,408.2,399.4,385.4
XS GIS Cut Line= 3
     1927355.086      290312.797     1927434.655      290714.784
     1927500.745      291118.864
#Sta/Elev= 30
       0 1829.96      30 1815.88      50 1811.28   119.9 1783.02   149.9  1775.2
   229.9 1743.32   239.9 1742.98   249.9 1739.14   269.9 1728.68   319.8 1692.09
   349.8 1686.39   397.3 1686.21   422.3    1687   469.7 1692.08   479.7 1695.76
   489.7 1704.24   509.6 1733.04   529.6 1751.85   539.6 1771.16   549.6 1785.43
   569.6 1805.83   609.5 1855.98   619.5  1859.3   639.5 1886.55   689.4 1947.78
   699.4 1957.73   709.4 1958.89   789.3  2030.8   799.3 2031.45   819.2 2046.29
#Mann= 3 , 0 , 0
       0      .1       0   397.3    .045       0   422.3      .1       0
Bank Sta=397.3,422.3
XS Rating Curve= 0 ,0
Exp/Cntr=0.3,0.1

Type RM Length L Ch R = 1 ,35078.1 ,405.2,400.4,399.8
XS GIS Cut Line= 3
     1926852.758      290462.829     1927048.841      290814.762
     1927325.468      291165.968
#Sta/Elev= 30
       0 1824.94    68.8 1788.22    78.6 1784.28    88.4 1782.98   176.9 1738.55
   186.7 1737.11   216.2 1724.68   235.8 1719.94     285 1719.49   304.6 1717.45
   334.1 1690.35   343.9 1682.88   353.7 1678.94   363.6  1678.5   390.4 1678.82
   415.4 1679.08   522.1 1690.38     532 1694.19     542 1700.61   581.7    1729
   631.4  1775.4   641.3 1782.58   651.2 1786.29   710.8 1843.43   740.6  1879.9
   750.6 1894.04   760.5  1900.3   770.5 1908.95   820.1 1967.35   849.9  1997.2
#Mann= 3 , 0 , 0
       0      .1       0   390.4    .045       0   415.4      .1       0
Bank Sta=390.4,415.4
XS Rating Curve= 0 ,0
Exp/Cntr=0.3,0.1

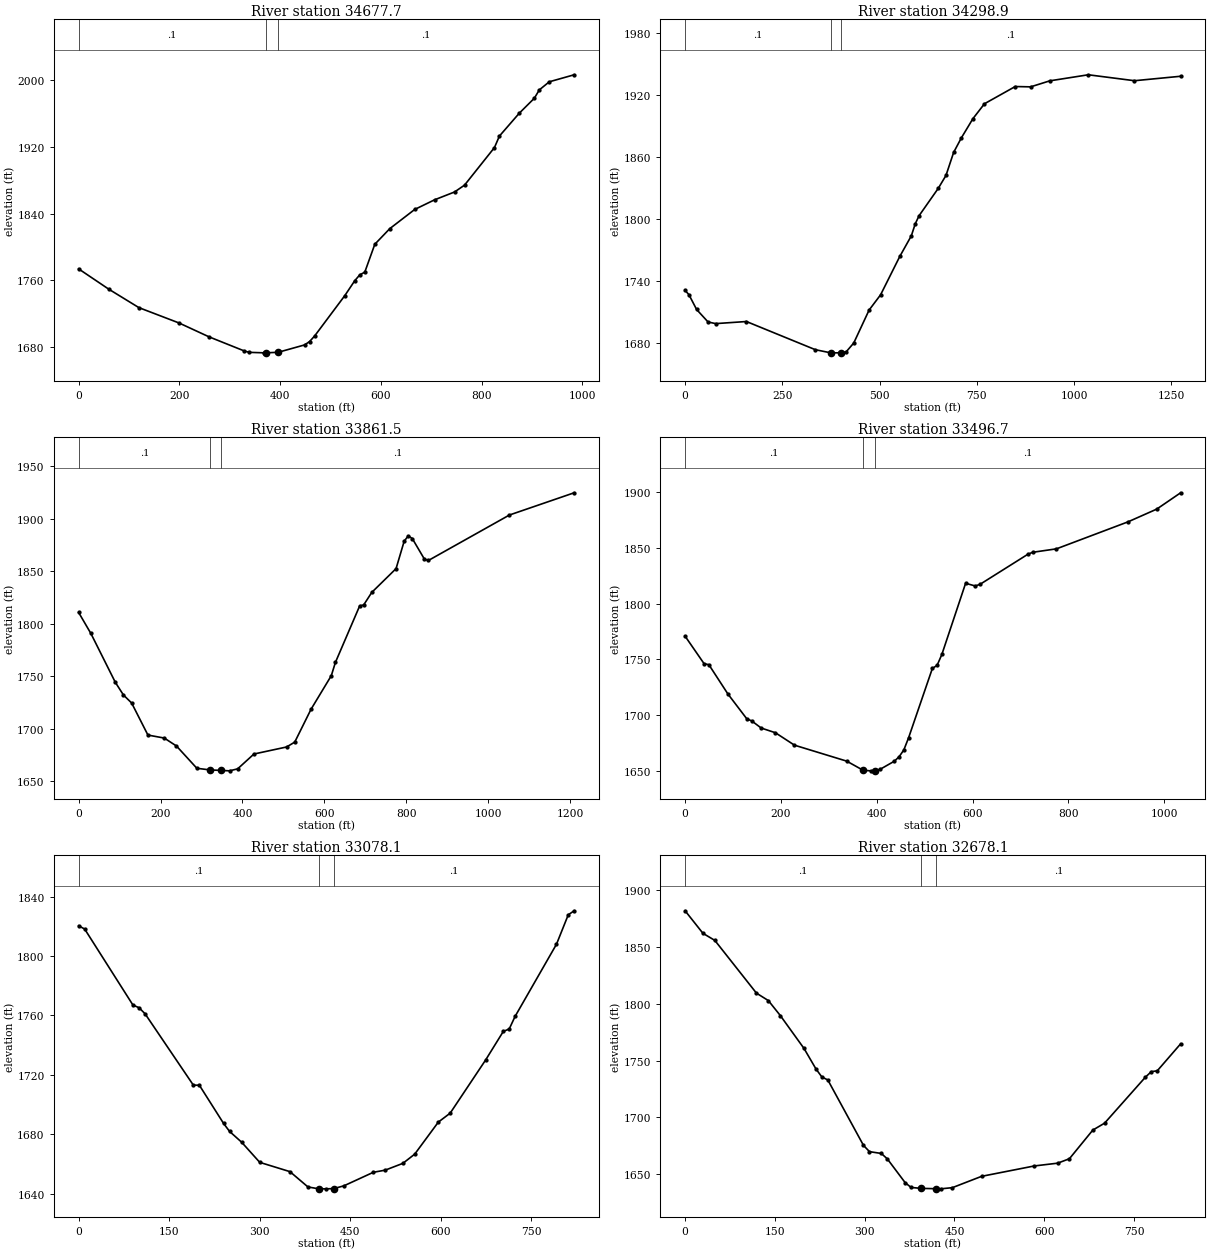
Type RM Length L Ch R = 1 ,34677.7 ,385.6,378.2,370.8
XS GIS Cut Line= 3
     1926479.977      290752.203     1926854.478      291205.437
     1927248.688      291239.626
#Sta/Elev= 30
       0  1773.8    59.8 1749.52   119.6 1727.42   199.3 1709.04   259.1 1692.38
   328.8 1675.56   338.8 1673.89   368.7  1673.3   371.1  1673.3   396.1 1673.96
   448.4 1682.76   458.4 1686.82   468.4 1693.45   528.2 1741.68   548.1 1759.66
     558 1766.62     568 1769.91   587.9 1803.28   617.6 1821.95   667.1 1844.94
   706.6 1856.49   746.2 1865.85     766 1874.04   825.4 1919.04   835.2 1932.77
   874.8 1960.24   904.5 1978.03   914.4 1988.02   934.2 1997.74   983.6 2006.13
#Mann= 3 , 0 , 0
       0      .1       0   371.1    .045       0   396.1      .1       0
Bank Sta=371.1,396.1
XS Rating Curve= 0 ,0
Exp/Cntr=0.3,0.1

Type RM Length L Ch R = 1 ,34298.9 ,477.6,437.2,396.8
XS GIS Cut Line= 3
     1926109.705      291058.034      1926528.64       291352.84
     1927289.742       291373.38
#Sta/Elev= 30
       0 1730.56     9.8 1726.42    29.6 1712.03    59.1 1699.88    78.8 1698.33
   157.6 1700.36   334.9    1673   374.4 1669.97   375.6 1669.97   400.6 1669.99
   413.8 1670.87   433.5 1679.54   472.9 1711.48   502.4 1726.25   551.8 1763.52
   581.5 1783.55   591.4 1795.06   601.3 1802.99   650.7  1829.6   670.5 1842.09
   690.2 1864.45     710 1878.52   739.7 1897.15   769.4 1911.64   848.5 1928.36
     888 1928.04   937.4 1933.89  1036.3 1939.76    1155    1934  1273.6 1938.32
#Mann= 3 , 0 , 0
       0      .1       0   375.6    .045       0   400.6      .1       0
Bank Sta=375.6,400.6
XS Rating Curve= 0 ,0
Exp/Cntr=0.3,0.1

Type RM Length L Ch R = 1 ,33861.5 ,376.4,364.4,352.3
XS GIS Cut Line= 3
     1926191.131      291910.461     1926572.602      291476.969
     1927198.836      291387.483
#Sta/Elev= 30
       0 1810.69    29.9 1790.67    89.6 1744.12   109.5    1732   129.4 1724.44
   169.2 1693.88   209.1 1691.02   238.9 1683.45   288.7 1662.22   321.9 1660.62
   346.9 1660.22   368.4 1659.79   388.3 1661.69   428.1 1675.82   507.8 1682.52
   527.7 1687.17   567.5 1718.48     617 1750.48   626.9 1763.01   686.2  1816.9
     696 1817.84   715.8  1829.8   775.1 1852.46   794.9 1878.57   804.8 1883.64
   814.7 1881.13   844.3  1861.5   854.2 1860.25  1051.9 1903.52    1210 1924.71
#Mann= 3 , 0 , 0
       0      .1       0   321.9    .045       0   346.9      .1       0
Bank Sta=321.9,346.9
XS Rating Curve= 0 ,0
Exp/Cntr=0.3,0.1

Type RM Length L Ch R = 1 ,33496.7 ,415.8,418.5,424.2
XS GIS Cut Line= 3
     1926658.483      292057.003     1926823.446      291495.071
     1927264.461      291411.479
#Sta/Elev= 30
       0 1770.73    39.7 1746.01    49.6 1745.16    89.3  1718.9     129 1696.46
     139 1694.73   158.8 1688.31   188.6 1684.06   228.3 1672.92   337.5 1658.57
   371.5 1650.42   387.1 1649.88   396.5 1649.97     407 1651.22   436.8 1658.52
   446.7 1662.49   456.6 1668.61   466.5 1679.46   516.2 1741.78   526.1 1744.57
     536 1754.32   585.6 1818.22   605.6 1815.81   615.6 1817.24   715.3 1844.19
   725.3 1846.01   775.2 1849.12   924.8 1873.38   984.6 1884.78  1034.5 1899.44
#Mann= 3 , 0 , 0
       0      .1       0   371.5    .045       0   396.5      .1       0
Bank Sta=371.5,396.5
XS Rating Curve= 0 ,0
Exp/Cntr=0.3,0.1

Type RM Length L Ch R = 1 ,33078.1 ,412.9,399.6,385
XS GIS Cut Line= 3
     1927007.448      292206.422     1927161.558      291826.553
     1927355.249      291464.171
#Sta/Elev= 30
       0 1820.35      10 1818.14      90 1766.99     100 1765.24     110 1761.17
     190 1713.15     200 1713.07     240 1687.44     250 1682.02     270 1674.76
     300  1661.2     350 1654.96   379.9 1644.64   397.4 1643.44   409.9 1643.39
   422.4 1643.55   439.3  1645.4   488.2 1654.53   507.8 1655.96   537.1 1660.54
   556.7 1666.74   595.8 1688.28   615.4 1694.29   674.1 1730.04   703.4 1749.27
   713.2 1750.92     723 1759.43   791.5 1807.93     811 1827.72   820.8 1830.43
#Mann= 3 , 0 , 0
       0      .1       0   397.4    .045       0   422.4      .1       0
Bank Sta=397.4,422.4
XS Rating Curve= 0 ,0
Exp/Cntr=0.3,0.1

Type RM Length L Ch R = 1 ,32678.1 ,397.8,399.6,399.9
XS GIS Cut Line= 3
     1927579.933      292345.141      1927540.01      291939.794
     1927522.803      291519.667
#Sta/Elev= 30
       0 1882.05    29.8  1862.2    49.7 1855.93   119.2 1809.48   139.1 1802.91
     159 1789.77   198.7  1760.7   218.6 1742.69   228.5 1735.59   238.4 1732.99
     298 1675.33     308 1669.82   327.8 1668.21   337.8 1663.44   367.6  1642.5
   377.5 1638.26   394.8 1637.44   419.8 1637.14   426.9 1637.04   446.4 1638.07
   495.3 1648.06   583.3  1657.2   622.4 1659.66     642 1663.57   681.1 1688.82
   700.7 1694.89   769.1 1735.53   778.9 1740.33   788.7 1741.01   827.8 1764.81
#Mann= 3 , 0 , 0
       0      .1       0   394.8    .045       0   419.8      .1       0
Bank Sta=394.8,419.8
XS Rating Curve= 0 ,0
Exp/Cntr=0.3,0.1

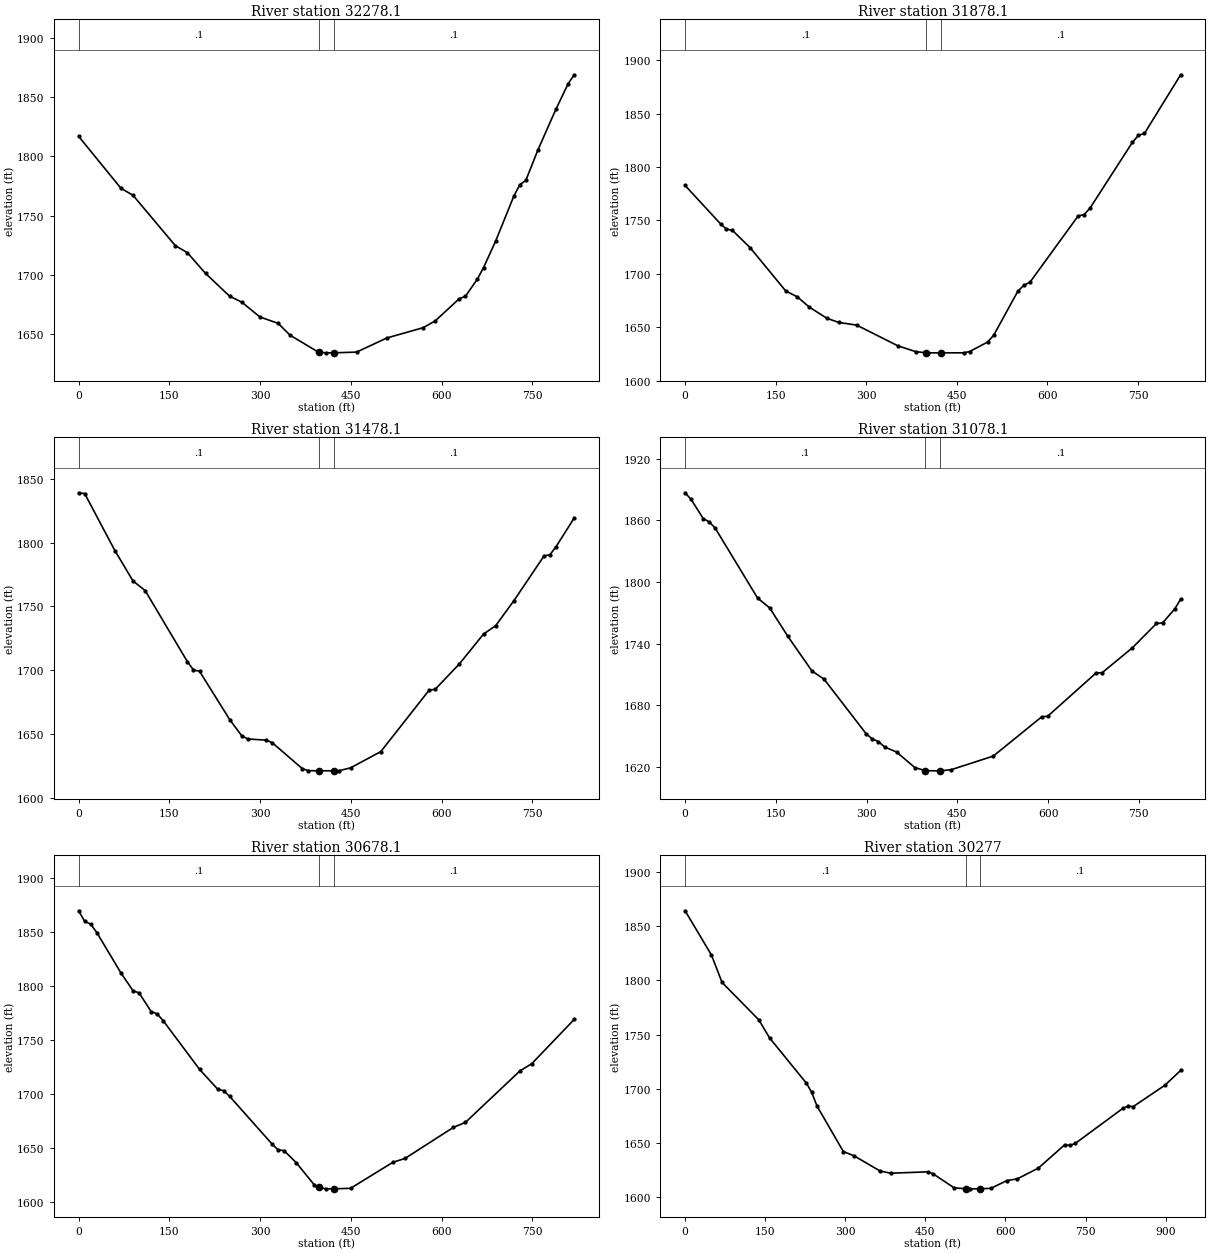
Type RM Length L Ch R = 1 ,32278.1 ,392.1,400,410.3
XS GIS Cut Line= 3
     1927947.089      292295.976      1927934.39      291886.673
     1927921.691       291477.37
#Sta/Elev= 30
       0 1816.88    69.9 1773.02    89.9 1767.06   159.8 1724.52   179.8 1718.54
   209.7 1701.09   249.7 1681.73   269.7 1676.77   299.6 1664.25   329.6  1658.9
   349.6  1648.8     397 1634.32   409.5 1633.94     422 1633.96   459.4 1634.55
   509.4 1646.51   569.3 1655.17   589.3 1660.91   629.2 1679.75   639.2 1681.67
   659.2 1696.42   669.2 1705.99   689.2 1728.31   719.1 1766.18   729.1 1775.99
   739.1 1779.61   759.1 1805.45     789 1840.02     809 1861.29     819 1868.92
#Mann= 3 , 0 , 0
       0      .1       0     397    .045       0     422      .1       0
Bank Sta=397,422
XS Rating Curve= 0 ,0
Exp/Cntr=0.3,0.1

Type RM Length L Ch R = 1 ,31878.1 ,398,400,399.6
XS GIS Cut Line= 3
     1928228.074      292295.039     1928332.525      291897.257
     1928469.358      291511.625
#Sta/Elev= 30
       0 1782.69    58.8 1746.63    68.5 1741.83    78.3 1740.68   107.7 1724.41
   166.5 1683.95     186 1678.31   205.6 1668.77     235 1658.22   254.6  1654.4
     284 1651.91   352.5 1632.45   381.9 1627.05   398.8 1625.96   401.5 1625.92
   423.8 1625.94   461.2 1625.94   471.2 1627.16   501.1 1636.07   511.1 1642.55
     551  1683.7     561  1689.2     571 1692.04   650.8 1754.17   660.8  1755.4
   670.8 1761.78   740.6  1823.1   750.6 1829.65   760.6 1831.44   820.5 1886.39
#Mann= 3 , 0 , 0
       0      .1       0   398.8    .045       0   423.8      .1       0
Bank Sta=398.8,423.8
XS Rating Curve= 0 ,0
Exp/Cntr=0.3,0.1

Type RM Length L Ch R = 1 ,31478.1 ,405.4,400,394.2
XS GIS Cut Line= 3
     1928580.784      292409.179     1928712.645       292021.49
     1928844.507        291633.8
#Sta/Elev= 30
       0 1839.01      10 1838.38    59.9 1793.75    89.9 1769.93   109.9 1762.46
   179.8  1706.7   189.8 1700.22   199.8 1699.24   249.7 1661.36   269.7 1648.59
   279.7 1646.23   309.6 1645.26   319.6 1643.42   369.6 1623.02   379.5 1621.36
     397  1621.3     422 1621.26   429.5 1621.24   449.4 1623.58   499.4 1636.29
   579.3 1684.43   589.3 1685.09   629.2 1704.95   669.2 1728.36   689.2 1734.88
   719.1  1754.3   769.1 1789.48     779 1790.53     789 1796.75     819 1819.23
#Mann= 3 , 0 , 0
       0      .1       0     397    .045       0     422      .1       0
Bank Sta=397,422
XS Rating Curve= 0 ,0
Exp/Cntr=0.3,0.1

Type RM Length L Ch R = 1 ,31078.1 ,391.8,399.7,407.9
XS GIS Cut Line= 3
     1929040.564      292543.645     1929093.942      292137.604
     1929142.499      291730.999
#Sta/Elev= 30
       0 1886.93      10  1880.4      30 1861.79      40  1858.6    49.9 1852.35
   119.9 1784.36   139.8 1774.87   169.8 1747.18   209.8 1713.34   229.7 1705.48
   299.7 1651.98   309.6 1647.32   319.6 1644.68   329.6 1639.51   349.6 1634.53
   379.6 1619.49     397 1616.38   419.5 1616.25     422 1616.28   439.5 1617.31
   509.4 1630.61   589.3  1668.8   599.3 1669.42   679.2  1711.5   689.2 1711.74
   739.1 1735.94   779.1 1759.72   789.1 1760.23     809 1773.65     819 1783.32
#Mann= 3 , 0 , 0
       0      .1       0     397    .045       0     422      .1       0
Bank Sta=397,422
XS Rating Curve= 0 ,0
Exp/Cntr=0.3,0.1

Type RM Length L Ch R = 1 ,30678.1 ,398.1,400.8,403.5
XS GIS Cut Line= 3
      1929306.75      292631.489     1929472.691      292257.118
     1929638.632      291882.746
#Sta/Elev= 30
       0  1869.7      10 1859.94      20 1857.24      30 1849.58    69.9 1812.16
    89.9 1795.68    99.9  1793.7   119.8 1776.43   129.8 1774.22   139.8 1767.91
   199.8  1722.9   229.7  1704.6   239.7 1703.14   249.7 1697.81   319.6 1653.82
   329.6 1648.39   339.6  1647.6   359.6 1636.52   389.5  1615.9     397 1613.52
   409.5 1612.27     422 1612.32   449.4 1612.73   519.4 1636.85   539.3 1640.38
   619.2  1669.1   639.2 1673.77   729.1 1721.29   749.1 1728.23     819  1769.1
#Mann= 3 , 0 , 0
       0      .1       0     397    .045       0     422      .1       0
Bank Sta=397,422
XS Rating Curve= 0 ,0
Exp/Cntr=0.3,0.1

Type RM Length L Ch R = 1 ,30277   ,351.2,385.5,419.8
XS GIS Cut Line= 3
      1929405.03      292687.205     1929799.953       292482.93
     1930038.106       292062.16
#Sta/Elev= 30
       0 1864.35    49.4 1823.43    69.2 1798.14   138.3 1763.42   158.1 1746.93
   227.2    1705   237.1 1696.53     247 1683.94   296.4 1641.84   316.2 1637.95
   365.6 1623.76   385.3 1621.84   454.5 1623.08   464.4 1621.31   503.8 1608.32
   526.6 1607.39   533.4 1607.38   551.6 1607.41   572.9 1607.85   602.5    1615
   622.2  1616.6   661.7 1626.55     711  1648.1   720.9 1647.48   730.8 1649.38
   819.6 1681.65   829.4 1683.73   839.3 1683.38   898.5 1703.09   928.1 1716.78
#Mann= 3 , 0 , 0
       0      .1       0   526.6    .045       0   551.6      .1       0
Bank Sta=526.6,551.6
XS Rating Curve= 0 ,0
Exp/Cntr=0.3,0.1

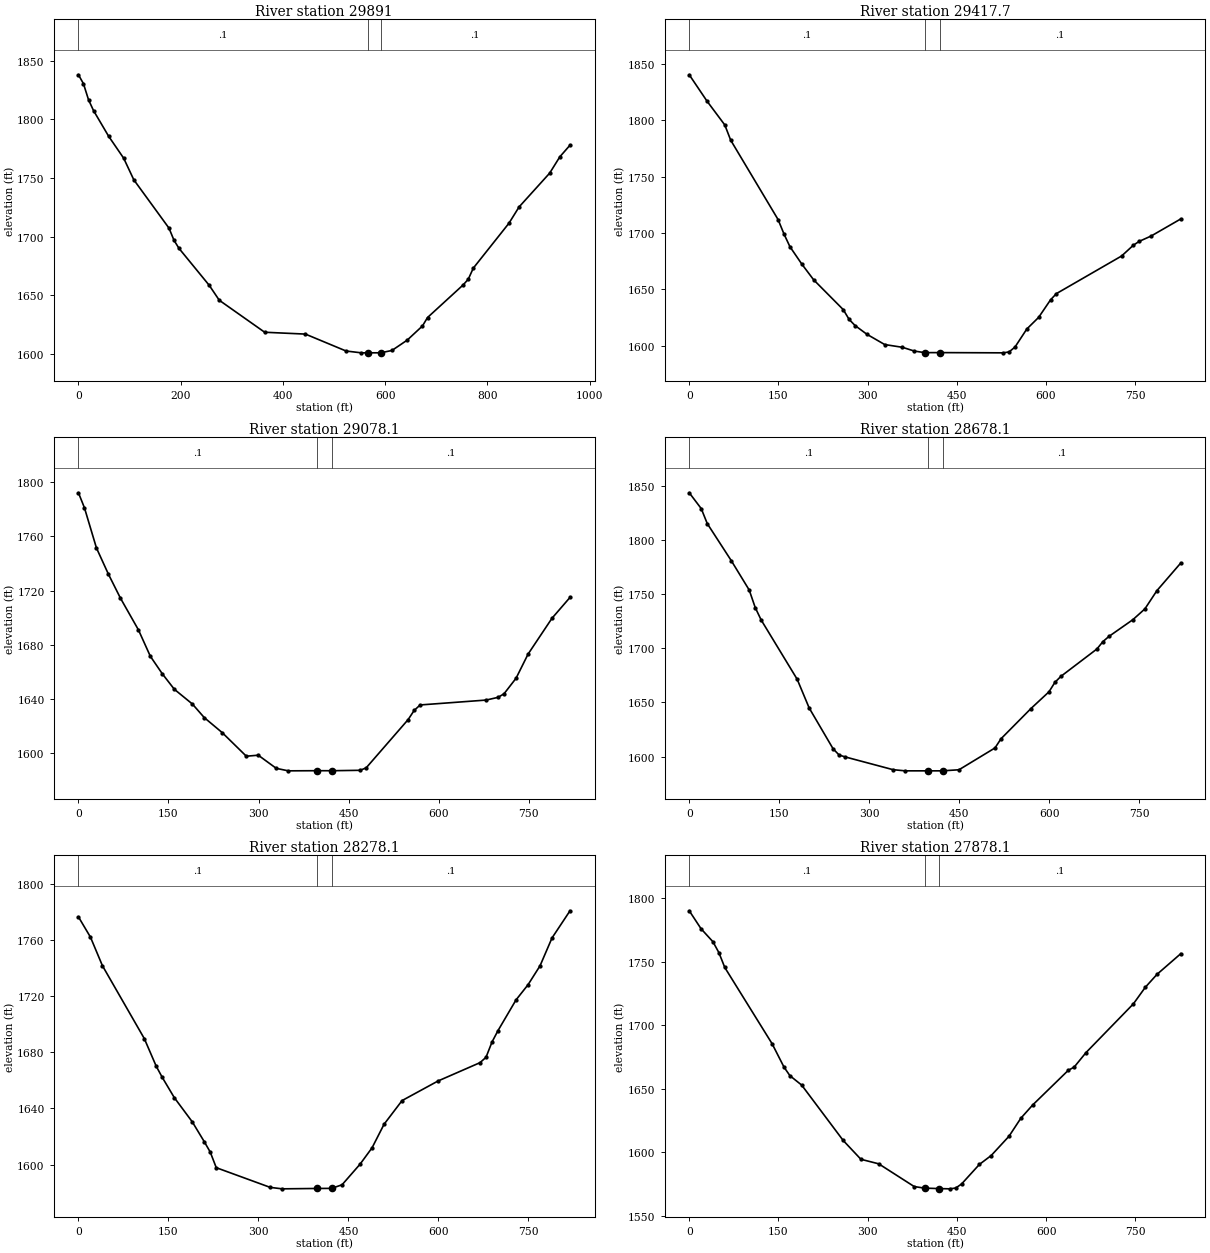
Type RM Length L Ch R = 1 ,29891   ,463.1,473.4,483.6
XS GIS Cut Line= 3
     1929442.104      292777.702     1929771.507      292676.881
     1930378.651      292788.574
#Sta/Elev= 30
       0 1837.95     9.8 1830.38    19.7 1816.71    29.5 1807.45      59 1785.62
    88.6 1766.78   108.3 1748.46   177.2 1707.22     187 1696.86   196.8 1689.96
   255.9  1658.5   275.6 1645.76   364.4  1618.5   444.1 1616.93   523.7  1602.5
   553.6 1600.95   566.2 1600.97   591.2 1600.98   613.3 1602.96   643.2 1611.76
   673.1 1623.86     683 1631.04   752.7 1658.84   762.7  1663.7   772.6 1673.16
   842.3 1711.41   862.2 1725.34     922 1754.12   941.9 1768.05   961.8 1777.95
#Mann= 3 , 0 , 0
       0      .1       0   566.2    .045       0   591.2      .1       0
Bank Sta=566.2,591.2
XS Rating Curve= 0 ,0
Exp/Cntr=0.3,0.1

Type RM Length L Ch R = 1 ,29417.7 ,341.4,339.2,337
XS GIS Cut Line= 2
     1929404.308       292867.08     1930102.849      293309.134
#Sta/Elev= 30
       0 1840.61    29.9 1817.17    59.8 1796.01    69.7  1782.5   149.4 1711.95
   159.4 1699.06   169.3 1687.86   189.2 1672.47   209.2 1658.43     259 1631.93
   268.9  1623.2   278.9 1617.78   298.8 1610.02   328.7  1600.9   358.6 1598.45
   378.5 1595.11   396.1 1593.72   421.1 1593.75   527.9 1593.54   537.8 1594.33
   547.8 1598.68   567.7 1614.73   587.6 1625.07   607.6 1640.65   617.5 1646.18
   727.1  1679.6     747 1689.23   756.9 1692.64   776.9 1697.38   826.7 1712.55
#Mann= 3 , 0 , 0
       0      .1       0   396.1    .045       0   421.1      .1       0
Bank Sta=396.1,421.1
XS Rating Curve= 0 ,0
Exp/Cntr=0.3,0.1

Type RM Length L Ch R = 1 ,29078.1 ,407.5,399.7,391.8
XS GIS Cut Line= 3
     1929208.701       293189.14     1929575.235       293371.74
     1929942.023      293553.833
#Sta/Elev= 30
       0  1792.2      10 1781.13      30 1751.46    49.9 1732.13    69.9 1714.46
    99.9    1691   119.8 1671.46   139.8 1658.47   159.8 1647.06   189.8 1636.21
   209.7 1626.13   239.7    1615   279.7 1597.65   299.6 1598.38   329.6 1588.68
   349.6 1586.84     397 1586.94     422 1586.92   469.4 1587.24   479.4 1589.06
   549.3  1624.7   559.3 1631.42   569.3  1635.5   679.2 1639.11   699.2 1641.12
   709.1 1643.78   729.1 1655.23   749.1 1673.05     789 1699.55     819 1714.94
#Mann= 3 , 0 , 0
       0      .1       0     397    .045       0     422      .1       0
Bank Sta=397,422
XS Rating Curve= 0 ,0
Exp/Cntr=0.3,0.1

Type RM Length L Ch R = 1 ,28678.1 ,390.3,399.7,409.2
XS GIS Cut Line= 3
     1929042.352      293673.624     1929445.239      293746.907
     1929848.671      293817.223
#Sta/Elev= 30
       0 1843.42      20  1828.8      30 1814.99    69.9 1780.88    99.9 1753.67
   109.9 1737.51   119.8 1726.04   179.8 1671.32   199.8 1644.81   239.7  1607.1
   249.7  1601.4   259.7 1599.66   339.6 1587.86   359.6  1586.8     397  1586.8
     422  1586.8   449.4 1587.79   509.4 1607.94   519.4 1616.39   569.3  1644.3
   599.3 1659.72   609.3 1668.53   619.2    1674   679.2 1699.26   689.2 1706.07
   699.2 1710.85   739.1 1726.31   759.1 1736.24   779.1 1753.08     819 1778.68
#Mann= 3 , 0 , 0
       0      .1       0     397    .045       0     422      .1       0
Bank Sta=397,422
XS Rating Curve= 0 ,0
Exp/Cntr=0.3,0.1

Type RM Length L Ch R = 1 ,28278.1 ,396.8,399.5,404
XS GIS Cut Line= 3
     1928962.812      293919.148     1929318.142      294122.572
     1929674.403      294325.181
#Sta/Elev= 30
       0 1776.36      20 1761.97      40  1741.6   109.8 1689.73   129.8 1669.94
   139.8 1662.07   159.8 1647.71   189.7 1630.52   209.7  1616.4   219.7 1608.98
   229.7 1597.88   319.6 1583.87   339.5 1582.83   396.9 1583.09   421.9 1583.16
   439.4 1585.73   469.4 1600.39   489.4 1612.05   509.4 1628.81   539.4 1645.63
   599.4 1659.59   669.3 1672.62   679.3 1676.44   689.3 1687.33   699.3 1695.45
   729.3 1717.26   749.3 1728.04   769.3 1741.51   789.3 1761.37   819.3 1780.69
#Mann= 3 , 0 , 0
       0      .1       0   396.9    .045       0   421.9      .1       0
Bank Sta=396.9,421.9
XS Rating Curve= 0 ,0
Exp/Cntr=0.3,0.1

Type RM Length L Ch R = 1 ,27878.1 ,391.4,399.3,405.7
XS GIS Cut Line= 3
      1928713.48      294172.514      1929045.94      294408.918
     1929371.286      294671.681
#Sta/Elev= 30
       0 1789.97    19.9  1775.8    39.8 1765.62    49.8 1757.07    59.7 1745.38
   139.3 1685.35   159.2 1667.05   169.2 1660.25     189 1652.84   258.7 1609.32
   288.5  1594.5   318.4 1590.94   378.1 1573.05   395.4 1571.82   420.4 1571.45
   437.8 1571.26   447.8 1571.88   457.7 1575.08   487.6 1590.45   507.5 1597.47
   537.4 1612.62   557.3 1626.79   577.2 1637.22     637 1664.47   646.9 1667.01
   666.8 1678.42   746.5 1716.79   766.4 1729.74   786.3 1740.04   826.2 1756.27
#Mann= 3 , 0 , 0
       0      .1       0   395.4    .045       0   420.4      .1       0
Bank Sta=395.4,420.4
XS Rating Curve= 0 ,0
Exp/Cntr=0.3,0.1

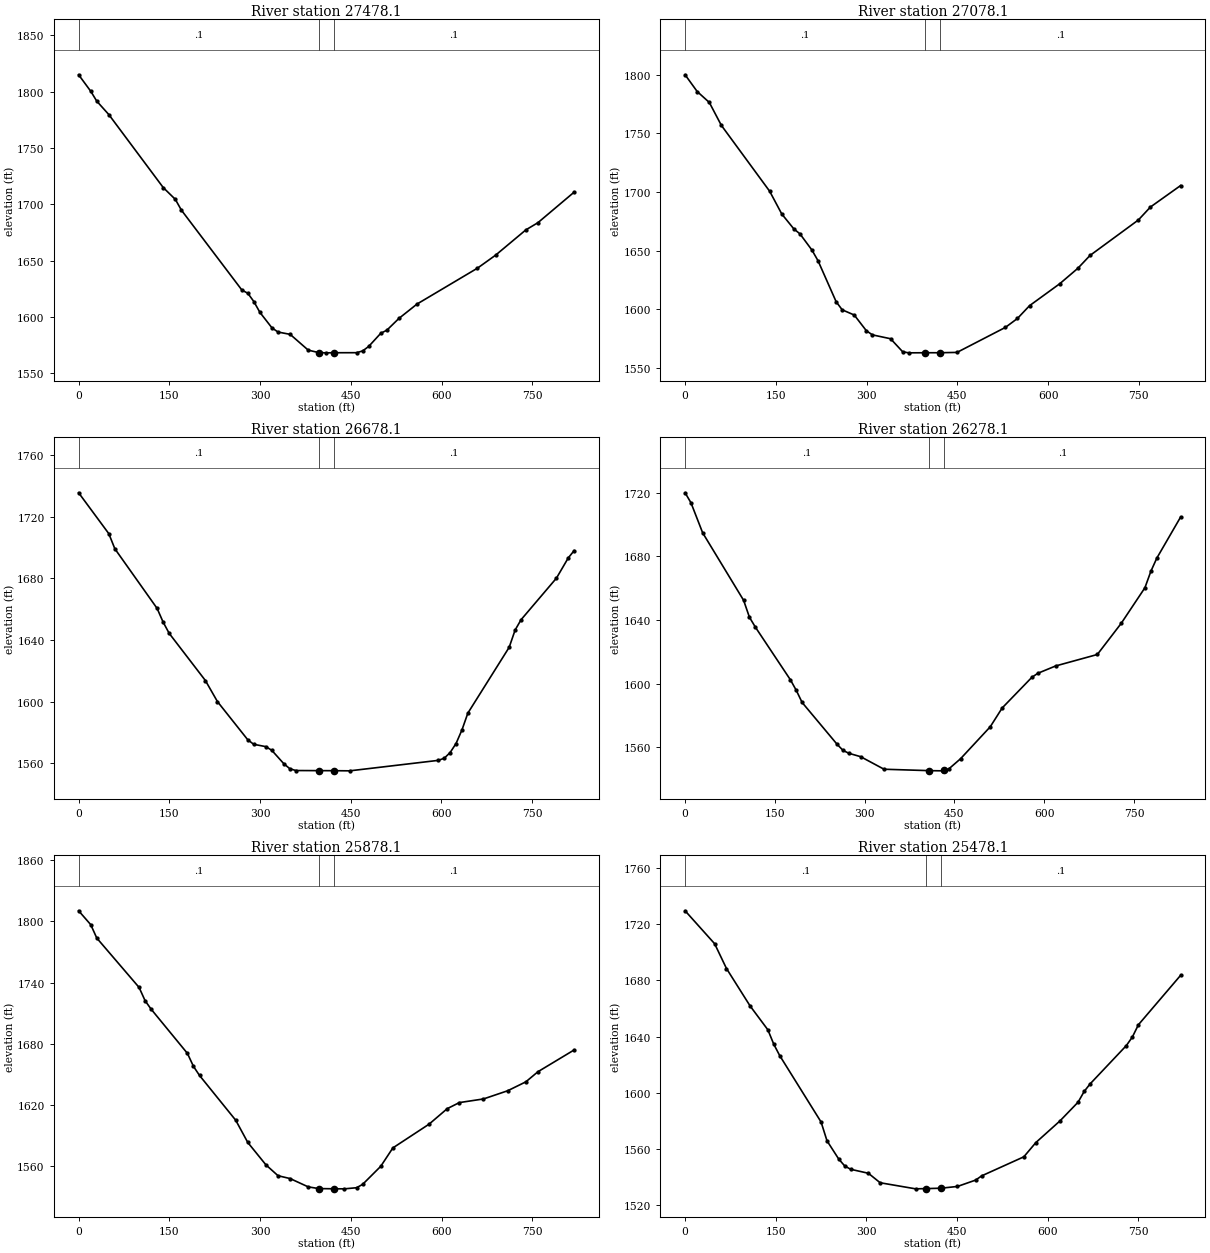
Type RM Length L Ch R = 1 ,27478.1 ,407.2,399.7,392.4
XS GIS Cut Line= 3
     1928498.033      294339.588     1928750.343      294662.125
     1929002.653      294984.662
#Sta/Elev= 30
       0 1815.04      20 1800.43      30 1791.61    49.9 1779.71   139.8 1714.93
   159.8 1704.46   169.8 1694.91   269.7 1624.02   279.7 1621.02   289.6 1613.71
   299.6 1604.12   319.6 1590.31   329.6 1586.66   349.6 1584.61   379.5 1570.59
     397 1568.39   409.5  1568.2     422 1568.29   459.4 1568.33   469.4 1569.89
   479.4 1573.88   499.4 1585.58   509.4  1588.3   529.4 1598.77   559.3 1611.52
   659.2 1643.38   689.2 1654.93   739.1 1677.33   759.1 1683.74     819 1710.88
#Mann= 3 , 0 , 0
       0      .1       0     397    .045       0     422      .1       0
Bank Sta=397,422
XS Rating Curve= 0 ,0
Exp/Cntr=0.3,0.1

Type RM Length L Ch R = 1 ,27078.1 ,409.8,399.7,389.4
XS GIS Cut Line= 3
     1928156.601      294719.583     1928487.121      294961.328
     1928815.131      295206.531
#Sta/Elev= 30
       0 1799.97      20 1785.69      40  1776.4    59.9 1756.88   139.8 1700.67
   159.8  1681.3   179.8 1668.56   189.8 1664.39   209.7 1650.52   219.7 1641.46
   249.7 1606.47   259.7 1599.62   279.6 1595.19   299.6 1581.79   309.6 1578.28
   339.6 1574.99   359.6 1563.88   369.5 1562.97     397 1563.05     422 1563.07
   449.4 1563.34   529.4 1584.66   549.3 1592.27   569.3 1603.17   619.2 1621.87
   649.2 1635.06   669.2 1645.96   749.1 1676.19   769.1 1687.26     819 1705.58
#Mann= 3 , 0 , 0
       0      .1       0     397    .045       0     422      .1       0
Bank Sta=397,422
XS Rating Curve= 0 ,0
Exp/Cntr=0.3,0.1

Type RM Length L Ch R = 1 ,26678.1 ,399,399.8,398.7
XS GIS Cut Line= 3
     1927913.506       295210.81     1928308.793      295317.168
     1928704.605      295425.514
#Sta/Elev= 30
       0 1735.66    49.9  1709.1    59.9 1699.28   129.8 1660.52   139.8 1651.59
   149.8  1644.3   209.7 1613.63   229.6 1599.96   279.6 1575.22   289.5 1572.21
   309.5 1570.69   319.5  1568.3   339.5 1559.54   349.4 1556.31   359.4 1555.15
   396.8 1555.08   421.8 1555.05   448.4 1554.95     595 1561.76   604.8 1563.15
   614.5 1566.82   624.3 1572.71   634.1 1581.55   643.8 1592.43   712.2 1635.24
     722 1646.43   731.8 1653.14   790.4  1680.2     810 1693.39   819.7 1698.09
#Mann= 3 , 0 , 0
       0      .1       0   396.8    .045       0   421.8      .1       0
Bank Sta=396.8,421.8
XS Rating Curve= 0 ,0
Exp/Cntr=0.3,0.1

Type RM Length L Ch R = 1 ,26278.1 ,403.8,399.5,397
XS GIS Cut Line= 3
     1927867.469      295594.028     1928270.349      295714.127
     1928667.516      295805.652
#Sta/Elev= 30
       0 1719.97     9.8  1713.7    29.3 1694.84    97.8 1652.37   107.5 1641.75
   117.3  1635.6     176 1602.41   185.8 1595.78   195.5  1588.2   254.2  1561.8
     264 1558.04   273.8 1556.23   293.3 1554.12   332.4 1546.23   407.9 1545.34
   430.3 1545.22   432.9 1545.51   440.3 1546.32   460.2  1552.8   509.9 1572.92
   529.8 1584.73   579.4 1603.99   589.4 1606.53   619.2 1611.14   688.8 1618.34
   728.6 1637.86   768.3 1660.27   778.3 1670.66   788.2 1678.91     828 1704.75
#Mann= 3 , 0 , 0
       0      .1       0   407.9    .045       0   432.9      .1       0
Bank Sta=407.9,432.9
XS Rating Curve= 0 ,0
Exp/Cntr=0.3,0.1

Type RM Length L Ch R = 1 ,25878.1 ,413.1,399.6,385.9
XS GIS Cut Line= 3
     1927711.203      296022.208     1928117.059      296076.569
      1928522.89      296132.091
#Sta/Elev= 30
       0 1810.46      20 1796.82      30 1783.66    99.9 1735.18   109.9 1722.08
   119.8 1713.84   179.8 1670.39   189.8 1657.65   199.8 1648.71   259.7 1604.68
   279.6 1582.87   309.6 1560.87   329.6 1550.21   349.6  1547.4   379.5 1539.25
     397 1537.56     422 1537.38   439.4 1537.32   459.4 1538.41   469.4 1541.69
   499.4 1559.47   519.4 1577.51   579.3 1600.87   609.3 1616.09   629.3 1622.04
   669.2 1625.62   709.2 1633.67   739.2 1642.42   759.2 1652.35   819.1 1673.78
#Mann= 3 , 0 , 0
       0      .1       0     397    .045       0     422      .1       0
Bank Sta=397,422
XS Rating Curve= 0 ,0
Exp/Cntr=0.3,0.1

Type RM Length L Ch R = 1 ,25478.1 ,429.4,432.5,435.7
XS GIS Cut Line= 3
     1927760.961      296612.507     1928146.167      296469.174
     1928529.187      296325.016
#Sta/Elev= 30
       0 1729.61    48.9 1706.15    68.5 1688.52   107.6 1661.86     137 1644.89
   146.8 1634.62   156.6 1626.53   225.1 1579.25   234.9 1565.87   254.4 1552.83
   264.2    1548     274 1545.61   303.4 1542.76   322.9 1536.01   381.6 1531.68
   398.5 1531.84   423.5 1532.13   450.9 1533.38   480.9  1537.9   490.9 1540.91
   560.7 1554.47   580.7 1564.65   620.6 1580.05   650.6  1593.4   660.6    1601
   670.5  1606.4   730.4 1633.65   740.4 1639.76   750.4 1648.48   820.3 1683.68
#Mann= 3 , 0 , 0
       0      .1       0   398.5    .045       0   423.5      .1       0
Bank Sta=398.5,423.5
XS Rating Curve= 0 ,0
Exp/Cntr=0.3,0.1