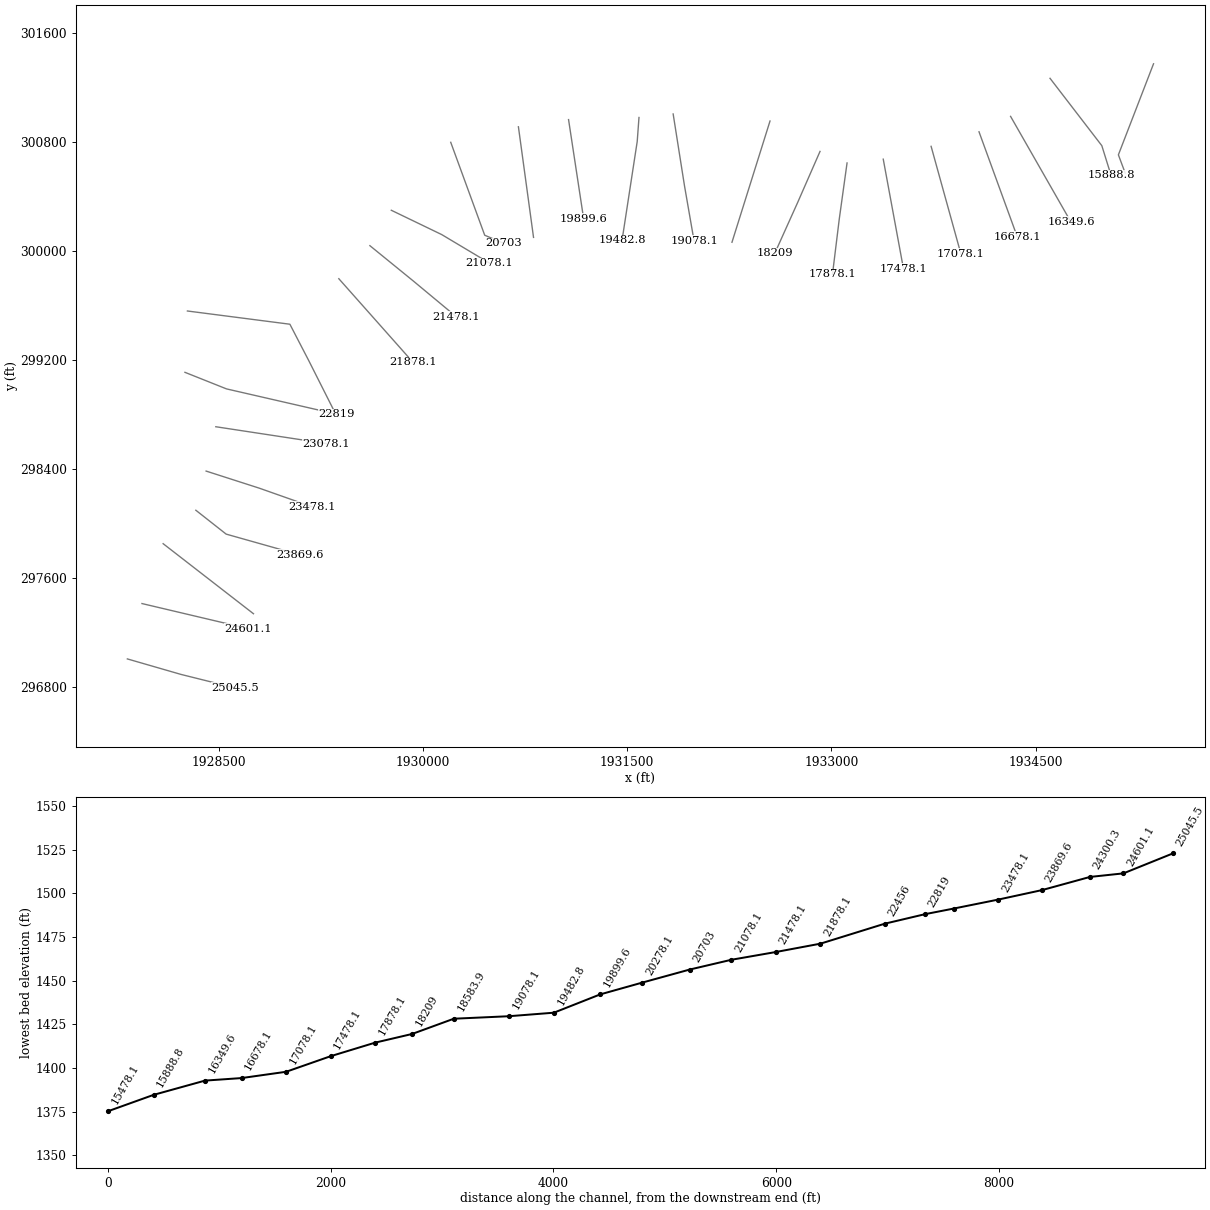
HEC-RAS study PnyCrk.prj: PnyCrk

--- PnyCrk.g01 (geometry) --- (continued)

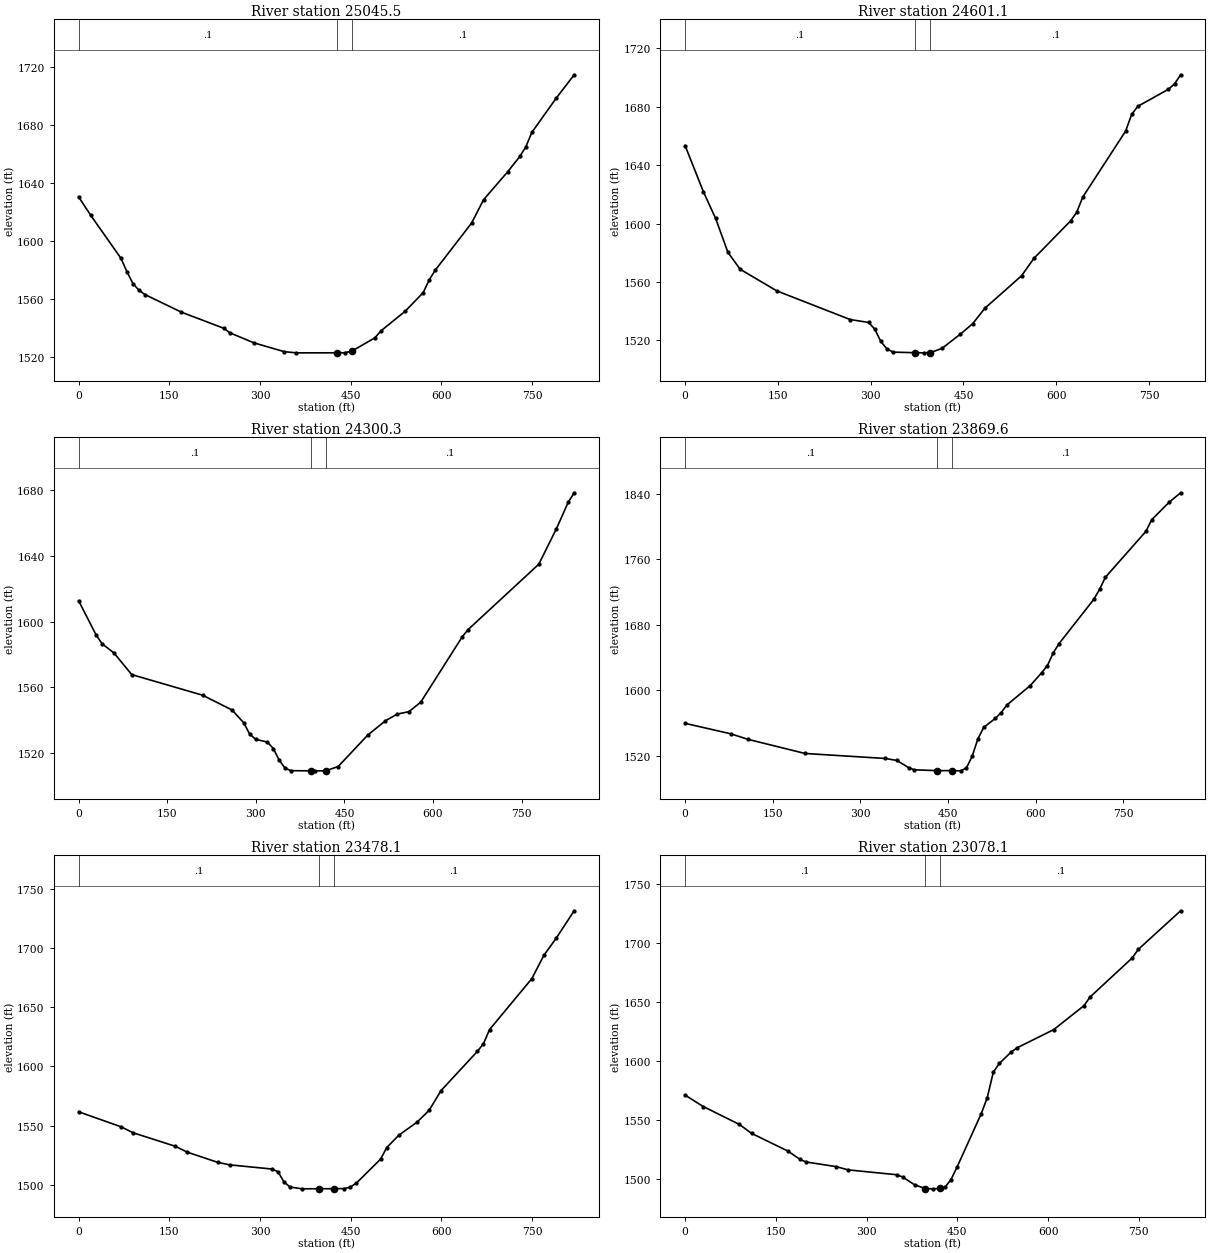
Type RM Length L Ch R = 1 ,25045.5 ,443.8,444.1,444.4
XS GIS Cut Line= 3
     1927830.664      297008.275     1928224.585      296894.539
     1928621.853      296795.574
#Sta/Elev= 30
       0 1630.35      20 1617.61      70    1588      80 1578.62      90 1570.48
     100 1565.91     110 1562.96     170 1550.89     240 1539.81     250  1536.7
     290 1529.74     340 1523.68     360 1522.88   426.7 1522.89     440 1522.95
   451.7 1524.05   489.9 1533.21   499.9 1538.02   539.8 1551.47   569.8 1564.39
   579.8 1573.21   589.8 1579.91   649.7 1612.24   669.6 1628.38   709.6 1647.69
   729.6 1658.19   739.5 1664.84   749.5 1674.82   789.5 1698.21   819.4 1714.45
#Mann= 3 , 0 , 0
       0      .1       0   426.7    .045       0   451.7      .1       0
Bank Sta=426.7,451.7
XS Rating Curve= 0 ,0
Exp/Cntr=0.3,0.1

Type RM Length L Ch R = 1 ,24601.1 ,312.5,300.7,289
XS GIS Cut Line= 2
      1927938.02      297414.467     1928717.604       297230.52
#Sta/Elev= 30
       0  1653.4    29.7 1621.65    49.4 1603.48    69.2  1580.3      89 1568.71
   148.3 1553.87     267 1534.23   296.7 1532.27   306.6 1527.66   316.4 1519.23
   326.3 1514.11   336.2 1511.94   371.6 1511.54   385.7 1511.45   396.6 1511.58
   415.3 1514.53     445 1524.27   464.8 1531.41   484.6 1542.01   543.9 1564.26
   563.7  1576.1     623 1601.79   632.9 1607.63   642.8 1618.16     712  1663.3
   721.9 1674.82   731.8 1680.32   781.2 1691.97   791.1 1695.68     801 1701.92
#Mann= 3 , 0 , 0
       0      .1       0   371.6    .045       0   396.6      .1       0
Bank Sta=371.6,396.6
XS Rating Curve= 0 ,0
Exp/Cntr=0.3,0.1

Type RM Length L Ch R = 1 ,24300.3 ,419.5,430,440.6
XS GIS Cut Line= 2
     1928093.495      297853.683     1928756.576      297339.799
#Sta/Elev= 30
       0 1612.65      30 1591.62      40 1586.45    59.9 1580.94    89.9 1567.82
   209.7 1555.33   259.7 1546.34   279.6 1538.54   289.6 1531.68   299.6 1528.55
   319.6 1526.84   329.6 1522.96   339.6 1515.79   349.5 1511.02   359.5 1509.49
   393.2 1509.41   399.5  1509.4   418.2 1509.41   439.4 1512.03   489.4 1531.08
   519.3 1539.78   539.3 1543.83   559.3 1545.34   579.2  1551.1   649.2 1590.65
   659.1 1595.07     779 1634.84   808.9 1656.41   828.9  1672.5   838.9  1678.2
#Mann= 3 , 0 , 0
       0      .1       0   393.2    .045       0   418.2      .1       0
Bank Sta=393.2,418.2
XS Rating Curve= 0 ,0
Exp/Cntr=0.3,0.1

Type RM Length L Ch R = 1 ,23869.6 ,392.1,391.1,389.3
XS GIS Cut Line= 3
     1928333.524      298099.003     1928556.078      297923.913
     1929099.722       297770.69
#Sta/Elev= 30
       0  1559.8    78.1 1547.04   107.4 1540.33   205.1 1523.07   342.6 1516.95
   362.4 1514.53   382.3 1505.85   392.2 1503.14     431 1502.11     456 1502.13
   471.4 1501.87   481.4  1505.3   491.3 1519.77   501.2 1541.17   511.1 1554.93
   530.9 1565.84   540.8 1572.79   550.7 1582.24   590.4 1605.66   610.2 1621.52
   620.1 1630.34     630 1645.75   639.9    1657   699.4 1711.03   709.3 1723.23
   719.2 1737.92   788.5 1793.86   798.4 1808.09   828.2 1829.38     848    1841
#Mann= 3 , 0 , 0
       0      .1       0     431    .045       0     456      .1       0
Bank Sta=431,456
XS Rating Curve= 0 ,0
Exp/Cntr=0.3,0.1

Type RM Length L Ch R = 1 ,23478.1 ,395.5,399.9,405
XS GIS Cut Line= 3
      1928408.93      298386.374     1928798.777      298261.179
     1929185.443      298124.896
#Sta/Elev= 30
       0 1561.67    69.9 1549.01    89.9 1543.95   159.8 1532.48   179.8 1527.46
   229.7 1518.93   249.7 1516.77   319.6 1513.22   329.6 1510.94   339.6 1502.27
   349.5 1498.03   369.5 1496.46     397 1496.56     422 1496.56   439.4 1496.69
   449.4 1497.97   459.4 1501.38   499.4 1521.67   509.4 1531.36   529.4 1541.84
   559.4 1552.82   579.4  1562.8   599.4 1579.68   659.4 1612.83   669.4 1619.25
   679.4  1631.2   749.4 1674.36   769.4 1694.17   789.4 1708.34   819.4 1731.78
#Mann= 3 , 0 , 0
       0      .1       0     397    .045       0     422      .1       0
Bank Sta=397,422
XS Rating Curve= 0 ,0
Exp/Cntr=0.3,0.1

Type RM Length L Ch R = 1 ,23078.1 ,260.6,259.1,257.6
XS GIS Cut Line= 3
     1928480.172      298711.706      1928885.01      298650.095
     1929289.849      298588.485
#Sta/Elev= 30
       0 1570.93      30  1561.2    89.9 1545.98   109.9 1538.41   169.8 1523.43
   189.8 1516.38   199.8 1514.14   249.7 1510.18   269.7 1507.41   349.6  1503.3
   359.6 1501.35   379.5 1494.68     397  1491.6   409.5 1491.32     422 1491.67
   429.5 1492.69   439.5 1499.21   449.4 1509.72   489.4 1555.09   499.4  1568.8
   509.4 1590.42   519.4 1597.79   539.3 1607.72   549.3 1611.24   609.3 1626.54
   659.2 1646.86   669.2 1654.15   739.1 1687.46   749.1 1694.71     819 1727.44
#Mann= 3 , 0 , 0
       0      .1       0     397    .045       0     422      .1       0
Bank Sta=397,422
XS Rating Curve= 0 ,0
Exp/Cntr=0.3,0.1

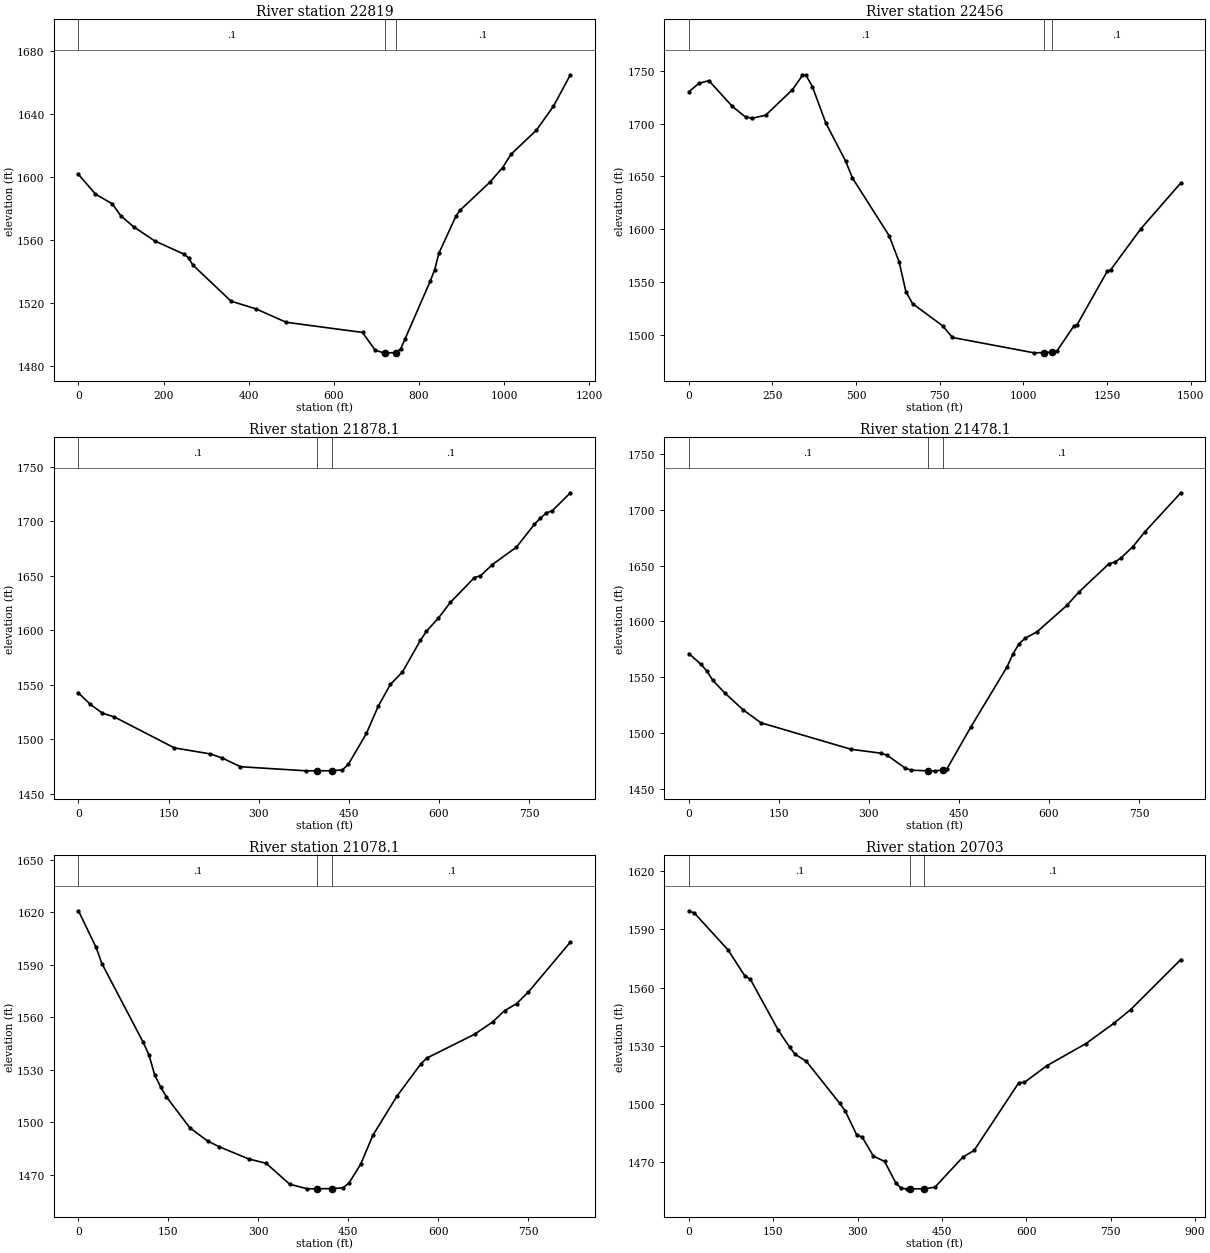
Type RM Length L Ch R = 1 ,22819   ,387,362.3,337.5
XS GIS Cut Line= 3
     1928253.514      299110.896     1928558.664      298989.353
     1929365.115      298804.306
#Sta/Elev= 30
       0 1601.49    39.8    1589    79.6 1582.74    99.5 1575.14   129.4 1568.23
   179.2 1559.19   248.8  1550.7   258.8 1548.37   268.7  1543.9   358.4 1520.95
   418.2  1515.9     488  1507.5   667.4 1501.04   697.3 1489.74   717.2 1488.08
   720.5 1488.09   745.5 1488.18   757.1 1490.64   767.1 1496.74   826.9 1533.87
   836.9 1540.82   846.8 1551.34   886.7  1574.8   896.7 1578.71   966.5 1596.46
   996.4 1605.73  1016.3 1614.23  1076.1 1629.61    1116 1644.78  1155.9 1664.77
#Mann= 3 , 0 , 0
       0      .1       0   720.5    .045       0   745.5      .1       0
Bank Sta=720.5,745.5
XS Rating Curve= 0 ,0
Exp/Cntr=0.3,0.1

Type RM Length L Ch R = 1 ,22456   ,570.5,577.5,584.7
XS GIS Cut Line= 4
     1928271.616      299560.863     1929023.913      299463.814
     1929163.229      299195.282     1929347.683      298829.683
#Sta/Elev= 30
       0 1730.39    29.9  1738.3    59.9 1740.94   129.8 1716.47   169.7 1706.32
   189.6 1705.25   229.6 1708.11   309.4 1732.23   339.3 1745.84   349.3 1746.47
   369.3 1735.23   409.2 1700.82   469.1 1664.22     489 1648.49   598.8 1593.69
   628.8 1568.64   648.7 1540.71   668.7  1529.3   758.5 1508.27   787.8 1497.21
  1031.8 1482.62  1060.7 1482.86  1085.7 1483.25    1101 1484.65  1150.9  1508.2
  1160.9  1509.5  1250.8  1560.1  1260.8 1561.38  1350.7 1600.21  1470.5 1643.86
#Mann= 3 , 0 , 0
       0      .1       0  1060.7    .045       0  1085.7      .1       0
Bank Sta=1060.7,1085.7
XS Rating Curve= 0 ,0
Exp/Cntr=0.3,0.1

Type RM Length L Ch R = 1 ,21878.1 ,394.9,399.4,403.5
XS GIS Cut Line= 3
     1929383.217      299797.762     1929655.134      299491.574
     1929927.052      299185.386
#Sta/Elev= 30
       0 1542.66      20 1532.07      40 1524.09    59.9 1520.59   159.8 1492.21
   219.7 1486.69   239.7 1482.86   269.7 1474.96   379.5 1471.18     397 1471.24
     422 1471.26   439.5 1472.08   449.4 1477.22   479.4 1505.53   499.4 1530.85
   519.4 1550.54   539.3 1561.81   569.3  1590.9   579.3 1599.24   599.3 1611.39
   619.2 1625.73   659.2 1648.55   669.2 1650.15   689.2 1660.49   729.1 1676.42
   759.1 1697.38   769.1  1703.1     779 1707.81     789 1709.92     819 1726.31
#Mann= 3 , 0 , 0
       0      .1       0     397    .045       0     422      .1       0
Bank Sta=397,422
XS Rating Curve= 0 ,0
Exp/Cntr=0.3,0.1

Type RM Length L Ch R = 1 ,21478.1 ,393.3,399.7,404
XS GIS Cut Line= 3
      1929611.37       300040.07     1929929.674       299781.29
     1930244.629      299519.794
#Sta/Elev= 30
       0 1571.32      20 1561.81      30 1555.63      40 1547.27      60    1536
      90 1521.19   120.1 1509.38   270.2 1485.68   320.2 1482.19   330.2 1480.39
   360.2 1468.96   370.2 1467.01   397.7 1466.44   410.2 1466.41   422.7  1467.1
   430.2 1468.41   470.1 1505.88     530  1559.3     540 1571.02     550 1580.03
     560 1584.91     580 1590.74   629.9 1614.43   649.8 1626.34   699.8 1651.55
   709.8 1653.16   719.7 1656.64   739.7  1666.9   759.7 1680.16   819.6  1715.1
#Mann= 3 , 0 , 0
       0      .1       0   397.7    .045       0   422.7      .1       0
Bank Sta=397.7,422.7
XS Rating Curve= 0 ,0
Exp/Cntr=0.3,0.1

Type RM Length L Ch R = 1 ,21078.1 ,396.4,375.1,356.2
XS GIS Cut Line= 3
     1929768.547      300299.915     1930138.604      300121.501
     1930490.096      299911.778
#Sta/Elev= 30
       0 1620.81    29.3 1599.99    39.1 1590.63   107.6 1545.88   117.4 1538.64
   127.2 1526.92   136.9 1520.22   146.7 1514.49   185.8 1496.78   215.2 1489.31
   234.8 1485.99   283.7 1479.05     313 1476.53   352.1 1464.61   381.5 1461.96
   398.3    1462   423.3 1462.12   440.8 1462.52   450.8 1465.19   470.7 1476.18
   490.7 1492.48   530.6 1514.76   570.6 1533.26   580.5 1536.62   660.4 1550.27
   690.4 1557.28   710.3 1563.76   730.3 1567.73   750.2 1574.46   820.1 1602.96
#Mann= 3 , 0 , 0
       0      .1       0   398.3    .045       0   423.3      .1       0
Bank Sta=398.3,423.3
XS Rating Curve= 0 ,0
Exp/Cntr=0.3,0.1

Type RM Length L Ch R = 1 ,20703   ,430.5,424.6,418.7
XS GIS Cut Line= 3
     1930204.813      300798.618     1930454.216      300116.857
     1930591.155      300058.563
#Sta/Elev= 30
       0 1599.62     9.9 1598.42    69.6 1579.49    99.4 1566.12   109.4 1564.31
   159.1 1538.05     179 1529.46     189 1525.66   208.8 1522.09   268.5 1500.34
   278.4 1496.27   298.3 1484.24   308.3 1482.96   328.2 1473.19   348.1 1470.47
     368 1459.38   377.9  1456.6   387.8 1456.35     394 1456.37     419 1456.36
   437.6 1457.21   487.3 1472.73   507.2 1476.14   586.7 1511.02   596.7  1511.2
   636.4 1519.76   706.1 1531.19   755.7 1541.64   785.5  1548.7   874.8 1574.51
#Mann= 3 , 0 , 0
       0      .1       0     394    .045       0     419      .1       0
Bank Sta=394,419
XS Rating Curve= 0 ,0
Exp/Cntr=0.3,0.1

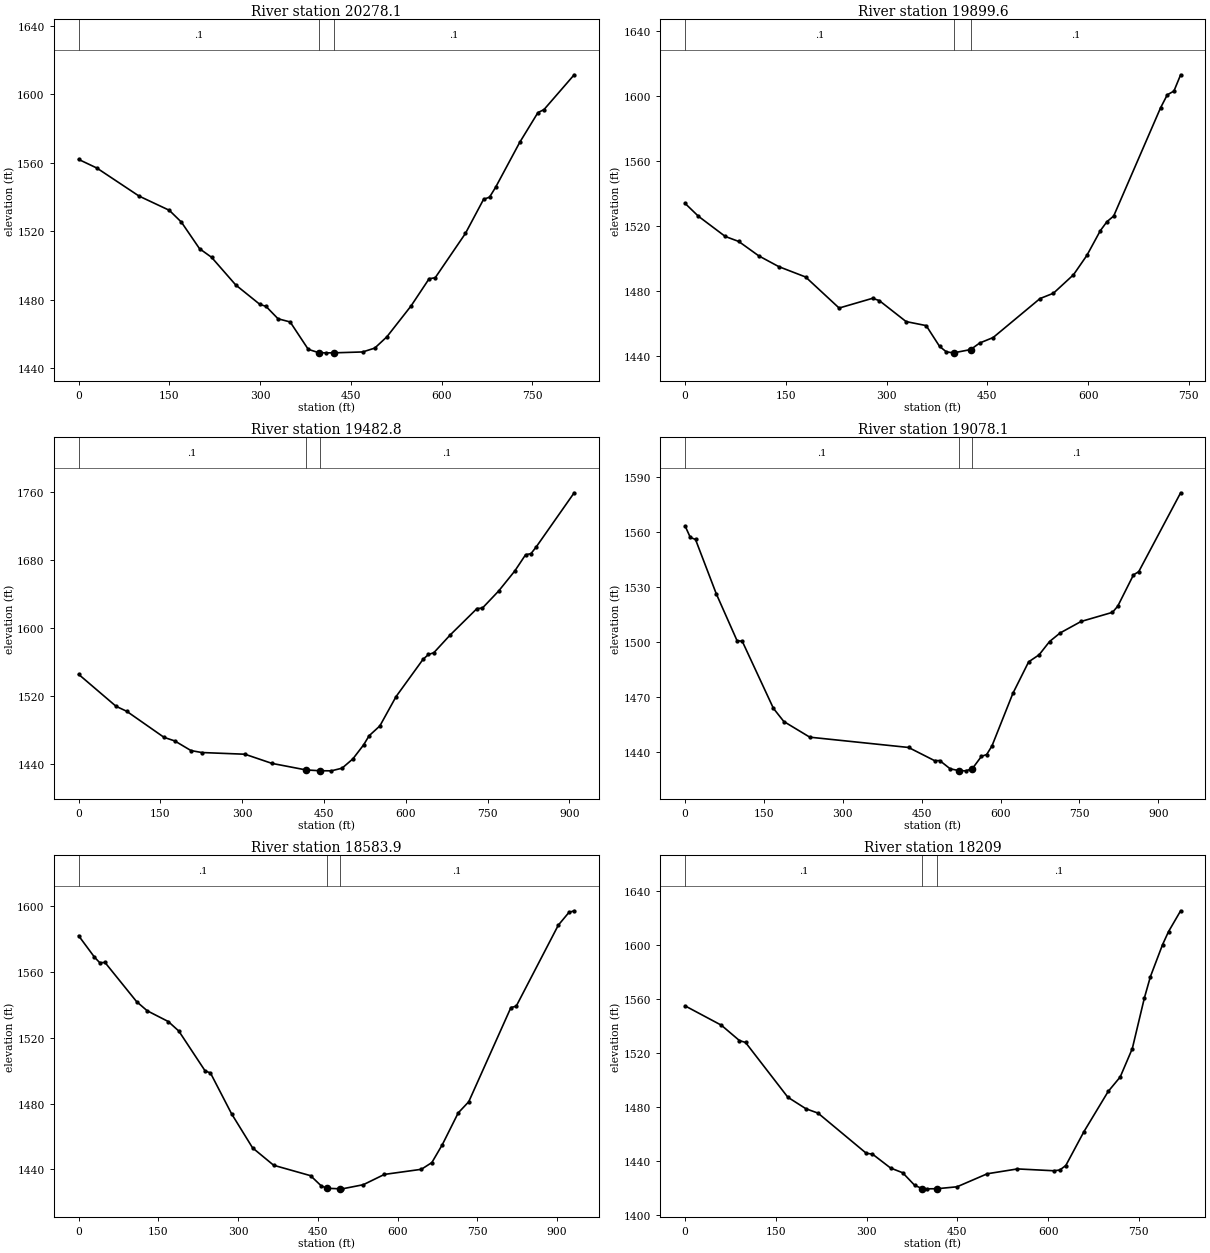
Type RM Length L Ch R = 1 ,20278.1 ,377.9,378.3,378.8
XS GIS Cut Line= 3
     1930701.713      300912.328     1930757.204      300506.605
     1930812.694      300100.882
#Sta/Elev= 30
       0 1561.95      30 1556.93    99.9 1540.51   149.8 1532.22   169.8 1525.31
   199.8 1509.78   219.7 1504.74   259.7 1488.55   299.6  1477.2   309.6 1476.08
   329.6  1468.8   349.6 1466.95   379.5 1450.95     397 1448.97   409.5  1448.9
     422  1448.9   469.4 1449.42   489.4 1451.67   509.4 1458.25   549.3 1476.26
   579.3 1492.22   589.3 1492.78   639.2 1518.65   669.2 1538.57   679.2 1539.93
   689.2 1545.69   729.1 1571.97   759.1 1589.31   769.1 1591.06     819 1611.41
#Mann= 3 , 0 , 0
       0      .1       0     397    .045       0     422      .1       0
Bank Sta=397,422
XS Rating Curve= 0 ,0
Exp/Cntr=0.3,0.1

Type RM Length L Ch R = 1 ,19899.6 ,424.6,416.5,408.5
XS GIS Cut Line= 2
     1931069.845      300965.117     1931180.887      300235.814
#Sta/Elev= 30
       0 1533.87    19.9 1525.96    59.8 1513.58    79.8 1510.52   109.7 1501.66
   139.6 1495.03   179.4  1488.7   229.3 1469.63   279.1 1475.62   289.1  1474.2
     329 1461.32   358.9 1458.85   378.8 1446.11   388.8 1442.77   398.8 1442.13
     400 1442.14     425 1444.14   438.6 1448.17   458.6 1451.53   528.4 1475.46
   548.3 1478.72   578.2 1490.07   598.1 1501.94   618.1  1517.1     628 1522.66
     638  1526.1   707.8 1592.54   717.8 1600.53   727.7 1602.84   737.7 1612.84
#Mann= 3 , 0 , 0
       0      .1       0     400    .045       0     425      .1       0
Bank Sta=400,425
XS Rating Curve= 0 ,0
Exp/Cntr=0.3,0.1

Type RM Length L Ch R = 1 ,19482.8 ,395.9,404.5,413.6
XS GIS Cut Line= 3
     1931586.892      300980.587     1931573.962      300804.738
     1931462.763      300080.652
#Sta/Elev= 30
       0 1545.09    68.6 1507.54    88.2 1501.65   156.7 1470.98   176.3  1466.8
     206 1455.49   225.8 1453.17     305 1451.17   354.5 1440.41   416.8 1432.73
   441.8 1431.77   463.4 1431.64   483.2 1434.77     503 1445.69   522.8 1462.23
   532.7 1472.84   552.5 1484.44   582.2  1518.9   631.7 1562.71   641.6 1568.42
   651.5 1570.51   681.2 1591.18   730.7 1622.46   740.6 1622.97   770.3 1642.99
     800 1666.61   819.8  1685.7   829.7 1687.01   839.6 1695.15   908.9 1758.52
#Mann= 3 , 0 , 0
       0      .1       0   416.8    .045       0   441.8      .1       0
Bank Sta=416.8,441.8
XS Rating Curve= 0 ,0
Exp/Cntr=0.3,0.1

Type RM Length L Ch R = 1 ,19078.1 ,506.5,493.8,480.6
XS GIS Cut Line= 3
     1931837.736      301006.447     1931920.987      300479.269
     1931991.028      300076.504
#Sta/Elev= 30
       0 1563.29     9.9 1557.03    19.8 1555.93    59.3 1526.26    98.8 1500.68
   108.7 1500.36     168 1463.72   187.8 1456.54   237.2 1447.99     425 1442.38
   474.4  1435.2   484.3 1435.23   504.1 1430.74   521.2 1429.71   533.7 1429.62
   546.2 1430.77   563.6 1437.51   573.6 1438.53   583.6 1443.18   623.4 1471.89
   653.4 1489.11   673.3 1492.95   693.2  1500.2   713.2 1504.86   753.1 1511.15
   812.9 1516.14   822.9 1519.51   852.8 1536.59   862.8 1538.34   942.5  1581.4
#Mann= 3 , 0 , 0
       0      .1       0   521.2    .045       0   546.2      .1       0
Bank Sta=521.2,546.2
XS Rating Curve= 0 ,0
Exp/Cntr=0.3,0.1

Type RM Length L Ch R = 1 ,18583.9 ,377.7,374.7,371.5
XS GIS Cut Line= 2
     1932548.891      300954.727     1932269.601      300065.136
#Sta/Elev= 30
       0 1581.89    29.8 1568.89    39.7 1565.53    49.6 1565.66   109.1 1541.87
     129 1536.33   168.6  1529.8   188.5 1524.01   238.1 1499.76     248 1498.58
   287.7 1473.81   327.3 1453.07     367  1442.5   436.4 1436.18   456.3 1430.04
   467.3 1428.52   492.3 1428.21     496 1428.19   535.6 1430.69   575.3 1436.95
   644.8 1440.05   664.6 1444.14   684.4 1455.07   714.2  1474.3     734 1481.07
   813.4 1538.31   823.3 1539.06   902.6 1588.34   922.5 1596.04   932.4 1597.05
#Mann= 3 , 0 , 0
       0      .1       0   467.3    .045       0   492.3      .1       0
Bank Sta=467.3,492.3
XS Rating Curve= 0 ,0
Exp/Cntr=0.3,0.1

Type RM Length L Ch R = 1 ,18209   ,323.3,330.9,339.1
XS GIS Cut Line= 3
     1932915.991      300731.654     1932751.646      300356.585
     1932583.355      299983.234
#Sta/Elev= 30
       0 1555.03    59.9 1540.72    89.9  1529.3    99.9 1527.93   169.8 1487.34
   199.8 1478.78   219.7 1475.56   299.6 1445.75   309.6 1445.22   339.6 1434.88
   359.6 1431.37   379.5 1422.04   391.5 1419.68   399.5 1419.45   416.5 1419.55
   449.4 1420.96   499.4 1430.62   549.3 1434.21   609.3 1432.85   619.2 1433.38
   629.2 1436.73   659.2 1461.85   699.2 1491.59   719.1 1502.34   739.1 1523.35
   759.1 1560.97   769.1 1576.79   789.1  1600.4     799  1610.1     819 1625.51
#Mann= 3 , 0 , 0
       0      .1       0   391.5    .045       0   416.5      .1       0
Bank Sta=391.5,416.5
XS Rating Curve= 0 ,0
Exp/Cntr=0.3,0.1

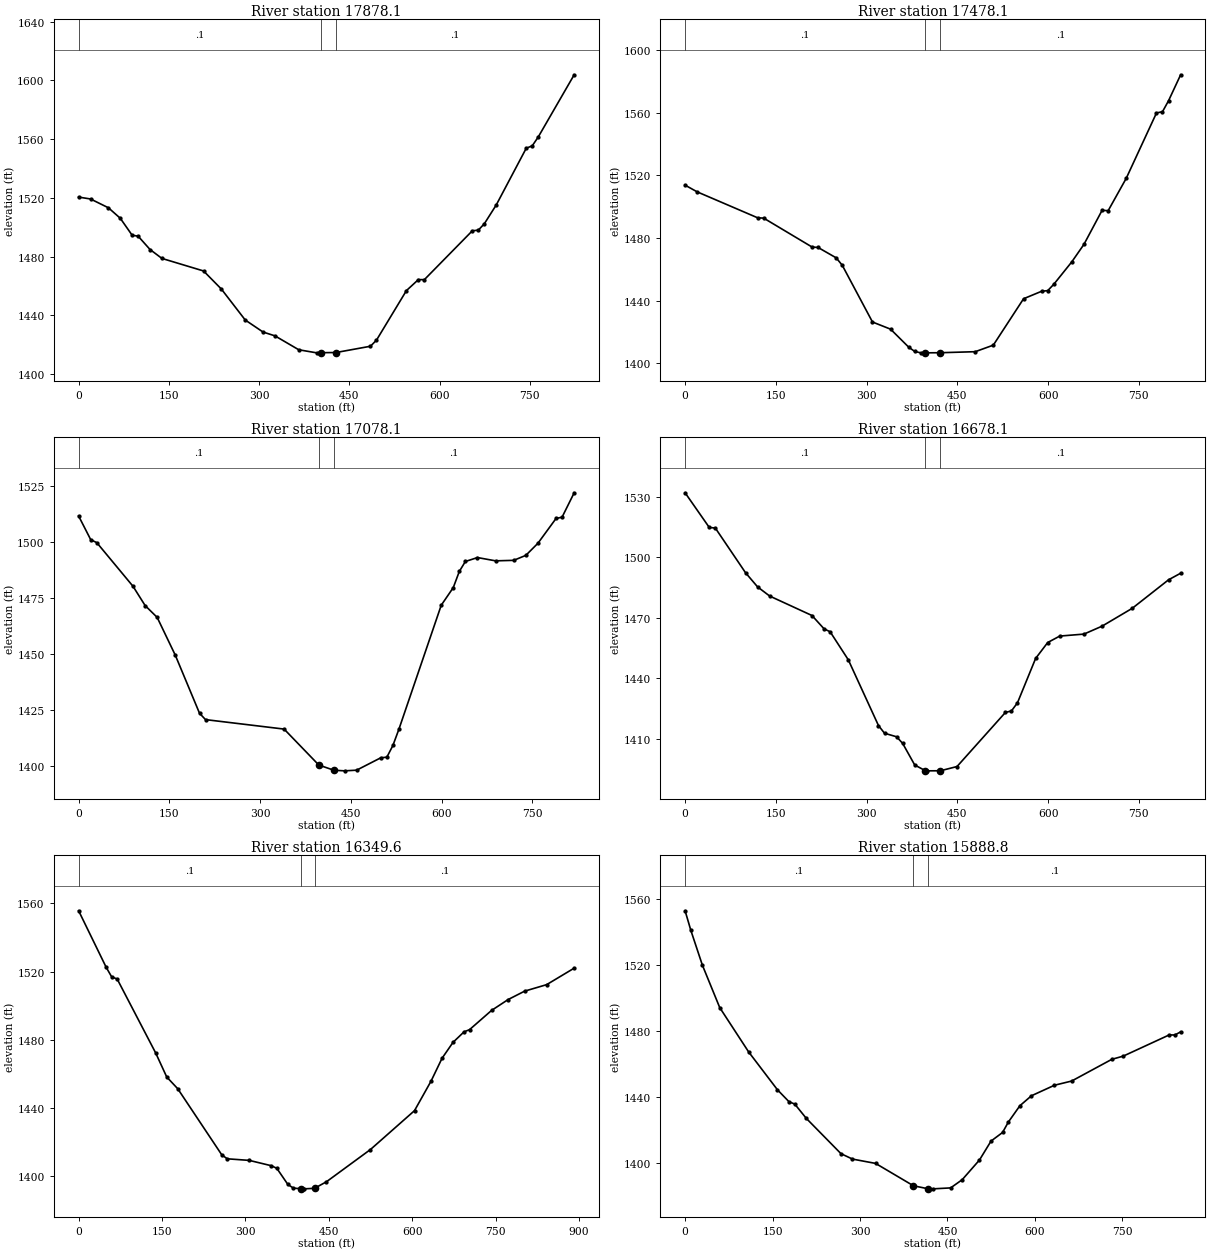
Type RM Length L Ch R = 1 ,17878.1 ,391.1,400,408.4
XS GIS Cut Line= 3
     1933114.465       300646.98     1933057.289       300235.48
     1933007.499      299830.077
#Sta/Elev= 30
       0  1520.5    19.8 1519.22    49.5 1513.23    69.2 1506.11      89 1494.53
    98.9 1493.92   118.7 1484.83   138.5 1478.76   207.7 1470.22   237.4 1457.88
     277 1436.84   306.6 1428.66   326.4 1426.06     366 1416.59   395.7  1414.5
     403 1414.59     428 1414.72   485.2 1418.99   495.2 1423.13     545 1456.86
   564.9 1464.36   574.8  1464.3   654.6 1497.58   664.5 1497.99   674.5 1502.33
   694.4 1515.19   744.2 1553.75   754.2 1555.41   764.1 1561.37   823.9 1603.75
#Mann= 3 , 0 , 0
       0      .1       0     403    .045       0     428      .1       0
Bank Sta=403,428
XS Rating Curve= 0 ,0
Exp/Cntr=0.3,0.1

Type RM Length L Ch R = 1 ,17478.1 ,397.6,400,402.4
XS GIS Cut Line= 3
     1933380.168      300674.813     1933454.531      300272.065
      1933528.83      299869.408
#Sta/Elev= 30
       0 1513.68      20  1509.4   119.9 1492.86   129.9 1492.65   209.8 1474.22
   219.8 1473.93   249.7 1467.32   259.7 1462.61   309.7 1426.39   339.6 1421.83
   369.6 1410.34   379.6  1407.6   389.6 1406.73   397.1 1406.73   422.1 1406.81
   479.5 1407.46   509.4 1411.64   559.4 1441.23   589.3 1446.01   599.3  1446.4
   609.3 1450.42   639.2  1464.8   659.2 1475.92   689.2 1497.64   699.2 1497.39
   729.1 1518.06   779.1 1559.75     789 1560.52     799 1567.52     819 1584.08
#Mann= 3 , 0 , 0
       0      .1       0   397.1    .045       0   422.1      .1       0
Bank Sta=397.1,422.1
XS Rating Curve= 0 ,0
Exp/Cntr=0.3,0.1

Type RM Length L Ch R = 1 ,17078.1 ,397.8,400,402.2
XS GIS Cut Line= 3
     1933731.575      300768.849        1933841.       300374.24
     1933950.426      299979.631
#Sta/Elev= 30
       0 1511.56      20 1500.99      30 1499.68    89.9 1480.18   109.9 1471.59
   129.8 1466.31   159.8 1449.41   199.8 1423.51   209.7 1420.67   339.6 1416.44
     397 1400.38     422 1398.07   439.5  1397.8   459.4 1398.09   499.4 1403.63
   509.4 1403.89   519.4 1409.12   529.4 1416.43   599.3 1471.74   619.2 1479.61
   629.2 1486.85   639.2 1491.27   659.2 1493.02   689.2 1491.55   719.1 1491.78
   739.1    1494   759.1  1499.4     789 1510.46     799 1511.05     819 1521.94
#Mann= 3 , 0 , 0
       0      .1       0     397    .045       0     422      .1       0
Bank Sta=397,422
XS Rating Curve= 0 ,0
Exp/Cntr=0.3,0.1

Type RM Length L Ch R = 1 ,16678.1 ,323.9,328.5,333.2
XS GIS Cut Line= 3
     1934083.263      300875.531     1934223.525      300490.801
     1934363.787      300106.072
#Sta/Elev= 30
       0 1531.97      40 1514.77    49.9 1514.52    99.9 1492.35   119.8 1485.34
   139.8  1480.8   209.7 1471.16   229.7 1464.55   239.7 1463.11   269.7 1449.23
   319.6 1416.64   329.6 1412.83   349.6 1411.07   359.6 1407.79   379.5  1397.1
     397 1394.28   399.5  1394.2     422 1394.24   449.4 1396.33   529.4 1423.14
   539.3 1423.86   549.3 1427.89   579.3 1449.88   599.3 1457.78   619.2 1460.97
   659.2 1461.95   689.2 1465.89   739.1 1474.74     799 1488.85     819 1492.11
#Mann= 3 , 0 , 0
       0      .1       0     397    .045       0     422      .1       0
Bank Sta=397,422
XS Rating Curve= 0 ,0
Exp/Cntr=0.3,0.1

Type RM Length L Ch R = 1 ,16349.6 ,457,460.7,464.4
XS GIS Cut Line= 2
     1934315.014      300988.683     1934757.351      300215.125
#Sta/Elev= 30
       0 1555.69    49.5 1522.59    59.4 1516.97    69.3  1515.7   138.6 1472.34
   158.4  1458.3   178.2 1451.41   257.4 1412.67   267.3 1410.34   306.9 1409.41
   346.5 1406.29   356.4 1404.76   376.2 1395.34   386.1 1393.17   399.2 1392.81
   405.9 1392.74   424.2 1393.05   445.6 1396.88   524.8 1415.79     604 1438.57
   633.7 1455.84   653.5 1469.26   673.3 1478.61   693.1 1484.75     703 1486.04
   742.6 1497.31   772.3 1503.66     802 1508.59   841.6  1512.4   891.1 1522.07
#Mann= 3 , 0 , 0
       0      .1       0   399.2    .045       0   424.2      .1       0
Bank Sta=399.2,424.2
XS Rating Curve= 0 ,0
Exp/Cntr=0.3,0.1

Type RM Length L Ch R = 1 ,15888.8 ,438.4,410.1,381.7
XS GIS Cut Line= 3
     1934604.592      301267.991     1934984.921      300773.705
     1935052.196      300557.742
#Sta/Elev= 30
       0 1553.07     9.9 1541.15    29.7 1520.07    59.4 1494.41   108.9 1467.59
   158.4 1444.61   178.2 1437.38   188.1 1435.94   207.9 1427.28   267.3 1405.91
   287.1 1402.62   326.7    1400   391.6 1386.45   416.6 1384.64   425.7 1384.59
   455.4 1385.16   475.2 1390.11   504.9 1402.07   524.7 1413.52   544.5 1418.75
   554.4 1425.05   574.2 1434.94     594 1440.98   633.5 1447.36     663 1449.91
   731.9 1463.07   751.5 1465.01   830.2 1477.83     840 1477.82   849.9  1479.7
#Mann= 3 , 0 , 0
       0      .1       0   391.6    .045       0   416.6      .1       0
Bank Sta=391.6,416.6
XS Rating Curve= 0 ,0
Exp/Cntr=0.3,0.1

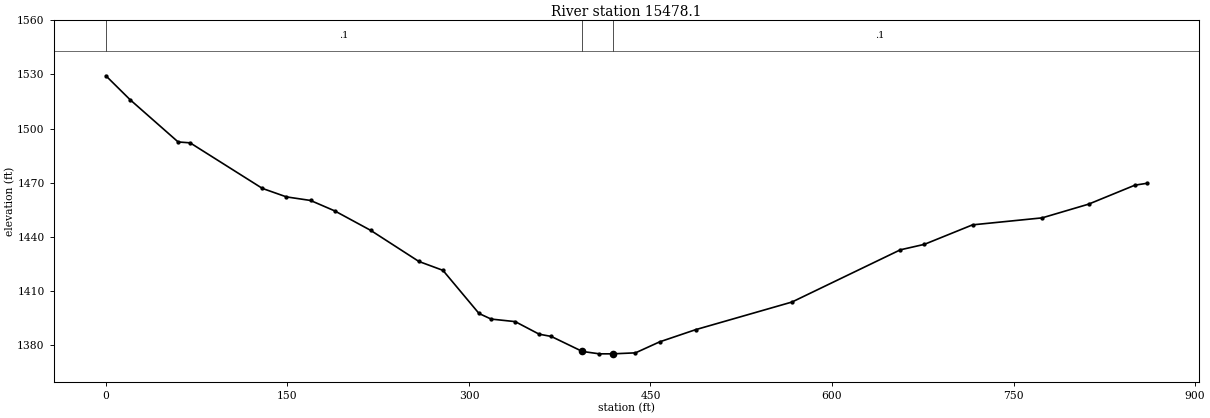
Type RM Length L Ch R = 1 ,15478.1 ,291.5,292.1,292.6
XS GIS Cut Line= 3
      1935364.49      301374.461     1935106.464      300706.469
     1935156.924      300571.817
#Sta/Elev= 30
       0 1529.23    19.9 1516.04    59.7 1492.57    69.6 1492.08   129.3 1466.84
   149.2 1462.14   169.1 1460.16     189 1454.41   218.8  1443.6   258.6 1426.38
   278.5 1421.45   308.3 1397.56   318.3 1394.46   338.2 1393.05     358 1386.09
     368 1384.84   393.7 1376.52   407.8  1375.2   418.7  1375.2   437.6 1375.75
   457.5 1381.82   487.3 1388.59   566.9  1403.9   656.4 1432.81   676.3 1435.85
   716.1 1446.65   773.6 1450.52     812 1458.12   850.3 1468.64   859.9 1469.64
#Mann= 3 , 0 , 0
       0      .1       0   393.7    .045       0   418.7      .1       0
Bank Sta=393.7,418.7
XS Rating Curve= 0 ,0
Exp/Cntr=0.3,0.1