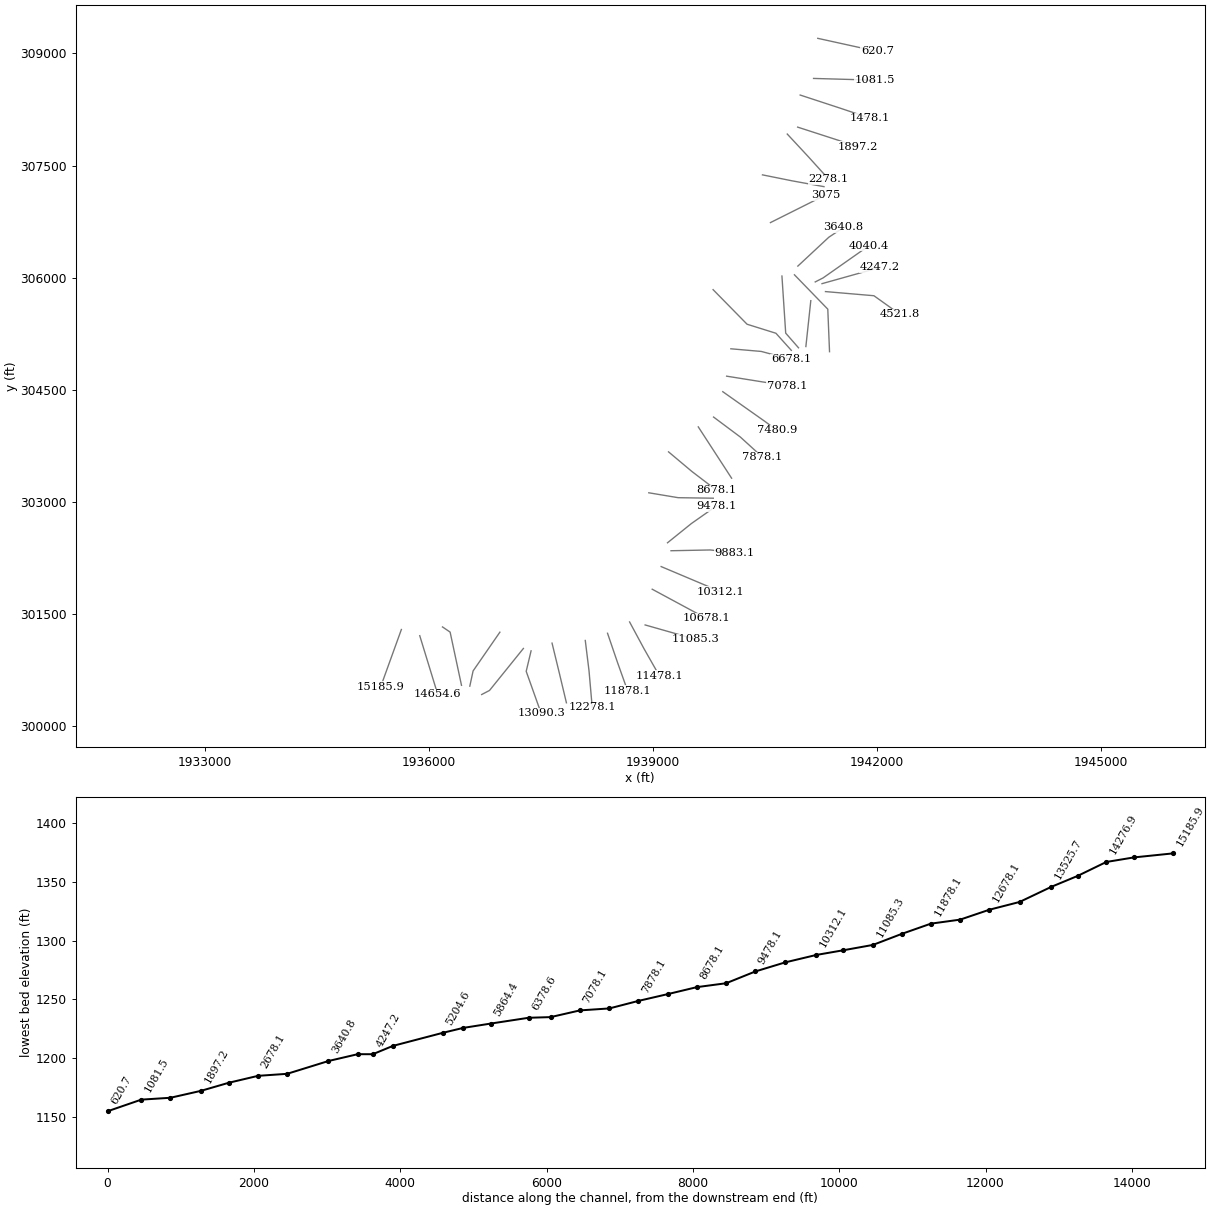
HEC-RAS study PnyCrk.prj: PnyCrk

--- PnyCrk.g01 (geometry) --- (continued)

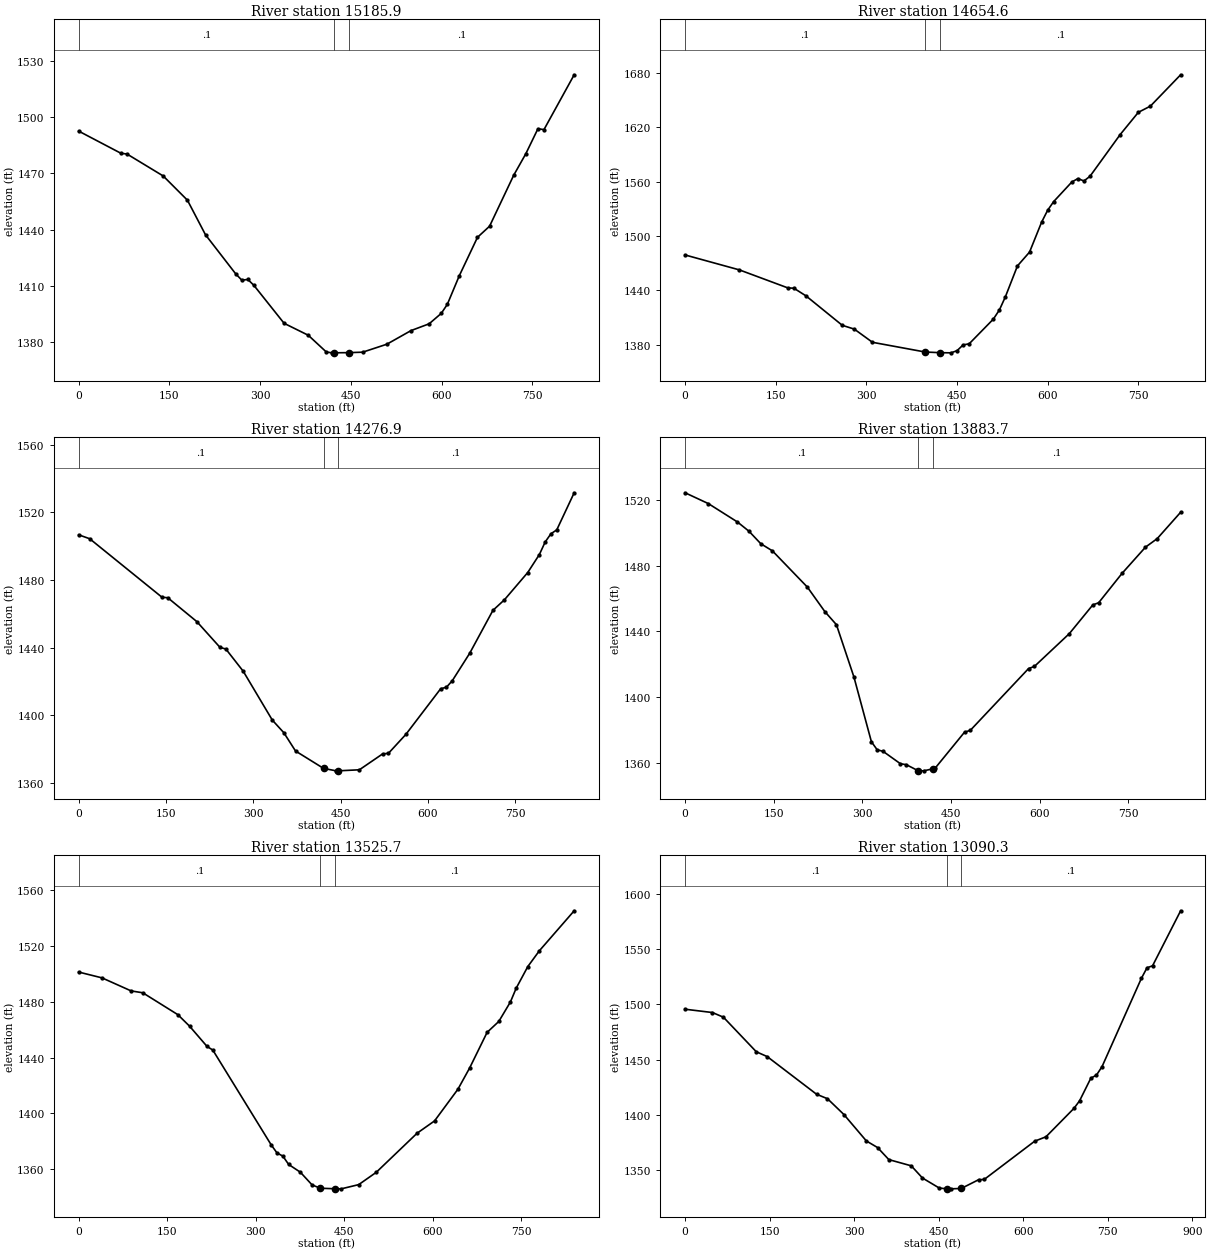
Type RM Length L Ch R = 1 ,15185.9 ,513.1,530.9,548.6
XS GIS Cut Line= 3
     1935635.538       301291.95     1935496.196      300906.886
     1935356.854      300521.822
#Sta/Elev= 30
       0 1492.45    69.9 1480.63    79.9 1480.24   139.8 1468.54   179.8 1455.65
   209.7 1437.22   259.7 1416.39   269.7 1413.08   279.7 1413.43   289.6 1410.33
   339.6 1390.09   379.5 1383.74   409.5 1374.78   419.5 1374.37   422.3 1374.39
   447.3 1374.48   469.4 1374.72   509.4 1378.96   549.3 1386.21   579.3 1389.83
   599.3 1395.37   609.3 1400.15   629.2 1415.47   659.2 1435.88   679.2  1441.8
   719.1 1468.95   739.1 1480.39   759.1 1493.69   769.1 1493.24     819 1522.43
#Mann= 3 , 0 , 0
       0      .1       0   422.3    .045       0   447.3      .1       0
Bank Sta=422.3,447.3
XS Rating Curve= 0 ,0
Exp/Cntr=0.3,0.1

Type RM Length L Ch R = 1 ,14654.6 ,379.8,377.4,374.9
XS GIS Cut Line= 2
     1935881.614      301208.943     1936122.092      300425.087
#Sta/Elev= 30
       0 1479.07      90 1462.55     170  1442.7     180 1442.34     200  1433.9
     260 1401.38     280 1397.16     310  1382.6   397.3 1371.86   422.3 1371.13
     440 1370.96     450 1373.38     460 1379.72     470 1380.93     510  1408.2
     520 1418.29   529.9 1432.82   549.9    1467   569.9 1482.24   589.9 1515.36
   599.9  1528.5   609.9  1538.1   639.9 1559.69   649.9 1563.46   659.9 1560.83
   669.9 1565.97   719.9 1612.11   749.9 1636.63   769.9 1643.51   819.9 1678.12
#Mann= 3 , 0 , 0
       0      .1       0   397.3    .045       0   422.3      .1       0
Bank Sta=397.3,422.3
XS Rating Curve= 0 ,0
Exp/Cntr=0.3,0.1

Type RM Length L Ch R = 1 ,14276.9 ,415.7,393.2,370.7
XS GIS Cut Line= 3
      1936186.25       301326.36     1936288.274      301257.291
     1936440.622      300545.284
#Sta/Elev= 30
       0 1506.78      19 1504.46   143.2 1469.82   153.1 1469.54     203 1455.43
   242.9 1440.14   252.9 1439.19   282.8 1426.01   332.7 1397.13   352.6 1389.61
   372.6 1378.82   420.7 1368.54   442.4 1367.08   445.7 1367.08   482.3  1367.7
   522.2  1377.1   532.2 1377.44   562.1 1388.62   621.9 1415.65   631.9 1416.58
   641.9 1420.41   671.8 1436.65   711.7 1462.05   731.6 1468.36   771.5 1484.45
   791.5  1495.1   801.5 1502.54   811.4 1507.41   821.4 1509.71   851.3 1531.66
#Mann= 3 , 0 , 0
       0      .1       0   420.7    .045       0   445.7      .1       0
Bank Sta=420.7,445.7
XS Rating Curve= 0 ,0
Exp/Cntr=0.3,0.1

Type RM Length L Ch R = 1 ,13883.7 ,360.4,358.4,356.4
XS GIS Cut Line= 3
     1936954.794      301256.207      1936596.01      300737.501
     1936552.072      300534.025
#Sta/Elev= 30
       0 1524.37    39.4 1517.78    88.7 1506.58   108.4 1500.89   128.1 1493.38
   147.8 1489.03     207 1466.97   236.5 1452.11   256.2 1444.09   285.8 1412.29
   315.4 1372.87   325.2 1367.97   335.1 1367.04   364.6 1359.47   374.5 1358.93
   394.8 1355.18     404 1355.17   419.8 1356.44   423.8 1357.02     473 1378.68
   482.9 1379.83   581.4 1417.39   591.3 1418.69   650.5 1438.67   690.2 1456.13
   700.1 1457.45   739.7 1475.32   779.4 1491.29   799.2 1496.46   838.9 1512.51
#Mann= 3 , 0 , 0
       0      .1       0   394.8    .045       0   419.8      .1       0
Bank Sta=394.8,419.8
XS Rating Curve= 0 ,0
Exp/Cntr=0.3,0.1

Type RM Length L Ch R = 1 ,13525.7 ,406.7,434.9,463
XS GIS Cut Line= 3
     1937269.567      301038.112     1936815.822      300476.313
     1936711.147      300421.897
#Sta/Elev= 30
       0 1501.37    39.6 1497.19      89 1487.84   108.8 1486.49   168.2  1470.8
     188 1462.59   217.6 1448.07   227.5 1445.41   326.4 1377.47   336.3 1371.64
   346.2 1369.39   356.1 1363.39   375.9 1357.83   395.7 1348.76   409.6 1346.34
   434.6 1345.97   445.2 1345.91   474.8 1348.93   504.5 1357.73   573.8  1385.8
   603.4 1394.62     643 1417.33   662.8  1432.5   692.5 1458.12   712.3 1465.93
     732  1479.9   741.8 1489.79   761.5  1505.3   781.1 1516.63   840.1  1545.3
#Mann= 3 , 0 , 0
       0      .1       0   409.6    .045       0   434.6      .1       0
Bank Sta=409.6,434.6
XS Rating Curve= 0 ,0
Exp/Cntr=0.3,0.1

Type RM Length L Ch R = 1 ,13090.3 ,415.1,412.2,409.2
XS GIS Cut Line= 3
     1937372.645      301006.345     1937307.165      300732.329
      1937507.74      300169.617
#Sta/Elev= 30
       0 1495.71    48.6  1492.7      68 1488.47   126.3 1457.18   145.7 1452.79
   233.2  1418.7   252.6 1414.64   281.7 1400.34   321.6 1376.38   341.5 1370.39
   361.4  1359.5   401.2 1353.86   421.1 1342.82     451  1333.7   464.9 1333.03
   470.9 1333.01   489.9 1333.34   520.7 1341.28   530.6  1341.5   620.2 1376.18
   640.2 1380.16     690 1405.99   699.9 1412.83   719.8 1433.25   729.8 1436.04
   739.7 1443.75   809.4 1523.61   819.4 1533.23   829.3 1535.05   879.1 1584.88
#Mann= 3 , 0 , 0
       0      .1       0   464.9    .045       0   489.9      .1       0
Bank Sta=464.9,489.9
XS Rating Curve= 0 ,0
Exp/Cntr=0.3,0.1

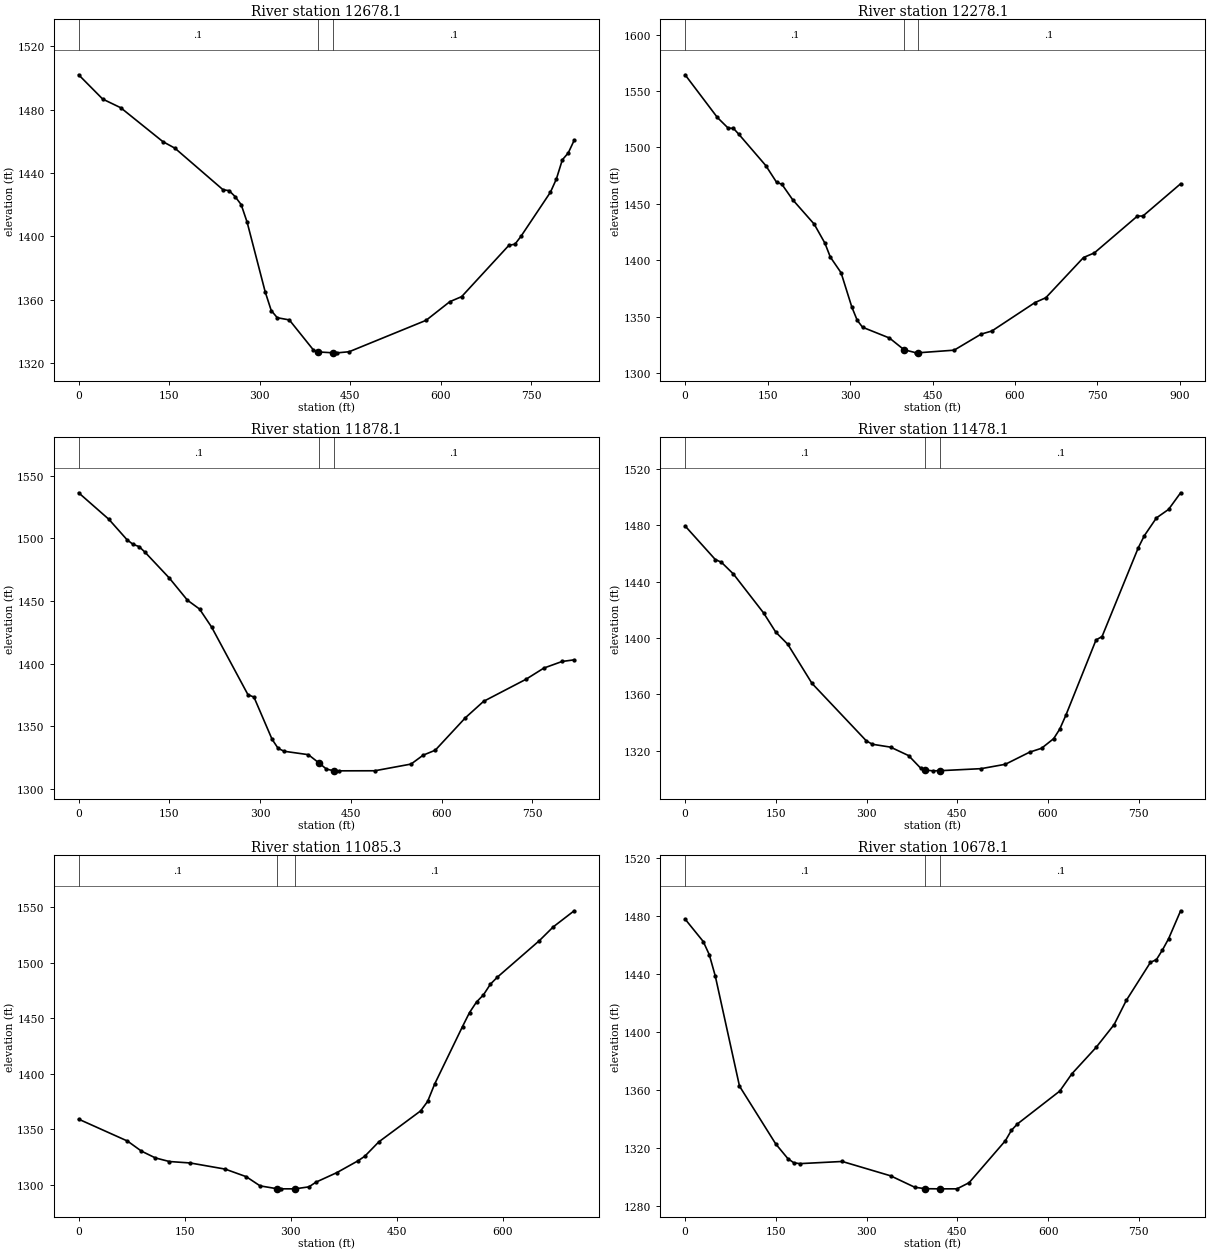
Type RM Length L Ch R = 1 ,12678.1 ,403.2,400,395.9
XS GIS Cut Line= 3
      1937653.39       301109.68     1937750.056      300712.261
     1937845.849      300311.251
#Sta/Elev= 30
       0 1501.98    39.9 1486.64    69.8 1481.16   139.7 1459.75   159.6 1455.63
   239.4 1429.37   249.4 1428.83   259.4 1425.05   269.4    1420   279.3 1408.85
   309.2 1364.93   319.2 1353.14   329.2  1348.6   349.2  1347.2   389.1 1328.24
   396.5 1327.02   421.5 1326.43   428.6 1326.42   448.3 1327.11   575.9 1346.96
   615.2 1358.72   634.8  1361.9   713.3 1394.38   723.1 1394.98     733 1399.92
     782 1427.86   791.8 1436.18   801.7  1448.3   811.5 1452.64   821.3  1460.6
#Mann= 3 , 0 , 0
       0      .1       0   396.5    .045       0   421.5      .1       0
Bank Sta=396.5,421.5
XS Rating Curve= 0 ,0
Exp/Cntr=0.3,0.1

Type RM Length L Ch R = 1 ,12278.1 ,393.6,399.3,406.3
XS GIS Cut Line= 3
     1938098.542      301145.089      1938148.83      300737.364
     1938191.584      300248.744
#Sta/Elev= 30
       0 1564.37    58.7 1526.55    78.2 1517.16      88 1516.85    97.8 1511.63
   146.7 1483.95   166.3 1469.18   176.1  1467.3   195.6  1453.7   234.8 1432.04
   254.3 1415.17   264.1 1402.88   283.7 1388.95   303.2 1358.63     313 1346.88
   322.8 1340.65   371.7 1331.11   398.3  1320.7   420.6 1317.98   423.3    1318
   489.3 1320.34   538.3 1334.54     558 1337.33   636.4 1362.53   656.1 1366.82
   724.7 1402.46   744.4 1406.54   822.8 1439.22   832.6 1439.17   901.3 1467.81
#Mann= 3 , 0 , 0
       0      .1       0   398.3    .045       0   423.3      .1       0
Bank Sta=398.3,423.3
XS Rating Curve= 0 ,0
Exp/Cntr=0.3,0.1

Type RM Length L Ch R = 1 ,11878.1 ,395.2,399.8,404.6
XS GIS Cut Line= 3
     1938396.621      301241.533     1938529.126      300853.734
     1938666.807      300468.132
#Sta/Elev= 30
       0 1536.42      50 1515.26      80 1498.96      90 1495.26     100 1493.49
     110 1488.88   149.9 1468.41   179.9 1450.71   199.9 1443.67   219.9 1429.24
   279.9 1375.37   289.9 1373.37   319.8 1339.77   329.8 1332.53   339.8 1330.19
   379.8 1327.47   397.3 1320.89   409.8 1315.94   422.3 1314.58   429.8 1314.57
   489.7 1314.63   549.6 1319.97   569.6 1327.07   589.6 1331.02   639.5 1356.95
   669.5    1370   739.4 1387.56   769.3 1396.59   799.3 1401.82   819.3 1403.13
#Mann= 3 , 0 , 0
       0      .1       0   397.3    .045       0   422.3      .1       0
Bank Sta=397.3,422.3
XS Rating Curve= 0 ,0
Exp/Cntr=0.3,0.1

Type RM Length L Ch R = 1 ,11478.1 ,370.2,392.4,413.9
XS GIS Cut Line= 3
     1938692.063       301392.81      1938886.43      301032.426
     1939089.046      300676.287
#Sta/Elev= 30
       0 1479.55    49.9 1455.74    59.9 1453.84    79.9 1445.44   129.8 1417.82
   149.8 1404.27   169.8 1395.58   209.7  1367.9   299.6 1327.08   309.6 1324.67
   339.6 1322.63   369.5 1316.62   389.5 1307.67     397 1306.38   409.5 1305.81
     422 1305.92   489.4 1307.36   529.4 1310.46   569.4 1319.03   589.3 1321.83
   609.3 1328.65   619.3 1335.38   629.3 1345.09   679.3 1398.65   689.3 1401.11
   749.2  1464.1   759.2 1472.65   779.2 1485.27   799.2 1491.28   819.2 1503.09
#Mann= 3 , 0 , 0
       0      .1       0     397    .045       0     422      .1       0
Bank Sta=397,422
XS Rating Curve= 0 ,0
Exp/Cntr=0.3,0.1

Type RM Length L Ch R = 1 ,11085.3 ,413,407,401
XS GIS Cut Line= 2
     1938900.153      301352.974     1939574.183      301161.355
#Sta/Elev= 30
       0 1359.21    69.1 1339.48    88.8 1330.42   108.6 1324.28   128.3 1321.06
   157.9 1319.74   207.3 1314.21   236.9 1307.42   256.6 1299.12   281.1 1296.48
   286.2 1296.45   306.1 1296.45   325.7 1298.25   335.6 1302.46   365.2 1311.08
   394.8 1321.61   404.6 1325.78   424.4 1338.72   483.6 1366.66   493.5 1375.19
   503.4 1390.81   542.8 1442.62   552.7  1455.2   562.6 1464.72   572.4 1471.13
   582.3 1480.83   592.2 1487.16   651.4 1519.95   671.1 1532.37   700.7 1546.89
#Mann= 3 , 0 , 0
       0      .1       0   281.1    .045       0   306.1      .1       0
Bank Sta=281.1,306.1
XS Rating Curve= 0 ,0
Exp/Cntr=0.3,0.1

Type RM Length L Ch R = 1 ,10678.1 ,363.3,365.9,368.6
XS GIS Cut Line= 3
     1938995.055      301830.953     1939355.579      301636.756
     1939716.103      301442.559
#Sta/Elev= 30
       0 1477.85      30 1462.39      40  1453.3    49.9 1438.58    89.9  1362.7
   149.8 1322.84   169.8 1312.74   179.8  1309.8   189.8 1309.26   259.7 1310.75
   339.6 1300.86   379.5 1292.99     397 1291.97   419.5 1291.88     422 1291.88
   449.4 1291.88   469.4 1296.12   529.4 1325.09   539.3 1332.23   549.3 1336.64
   619.2 1359.27   639.2 1371.17   679.2 1389.35   709.1 1405.14   729.1 1421.74
   769.1 1448.03     779 1449.93     789 1456.62     799 1464.23     819 1483.59
#Mann= 3 , 0 , 0
       0      .1       0     397    .045       0     422      .1       0
Bank Sta=397,422
XS Rating Curve= 0 ,0
Exp/Cntr=0.3,0.1

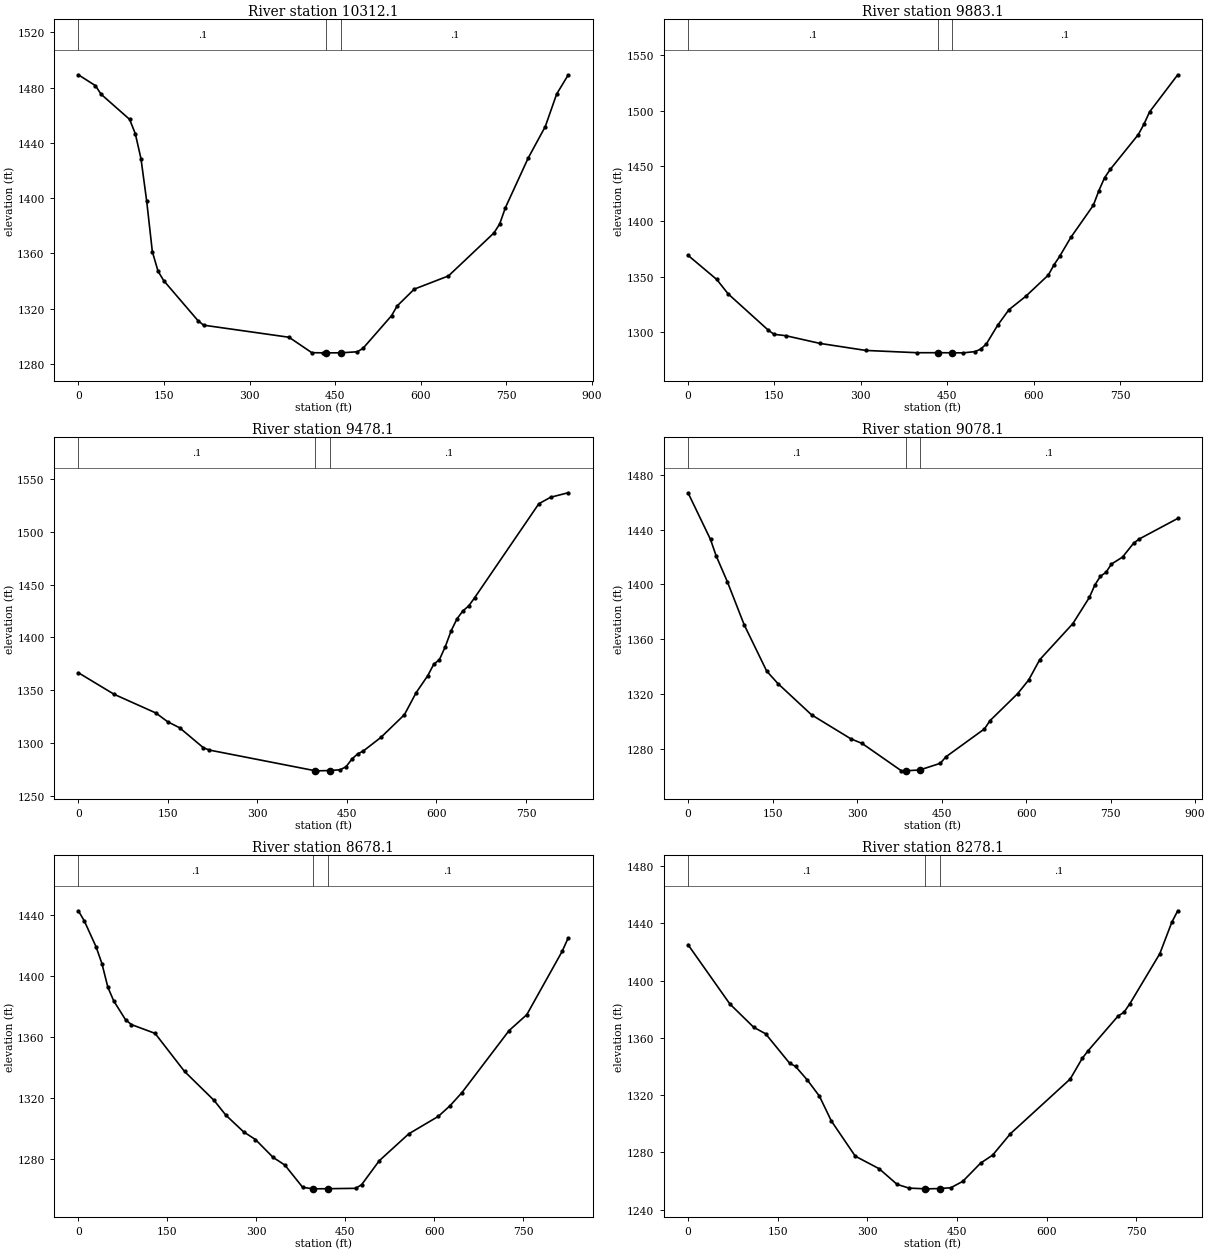
Type RM Length L Ch R = 1 ,10312.1 ,417,428.9,440.8
XS GIS Cut Line= 2
     1939114.792      302133.951     1939905.628      301800.441
#Sta/Elev= 30
       0 1489.28    29.9 1481.43    39.9 1475.18    89.8 1457.01    99.8 1446.66
   109.8 1428.52   119.8 1397.77   129.7 1361.19   139.7 1347.03   149.7 1340.18
   209.6 1311.29   219.6 1307.96   369.3 1299.21   409.2 1288.04   429.1 1287.93
   434.9 1287.94   459.9 1287.94     489  1288.7     499 1291.23   548.9 1314.81
   558.9 1321.95   588.8 1334.07   648.7 1343.63   728.5 1374.78   738.5 1381.32
   748.5 1393.06   788.4 1428.98   818.4 1451.81   838.3 1475.32   858.3 1488.98
#Mann= 3 , 0 , 0
       0      .1       0   434.9    .045       0   459.9      .1       0
Bank Sta=434.9,459.9
XS Rating Curve= 0 ,0
Exp/Cntr=0.3,0.1

Type RM Length L Ch R = 1 ,9883.1  ,387,404.8,420.9
XS GIS Cut Line= 3
     1939246.664      302345.966     1939774.227      302356.349
      1940094.42      302319.301
#Sta/Elev= 30
       0 1369.49    49.8 1347.74    69.7 1334.69   139.4 1301.94   149.3 1298.24
   169.2 1297.05     229 1290.05   308.6 1283.71   398.2 1281.64   433.7 1281.67
   458.7 1281.58   477.9 1281.54   497.8 1282.63   507.8 1284.81   517.7 1289.47
   537.4 1306.41     557 1320.44   586.3 1332.57   625.3 1351.66   635.1 1360.76
   644.9 1368.44   664.4 1385.62   703.5 1414.63   713.2 1427.91     723 1439.45
   732.8 1446.95   781.6 1478.42   791.4  1487.8   801.2 1498.91     850 1532.32
#Mann= 3 , 0 , 0
       0      .1       0   433.7    .045       0   458.7      .1       0
Bank Sta=433.7,458.7
XS Rating Curve= 0 ,0
Exp/Cntr=0.3,0.1

Type RM Length L Ch R = 1 ,9478.1  ,422.9,399.8,382.4
XS GIS Cut Line= 3
      1939200.01      302452.571     1939518.732      302709.208
     1939855.355       302945.35
#Sta/Elev= 30
       0 1366.63    59.9 1346.24   129.8 1328.58   149.7 1320.26   169.7 1314.57
   209.6 1295.65   219.6  1293.5   396.7 1273.96   399.2 1273.87   421.7 1274.16
   438.6 1274.91   448.4 1277.69   458.2 1284.93   467.9 1289.88   477.7 1292.74
   507.1  1305.6   546.3 1326.98   565.8 1347.68   585.4 1363.87   595.2 1374.43
     605 1379.12   614.8 1391.39   624.6 1406.35   634.4 1417.64   644.2 1425.03
     654  1429.8   663.8 1437.43   771.4 1526.34     791 1532.47   820.4 1536.74
#Mann= 3 , 0 , 0
       0      .1       0   396.7    .045       0   421.7      .1       0
Bank Sta=396.7,421.7
XS Rating Curve= 0 ,0
Exp/Cntr=0.3,0.1

Type RM Length L Ch R = 1 ,9078.1  ,414.3,399.5,382
XS GIS Cut Line= 3
     1938949.295      303121.436     1939342.605       303055.86
     1939813.032      303049.017
#Sta/Elev= 30
       0 1466.94    39.9 1432.84    49.8 1421.01    69.8 1401.98    99.7 1370.51
   139.6 1336.71   159.5 1327.61   219.3 1304.73   289.1  1287.2     309 1283.84
   378.8 1263.83   386.2 1263.87   411.2 1264.44   447.8 1269.34   457.6 1274.03
   526.2 1294.48     536 1300.48     585  1320.2   604.6 1330.16   624.2 1344.99
     683 1371.36   712.4 1390.52   722.2 1399.65     732 1405.99   741.8 1408.79
   751.6 1414.89   771.2 1419.96   790.8 1430.08   800.6 1433.12   869.2  1448.2
#Mann= 3 , 0 , 0
       0      .1       0   386.2    .045       0   411.2      .1       0
Bank Sta=386.2,411.2
XS Rating Curve= 0 ,0
Exp/Cntr=0.3,0.1

Type RM Length L Ch R = 1 ,8678.1  ,408.2,400,390.5
XS GIS Cut Line= 3
     1939213.627      303669.072     1939526.182      303406.771
     1939858.511      303153.559
#Sta/Elev= 30
       0 1442.82      10 1436.23    29.9 1419.19    39.8 1408.17    49.8 1392.66
    59.7 1383.71    79.6 1371.38    89.6  1368.2   129.4 1362.44   179.1 1337.48
   228.9  1318.5   248.8  1308.8   278.7 1297.88   298.6 1292.86   328.4 1281.15
   348.3 1276.09   378.2 1261.56   395.5 1260.52   420.5 1260.62   467.7 1260.85
   477.7 1263.26   507.5 1278.98   557.2 1296.58     607 1308.03   626.9 1315.05
   646.8  1323.6   726.4 1364.31   756.2  1374.7   815.9 1416.26   825.8 1424.83
#Mann= 3 , 0 , 0
       0      .1       0   395.5    .045       0   420.5      .1       0
Bank Sta=395.5,420.5
XS Rating Curve= 0 ,0
Exp/Cntr=0.3,0.1

Type RM Length L Ch R = 1 ,8278.1  ,390.2,400,407.1
XS GIS Cut Line= 3
     1939611.937      304003.271     1939835.108      303659.926
     1940058.278      303316.582
#Sta/Elev= 30
       0 1425.09    69.9 1383.72   109.9 1367.38   129.8 1362.84   169.8 1342.34
   179.8 1340.07   199.8 1330.42   219.7 1319.32   239.7 1301.96   279.7 1277.37
   319.6 1268.61   349.6 1257.68   369.6 1255.06     397 1254.56   399.5 1254.55
     422 1254.76   439.5 1255.33   459.4 1259.75   489.4 1272.54   509.4 1278.08
   539.3  1293.1   639.2 1331.28   659.2 1345.63   669.2 1351.06   719.1  1375.2
   729.1 1377.88   739.1 1383.97     789 1418.79     809 1440.67     819 1448.77
#Mann= 3 , 0 , 0
       0      .1       0     397    .045       0     422      .1       0
Bank Sta=397,422
XS Rating Curve= 0 ,0
Exp/Cntr=0.3,0.1

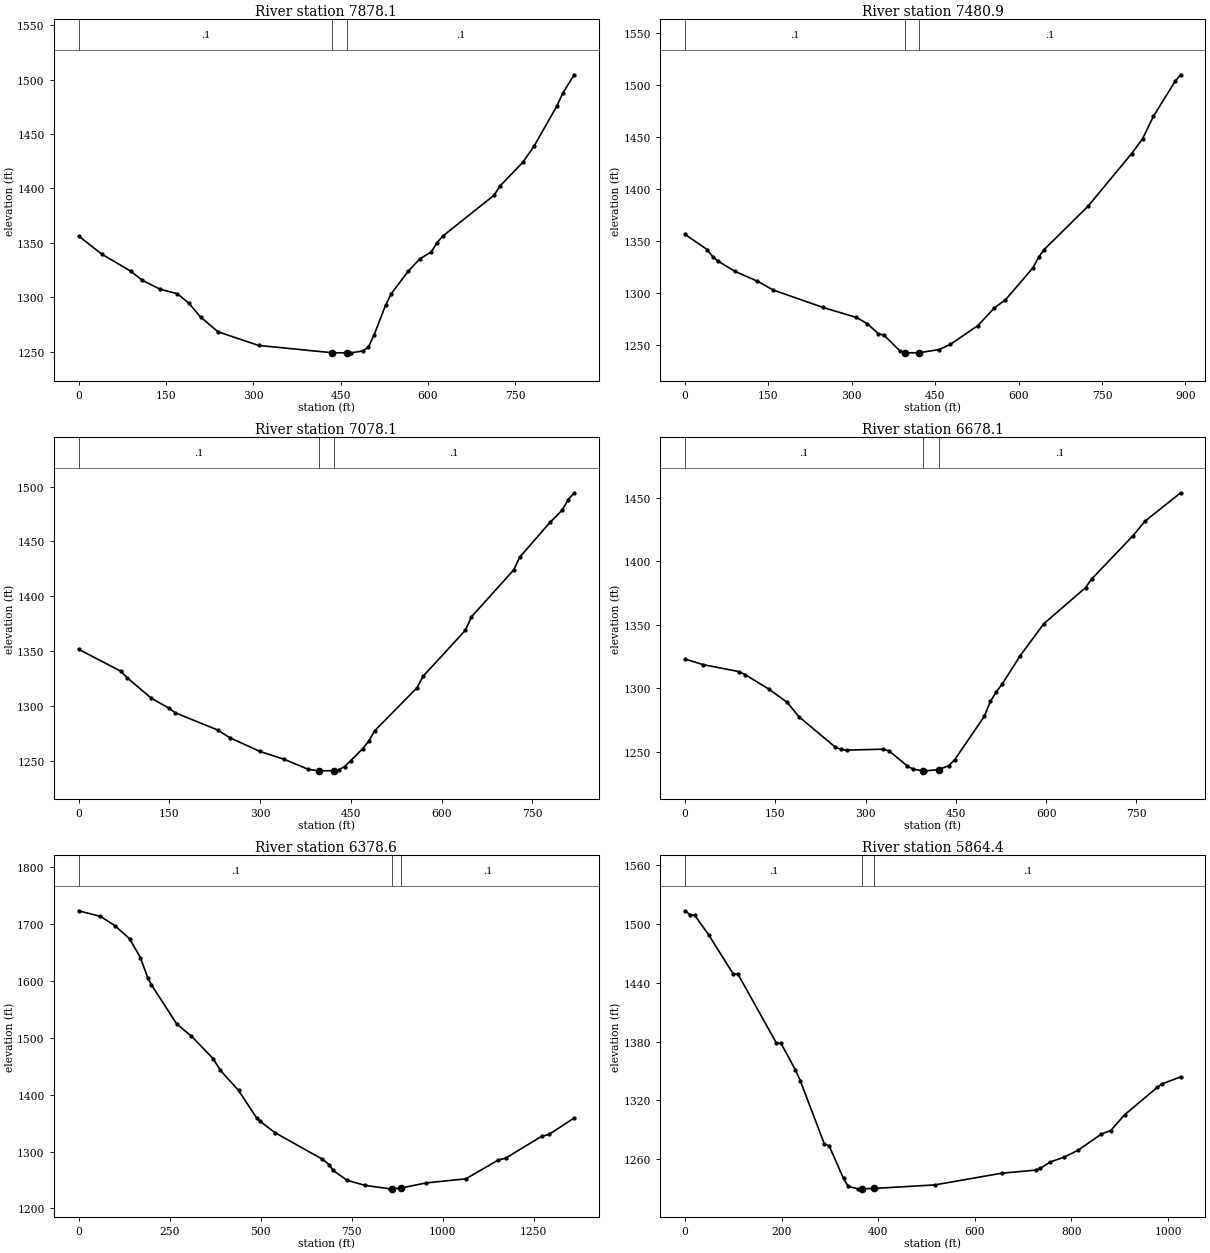
Type RM Length L Ch R = 1 ,7878.1  ,396.1,396.9,400.3
XS GIS Cut Line= 3
     1939816.667      304134.901     1940176.068      303866.738
     1940473.988      303595.895
#Sta/Elev= 30
       0 1356.27    39.9 1339.55    89.7 1323.82   109.6 1315.44   139.5 1307.43
   169.4 1303.16   189.3 1294.46   209.3 1281.81   239.2 1268.17   308.9 1255.62
   435.9 1248.83   460.9 1248.79   468.1 1248.78   487.7 1250.46   497.5 1253.87
   507.3 1265.12     527 1292.38   536.8 1303.16   566.3 1324.09   585.9  1335.2
   605.5 1341.59   615.4    1350   625.2 1356.14   713.6 1393.85   723.4 1402.14
   762.7 1423.99   782.3 1439.12   821.6 1476.14   831.4 1487.69     851 1504.61
#Mann= 3 , 0 , 0
       0      .1       0   435.9    .045       0   460.9      .1       0
Bank Sta=435.9,460.9
XS Rating Curve= 0 ,0
Exp/Cntr=0.3,0.1

Type RM Length L Ch R = 1 ,7480.9  ,390.2,402.7,415.3
XS GIS Cut Line= 3
     1939940.159      304474.118     1940508.656      304073.465
     1940666.404      303957.094
#Sta/Elev= 30
       0 1356.28    39.7 1341.64    49.7 1334.84    59.6  1330.5    89.4 1320.77
   129.2 1311.52     159 1302.71   248.4 1285.98     308 1276.45   327.9 1270.38
   347.8 1260.67   357.7  1259.5   387.5 1243.69   395.5 1242.63   397.4 1242.38
   420.5 1242.47     457 1245.49   476.9 1250.41   526.6 1268.54   556.4 1285.62
   576.3 1293.33   625.9 1324.21   635.9  1334.3   645.8 1341.61   724.9 1383.38
   803.3 1433.96   822.9  1448.1   842.5 1469.74   881.7 1503.66   891.5 1509.77
#Mann= 3 , 0 , 0
       0      .1       0   395.5    .045       0   420.5      .1       0
Bank Sta=395.5,420.5
XS Rating Curve= 0 ,0
Exp/Cntr=0.3,0.1

Type RM Length L Ch R = 1 ,7078.1  ,398,400,397.1
XS GIS Cut Line= 3
     1939991.794      304681.993     1940396.168      304617.403
     1940800.542      304552.812
#Sta/Elev= 30
       0 1351.61    69.9 1331.52    79.9  1325.8   119.8  1307.1   149.8 1297.72
   159.8 1293.62   229.7 1277.99   249.7 1270.99   299.6 1258.39   339.6 1251.24
   379.5 1242.11     397 1240.75   399.5  1240.7     422 1240.93   429.5 1241.52
   439.5 1244.57   449.4  1249.8   469.4  1260.9   479.4 1267.74   489.4 1277.32
   559.3  1316.5   569.3 1326.99   639.2 1368.92   649.2  1381.2   719.1 1424.01
   729.1 1435.69     779 1467.34     799 1478.44     809 1488.05     819 1494.37
#Mann= 3 , 0 , 0
       0      .1       0     397    .045       0     422      .1       0
Bank Sta=397,422
XS Rating Curve= 0 ,0
Exp/Cntr=0.3,0.1

Type RM Length L Ch R = 1 ,6678.1  ,305.5,299.5,298.4
XS GIS Cut Line= 3
     1940048.199      305048.321     1940455.214      305012.925
     1940856.088      304906.045
#Sta/Elev= 30
       0 1323.06    29.9 1318.68    89.7 1313.16    99.6 1310.86   139.5 1299.26
   169.4 1289.04   189.3  1277.6   249.1 1253.84   259.1 1251.82     269 1251.35
   328.8 1252.04   338.8 1250.74   368.7 1239.05   378.7 1236.26   396.1 1235.02
   398.6 1234.99   421.1 1235.93   438.2 1239.06   448.1 1243.84   497.4 1278.07
   507.3 1289.69   517.2 1297.32   527.1 1303.51   556.7 1325.64   596.2 1350.98
   665.4 1379.32   675.3    1386   744.4 1420.33   764.2 1431.69   823.4 1454.07
#Mann= 3 , 0 , 0
       0      .1       0   396.1    .045       0   421.1      .1       0
Bank Sta=396.1,421.1
XS Rating Curve= 0 ,0
Exp/Cntr=0.3,0.1

Type RM Length L Ch R = 1 ,6378.6  ,547.3,514.1,481
XS GIS Cut Line= 4
     1939810.431      305839.716     1940265.571      305376.819
     1940651.957      305256.286     1940857.769      305027.706
#Sta/Elev= 30
       0 1723.69    59.9 1713.72    99.9  1697.5   139.8 1674.52   169.8 1641.28
   189.8 1605.92   199.8 1593.63   269.7 1524.34   309.6 1503.29   369.5 1463.54
   389.5 1442.94   439.4 1407.48   489.4 1358.96   499.4 1352.93   539.3 1333.34
   668.9 1286.89   688.7 1276.81   698.5 1267.12     738 1249.38   787.4 1240.45
   856.5 1234.43   861.2 1234.54   886.2 1235.91   955.2 1244.89  1063.8 1252.03
  1153.1 1285.15    1173 1288.37  1272.2 1326.87    1292  1330.1  1361.5 1359.07
#Mann= 3 , 0 , 0
       0      .1       0   861.2    .045       0   886.2      .1       0
Bank Sta=861.2,886.2
XS Rating Curve= 0 ,0
Exp/Cntr=0.3,0.1

Type RM Length L Ch R = 1 ,5864.4  ,385.3,380.8,376.3
XS GIS Cut Line= 3
     1940732.382      306021.587     1940782.774      305257.862
       1940954.4      305061.614
#Sta/Elev= 30
       0 1513.57     9.9 1509.69    19.9 1509.03    49.7 1488.33    99.4 1449.16
   109.3 1448.99   188.9 1378.55   198.8 1378.03   228.6 1350.78   238.6 1339.94
   288.3 1275.37   298.2  1273.5     328 1240.11     338 1232.04   357.8 1229.54
   366.2 1229.62   391.2 1229.96   516.9 1233.55     656 1245.54   725.6 1248.64
   735.6 1250.42   755.4 1256.86   784.7 1261.87   813.7 1268.94   861.9  1285.5
   881.3 1289.12   910.2 1305.22   977.8 1333.27   987.5 1336.76  1026.1 1343.86
#Mann= 3 , 0 , 0
       0      .1       0   366.2    .045       0   391.2      .1       0
Bank Sta=366.2,391.2
XS Rating Curve= 0 ,0
Exp/Cntr=0.3,0.1

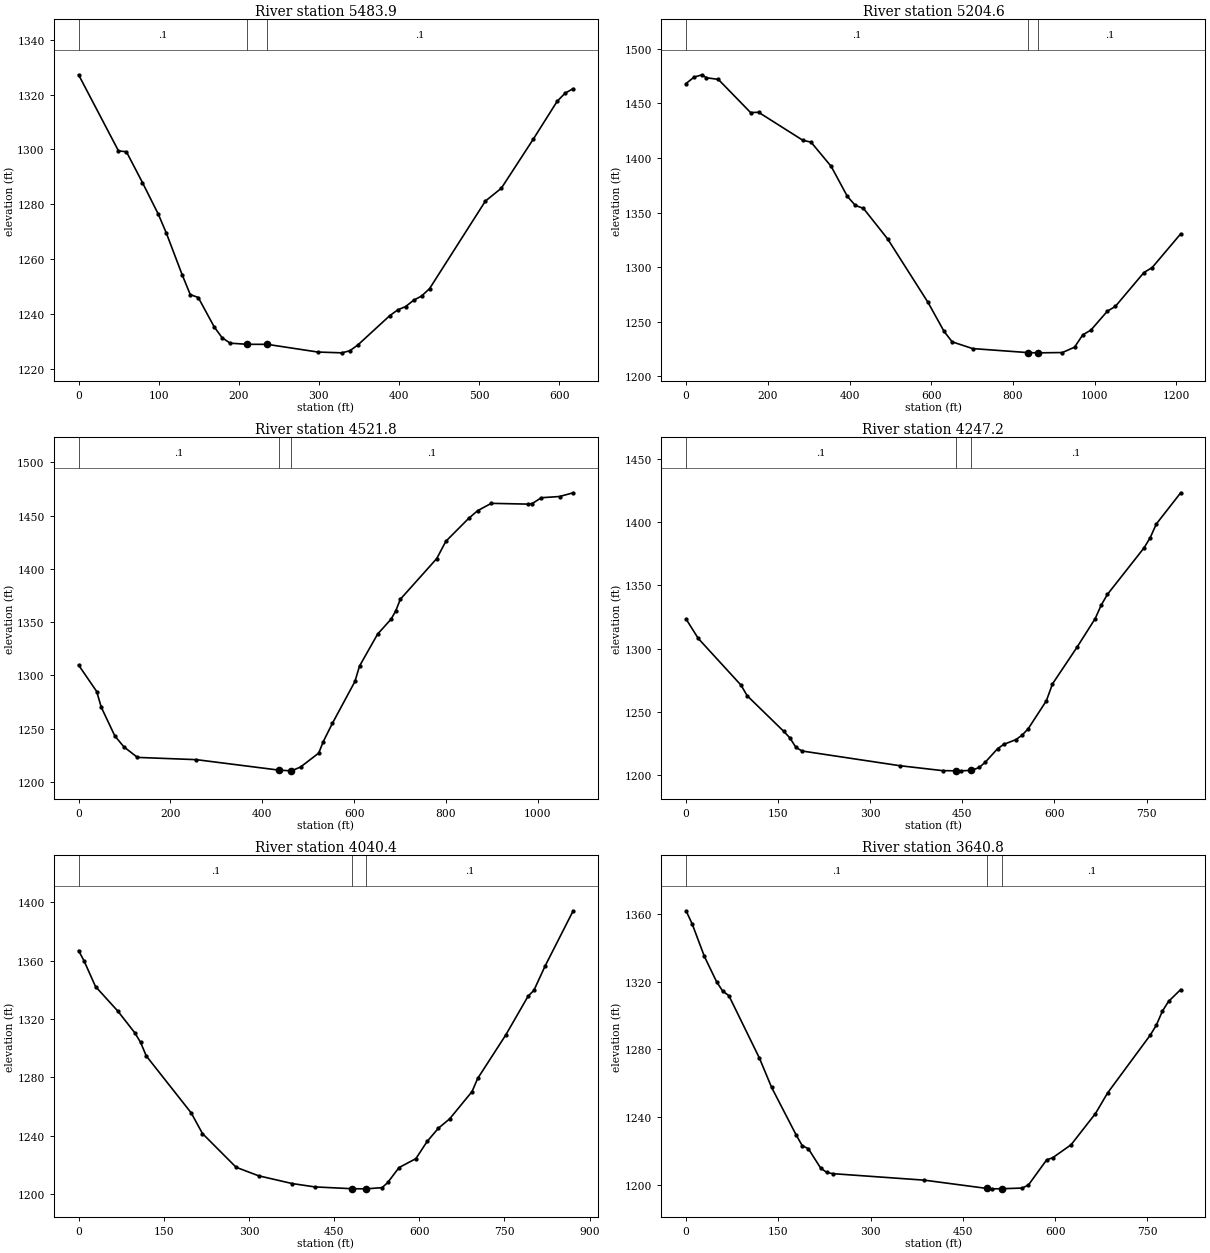
Type RM Length L Ch R = 1 ,5483.9  ,275.1,278.9,282.8
XS GIS Cut Line= 2
     1941118.957      305692.313     1941053.005      305078.497
#Sta/Elev= 30
       0 1327.24    49.8 1299.47    59.7 1299.17    79.7 1287.94    99.6 1276.34
   109.5 1269.52   129.4 1254.21   139.4 1247.07   149.4 1245.99   169.3 1235.27
   179.2 1231.32   189.2 1229.34   210.5 1228.92   235.5 1228.91   298.7  1226.1
   328.6 1225.81   338.6 1226.57   348.5 1228.65   388.3 1239.34   398.3 1241.46
   408.2 1242.69   418.2 1244.98   428.2 1246.55   438.1 1249.22   507.8 1281.17
   527.7 1285.85   567.6 1303.77   597.4 1317.57   607.4 1320.56   617.4 1322.18
#Mann= 3 , 0 , 0
       0      .1       0   210.5    .045       0   235.5      .1       0
Bank Sta=210.5,235.5
XS Rating Curve= 0 ,0
Exp/Cntr=0.3,0.1

Type RM Length L Ch R = 1 ,5204.6  ,642.9,682.7,722.6
XS GIS Cut Line= 3
     1940899.778      306038.542     1941346.526      305578.528
     1941369.801      305009.604
#Sta/Elev= 30
       0 1468.17    19.7 1474.05    39.5 1476.16    49.3 1473.47    78.9 1471.92
   157.8 1441.61   177.6  1441.8   286.1 1416.12   305.8 1414.52   355.2 1392.27
   394.6 1364.92   414.3 1356.56   434.1 1353.87   493.3 1325.92   591.9 1267.94
   631.4 1241.29   651.2  1231.7   701.2 1225.53   836.8 1221.84     861 1221.62
   861.8 1221.63     921 1221.88   950.9 1226.82   970.9 1238.09   990.9 1242.45
  1030.8 1259.64  1050.8 1264.18  1120.7 1295.16  1140.7 1299.64  1210.6 1330.56
#Mann= 3 , 0 , 0
       0      .1       0   836.8    .045       0   861.8      .1       0
Bank Sta=836.8,861.8
XS Rating Curve= 0 ,0
Exp/Cntr=0.3,0.1

Type RM Length L Ch R = 1 ,4521.8  ,264.7,274.6,284.5
XS GIS Cut Line= 3
     1941315.494      305813.856     1941964.263      305758.369
     1942311.111      305511.292
#Sta/Elev= 30
       0 1309.72    39.5 1284.88    49.3 1270.21    78.9 1243.25    98.7 1232.97
   128.2 1223.09   256.5 1220.97   436.5 1211.14   461.5  1210.5   463.7 1210.48
   483.4 1214.09   522.9 1227.14   532.8 1237.91   552.5 1254.92   601.8 1294.36
   611.7 1308.75   651.1 1338.74   680.8 1352.97   690.8  1360.7   700.6 1371.44
   779.9 1409.64   799.7 1425.82   849.2 1447.23     869 1454.57   898.7 1461.43
     978 1460.71   987.9 1461.27  1007.7  1466.7  1047.3 1467.84    1077 1471.34
#Mann= 3 , 0 , 0
       0      .1       0   436.5    .045       0   461.5      .1       0
Bank Sta=436.5,461.5
XS Rating Curve= 0 ,0
Exp/Cntr=0.3,0.1

Type RM Length L Ch R = 1 ,4247.2  ,197.3,206.6,216
XS GIS Cut Line= 2
     1941268.946      305919.882     1942044.751      306137.108
#Sta/Elev= 30
       0 1323.29    19.9 1307.94    89.5 1271.07    99.5 1262.73   159.1 1234.57
   169.1 1229.41     179 1221.84     189 1219.06   348.1 1207.46   417.7 1203.57
   439.7 1203.41   447.6  1203.4   464.7 1203.77   477.4 1206.04   487.4 1210.27
   507.3 1220.84   517.2 1224.23   537.1 1228.05     547 1231.45     557 1236.49
   586.8  1258.7   596.8 1272.09   636.6 1300.94   666.4 1323.72   676.3 1334.45
   686.3  1342.8     746 1379.59   755.9 1387.55   765.9 1398.39   805.6 1423.05
#Mann= 3 , 0 , 0
       0      .1       0   439.7    .045       0   464.7      .1       0
Bank Sta=439.7,464.7
XS Rating Curve= 0 ,0
Exp/Cntr=0.3,0.1

Type RM Length L Ch R = 1 ,4040.4  ,395.6,399.4,403.2
XS GIS Cut Line= 3
     1941178.435      305943.157     1941284.462      305997.463
     1941899.934      306429.328
#Sta/Elev= 30
       0 1366.91     9.9 1359.62    29.8 1342.23    69.5  1325.2    99.3 1310.32
   109.2 1303.89   119.1 1294.67   198.3 1255.54   218.1 1241.38   277.4 1218.22
     317 1212.37   376.4 1207.03   415.9 1204.75   481.8  1203.5     505 1203.42
   506.8 1203.43   534.6 1204.24   544.5  1207.8   564.3    1218     594 1224.14
   613.8 1235.94   633.6 1245.01   653.4 1251.42   692.9 1270.17   702.8 1279.15
   752.3 1309.02   791.8 1335.74   801.8 1339.59   821.5 1356.29     871 1394.21
#Mann= 3 , 0 , 0
       0      .1       0   481.8    .045       0   506.8      .1       0
Bank Sta=481.8,506.8
XS Rating Curve= 0 ,0
Exp/Cntr=0.3,0.1

Type RM Length L Ch R = 1 ,3640.8  ,573.4,565.4,557.5
XS GIS Cut Line= 3
     1940945.694       306155.21     1941360.311      306541.256
      1941558.58      306672.414
#Sta/Elev= 30
       0 1361.87     9.9  1354.1    29.8 1334.88    49.7 1319.88    59.6 1314.39
    69.6 1311.72   119.3 1274.79   139.1  1257.5   178.9 1229.49   188.8 1223.14
   198.8 1221.31   218.6    1210   228.6 1207.29   238.5 1206.58   387.6 1202.73
   488.8 1197.86   496.9 1197.61   513.8 1197.67   546.6 1198.08   556.6 1199.87
   586.3 1214.73   596.2    1216     626 1223.66   665.6 1242.06   685.4 1254.28
   754.7 1288.41   764.6 1294.29   774.5  1302.6   784.4 1308.31   804.2 1315.34
#Mann= 3 , 0 , 0
       0      .1       0   488.8    .045       0   513.8      .1       0
Bank Sta=488.8,513.8
XS Rating Curve= 0 ,0
Exp/Cntr=0.3,0.1

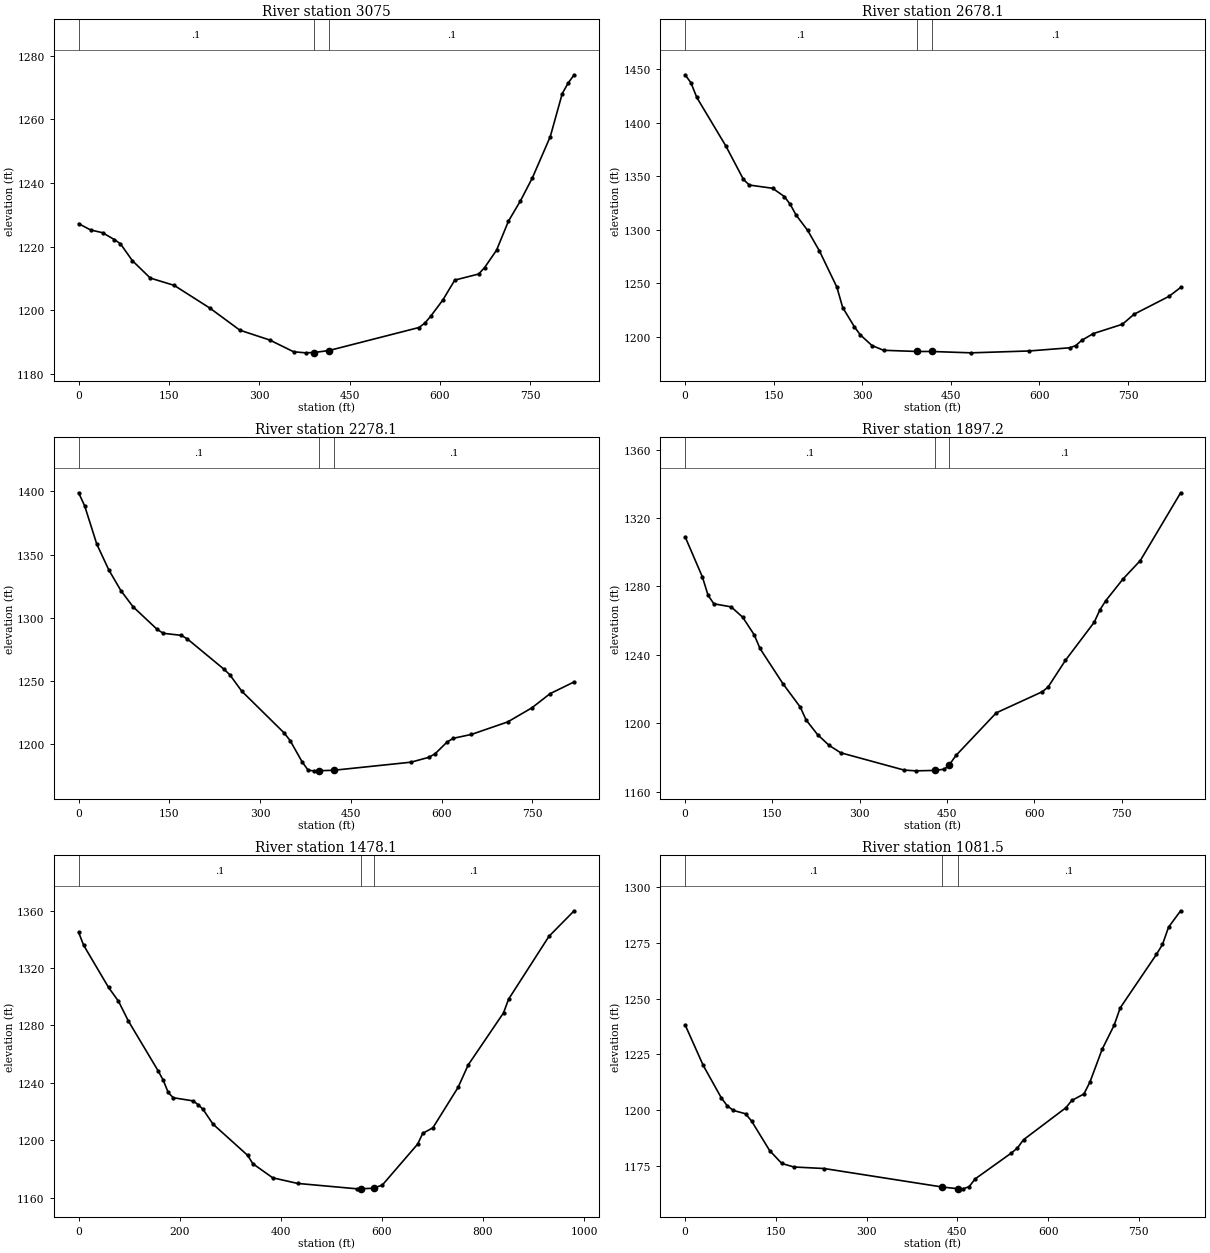
Type RM Length L Ch R = 1 ,3075    ,414.9,396.7,379
XS GIS Cut Line= 2
     1940578.479      306737.064     1941314.508      307105.292
#Sta/Elev= 30
       0 1227.27    19.8 1225.29    39.7 1224.42    59.5 1222.25    69.4 1220.96
    89.2 1215.65     119 1210.18   158.6 1207.89   218.1 1200.73   267.7 1193.82
   317.3 1190.73     357 1187.04   376.8  1186.7   390.5  1186.8   415.5 1187.41
   565.2 1194.65   575.1 1196.05     585 1198.26   604.9  1203.3   624.7 1209.54
   664.4 1211.45   674.3 1213.49   694.1 1218.94   713.9 1228.07   733.8 1234.43
   753.6 1241.65   783.3 1254.59   803.2 1268.11   813.1 1271.44     823 1274.01
#Mann= 3 , 0 , 0
       0      .1       0   390.5    .045       0   415.5      .1       0
Bank Sta=390.5,415.5
XS Rating Curve= 0 ,0
Exp/Cntr=0.3,0.1

Type RM Length L Ch R = 1 ,2678.1  ,416.8,399.7,381.6
XS GIS Cut Line= 3
     1940471.573      307375.771     1940868.818      307295.835
     1941295.596      307217.966
#Sta/Elev= 30
       0 1444.74     9.9 1437.28    19.8 1423.57    69.2 1378.03    98.8 1346.96
   108.7 1341.74   148.2 1338.71     168 1331.02   177.9 1323.79   187.8  1313.8
   207.6 1299.29   227.3 1280.37     257  1246.3   266.8 1227.33   286.6 1209.34
   296.5 1201.88   316.3 1191.84     336 1187.38   392.7 1186.26   417.7 1186.26
   484.1 1184.99   582.7 1186.74   651.7 1189.74   661.6 1191.84   671.4  1196.6
   691.1 1202.97   740.4  1211.7   760.2 1221.06   819.3 1237.77     839 1246.07
#Mann= 3 , 0 , 0
       0      .1       0   392.7    .045       0   417.7      .1       0
Bank Sta=392.7,417.7
XS Rating Curve= 0 ,0
Exp/Cntr=0.3,0.1

Type RM Length L Ch R = 1 ,2278.1  ,365.9,380.3,395.1
XS GIS Cut Line= 3
     1940803.737       307921.87     1941082.693      307622.092
     1941357.696      307318.613
#Sta/Elev= 30
       0 1398.96      10 1388.56      30 1358.37    49.9 1337.94    69.9 1321.57
    89.9 1308.86   129.8 1290.96   139.8 1287.86   169.8 1286.22   179.8 1283.36
   239.7 1259.67   249.7 1255.17   269.7 1242.06   339.6 1209.11   349.6 1203.01
   369.5 1186.09   379.5 1179.51   389.5 1179.11     397 1179.17     422 1179.58
   549.3 1185.95   579.3 1189.87   589.3 1192.67   609.3 1202.03   619.3 1204.85
   649.2  1207.9   709.2 1217.79   749.1 1228.92   779.1  1240.1     819 1249.44
#Mann= 3 , 0 , 0
       0      .1       0     397    .045       0     422      .1       0
Bank Sta=397,422
XS Rating Curve= 0 ,0
Exp/Cntr=0.3,0.1

Type RM Length L Ch R = 1 ,1897.2  ,419.6,419.2,418.6
XS GIS Cut Line= 2
     1940943.108      308014.558      1941753.31      307752.545
#Sta/Elev= 30
       0 1309.07    29.7 1285.56    39.6 1274.72    49.5 1269.85    79.2 1268.06
      99    1262   118.8  1251.7   128.7 1243.73   168.3 1223.06     198 1209.44
   207.9 1201.96   227.7 1193.36   247.5 1187.11   267.3 1182.79   376.2 1172.67
     396 1172.22     429 1172.46   445.6 1173.21     454 1175.75   465.4 1181.19
   534.7 1206.12   613.9 1218.47   623.8 1221.24   653.5 1236.79     703 1259.08
   712.9 1266.38   722.8 1271.65   752.5 1284.36   782.2 1295.13   851.5 1334.75
#Mann= 3 , 0 , 0
       0      .1       0     429    .045       0     454      .1       0
Bank Sta=429,454
XS Rating Curve= 0 ,0
Exp/Cntr=0.3,0.1

Type RM Length L Ch R = 1 ,1478.1  ,388.7,396.6,404.8
XS GIS Cut Line= 3
     1940976.726      308443.837     1941519.363      308266.035
     1941907.528      308135.582
#Sta/Elev= 30
       0 1344.82     9.8 1335.88    59.1 1306.52    78.8  1296.9    98.4 1283.12
   157.5 1248.31   167.4  1241.9   177.2 1233.39   187.1 1229.72   226.4 1227.52
   236.3 1224.95   246.1 1221.67   265.8 1211.36   334.7 1189.52   344.6 1183.82
     384    1174   433.2 1170.08   551.3 1166.31   558.5 1166.36   583.5 1166.73
     601 1168.98   670.9 1197.48   680.9 1204.96   700.9 1208.76   750.8 1236.91
   770.8 1252.52   840.7 1288.76   850.7 1298.28   930.6 1342.02   980.5 1359.81
#Mann= 3 , 0 , 0
       0      .1       0   558.5    .045       0   583.5      .1       0
Bank Sta=558.5,583.5
XS Rating Curve= 0 ,0
Exp/Cntr=0.3,0.1

Type RM Length L Ch R = 1 ,1081.5  ,465.9,460.7,455.5
XS GIS Cut Line= 3
     1941156.011      308666.212     1941565.347      308654.609
     1941974.683      308643.006
#Sta/Elev= 30
       0 1238.25      30 1220.03    59.9 1205.49    69.9 1201.85    79.9 1199.86
    99.9 1198.38   109.9  1195.1   139.8 1181.86   159.8  1176.1   179.8 1174.52
   229.7 1173.84   425.4 1165.53   450.4 1164.79   459.4 1164.73   469.4  1165.7
   479.4 1169.18   539.3  1180.8   549.3 1183.05   559.3 1186.74   629.2 1201.04
   639.2 1204.35   659.2 1207.26   669.2 1212.65   689.2 1227.24   709.1 1238.06
   719.1 1245.83     779 1269.81     789 1274.26     799    1282     819 1289.36
#Mann= 3 , 0 , 0
       0      .1       0   425.4    .045       0   450.4      .1       0
Bank Sta=425.4,450.4
XS Rating Curve= 0 ,0
Exp/Cntr=0.3,0.1

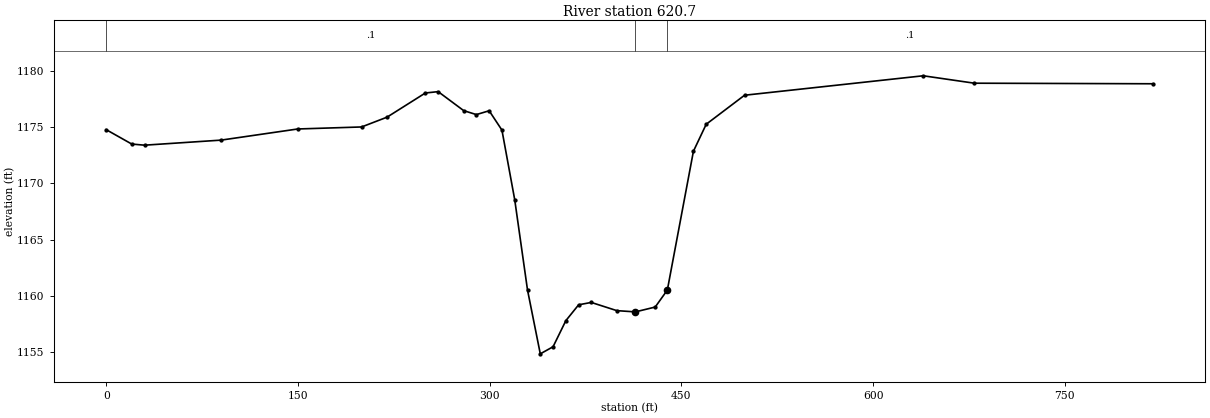
Type RM Length L Ch R = 1 ,620.7   ,643.1,620.7,598.3
XS GIS Cut Line= 3
     1941212.453      309202.721     1941612.406      309114.816
      1942012.36      309026.911
#Sta/Elev= 30
       0 1174.78      20  1173.5      30  1173.4    89.9 1173.85   149.8 1174.84
   199.8 1175.02   219.7 1175.89   249.7 1178.04   259.7 1178.16   279.7 1176.47
   289.6 1176.12   299.6 1176.46   309.6 1174.74   319.6 1168.55   329.6 1160.53
   339.6 1154.85   349.6 1155.48   359.6  1157.8   369.6 1159.21   379.5 1159.42
   399.5 1158.69     414 1158.58   429.5 1159.01     439 1160.52   459.4 1172.86
   469.4 1175.26   499.4 1177.84   639.2 1179.57   679.2 1178.91     819 1178.86
#Mann= 3 , 0 , 0
       0      .1       0     414    .045       0     439      .1       0
Bank Sta=414,439
XS Rating Curve= 0 ,0
Exp/Cntr=0.3,0.1

Chan Stop Cuts=-1
Use User Specified Reach Order=0
Composite Channel Slope=5